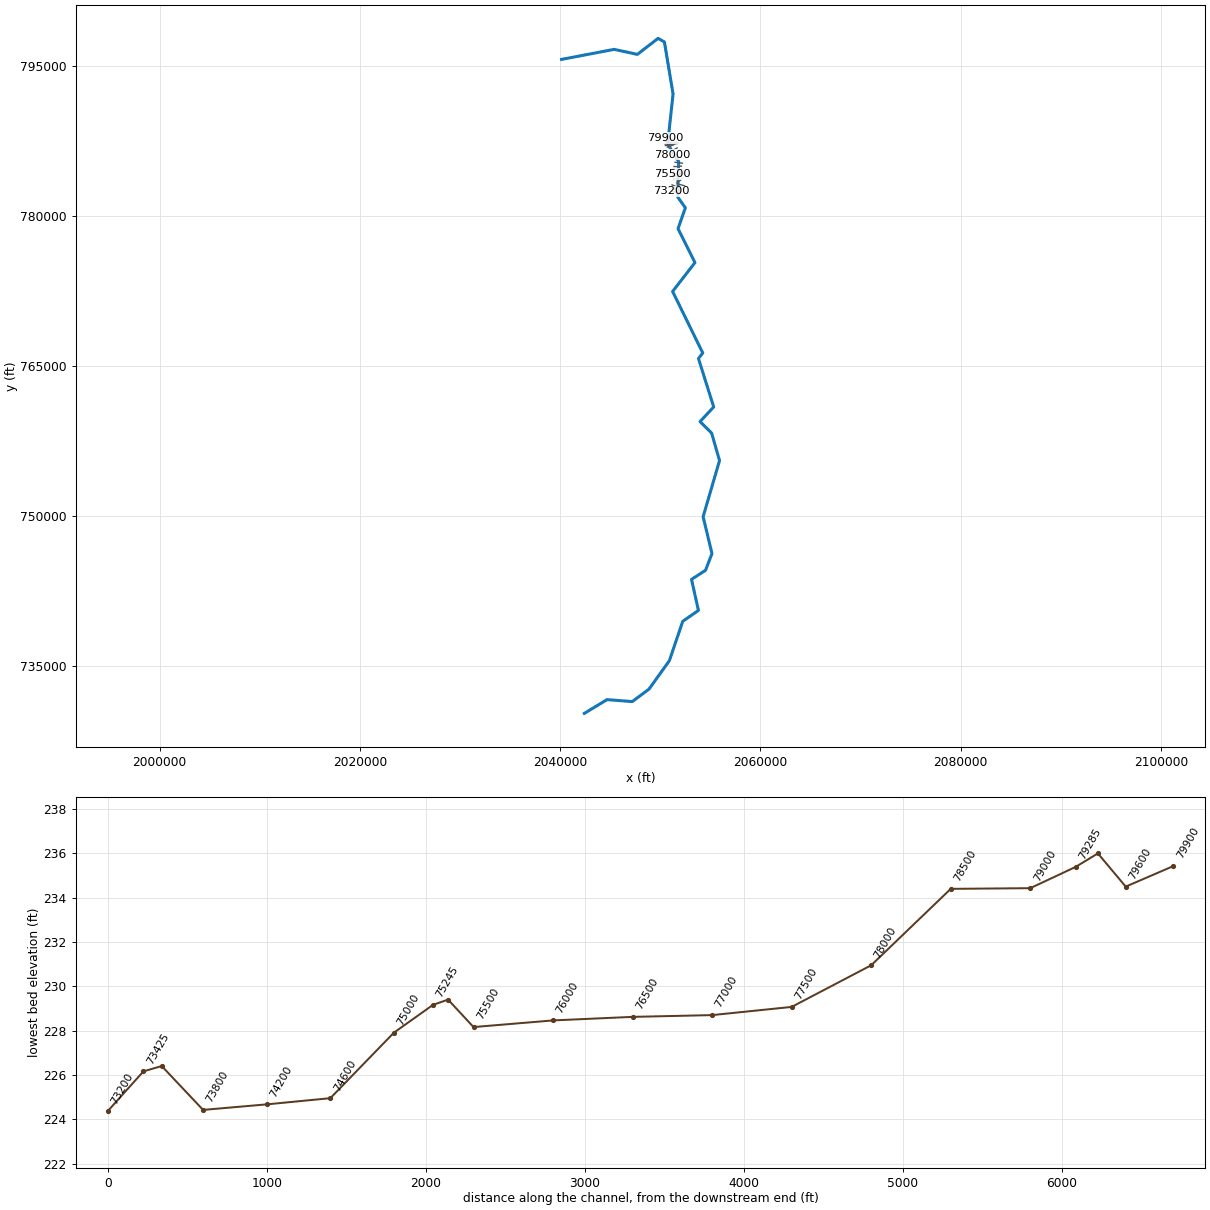
--- Cedar Creek.prj (project) ---

Proj Title=Cedar Creek Limited Detail Study
Current Plan=p05
Default Exp/Contr=0.3,0.1
English Units
Geom File=g01
Geom File=g04
Flow File=f01
Plan File=p01
Plan File=p05
Y Axis Title=Elevation
X Axis Title(PF)=Main Channel Distance
X Axis Title(XS)=Station
BEGIN DESCRIPTION:
Cedar Creek
END DESCRIPTION:
DSS Export Rating Curves= 0
DSS Export Rating Curve Sorted= 0
DSS Export Volume Flow Curves= 0
DXF OffsetX= 0
DXF OffsetY= 0
DXF ScaleX= 1
DXF ScaleY= 10

--- Cedar Creek.p05 (plan) ---

Plan Title=Proposed
Program Version=4.10
Short Identifier=Pro
Geom File=g04
Flow File=f01
Subcritical Flow
K Sum by GR= 0
Std Step Tol= 0.01
Critical Tol= 0.01
Num of Std Step Trials= 20
Max Error Tol= 0.3
Flow Tol Ratio= 0.001
Split Flow NTrial= 30
Split Flow Tol= 0.02
Split Flow Ratio= 0.02
Log Output Level= 0
Friction Slope Method= 1
Unsteady Friction Slope Method= 2
Unsteady Bridges Friction Slope Method= 1
Parabolic Critical Depth
Global Vel Dist= 1 , 1 , 1
Global Log Level= 0
CheckData=True
Encroach Param=-1 ,0,0, 0
BEGIN DESCRIPTION:
Multiple Run
END DESCRIPTION:
Computation Interval=1HOUR
Output Interval=1HOUR
Run HTab= 0
Run UNet= 0
Run PostProcess= 0
Run WQNet= 0
UNET Theta= 1
UNET Theta Warmup= 1
UNET ZTol= 0.02
UNET ZSATol= 0.05
UNET MxIter= 20
UNET MaxInSteps= 0
UNET DtIC= 0
UNET DtMin= 0
UNET MaxCRTS= 20
UNET WFStab= 2
UNET SFStab= 1
UNET WFX= 1
UNET SFX= 1
UNET DSS MLevel= 4
UNET DZMax Abort= 100
UNET Convert EG Bridges= 0
UNET Use Existing IB Tables=-1
UNET Froude Reduction=False
UNET Froude Limit= 1
UNET Froude Power= 10
UNET Time Slicing=0,0, 5
UNET Junction Losses=0
Instantaneous Interval=1HOUR
Write IC File= 0
Write IC File at Sim End=0
Echo Input=False
Echo Parameters=False
Echo Output=False
Write Detailed= 0
WQ AD Non Conservative
WQ ULTIMATE=-1
WQ Max Comp Step=1HOUR
WQ Output Interval=15MIN
WQ Output Selected Increments= 0
WQ Output face flow=0
WQ Output face velocity=0
WQ Output face area=0
WQ Output face dispersion=0
WQ Output cell volume=0
WQ Output cell surface area=0
WQ Output cell continuity=0
WQ Output cumulative cell continuity=0
WQ Output face conc=0
WQ Output face dconc_dx=0
WQ Output face courant=0
WQ Output face peclet=0
WQ Output face adv mass=0
WQ Output face disp mass=0
WQ Output cell mass=0
WQ Output cell source sink temp=0
WQ Output cell source sink nsm=0
WQ Output MaxMinRange=-1
WQ Daily Max Min Mean=-1
WQ Daily Range=0
WQ Daily Time=0
WQ Create Restart=0
WQ Fixed Restart=0
WQ System Summary=0
WQ Use Fixed Temperature=0
Sorting and Armoring Iterations= 10
XS Update Threshold= 0.02
Hydraulics Update Threshold= 0.02
Energy Slope Method= 1
Volume Change Method= 0
XS Weighting Method= 0
Number of US Weighted Cross Sections= 1
Number of DS Weighted Cross Sections= 1
Upstream XS Weight=0.25
Main XS Weight=0.5
Downstream XS Weight=0.25
Number of DS XS's Weighted with US Boundary= 1
Upstream Boundary Weight= 1
Weight of XSs Associated with US Boundary= 0
Number of US XS's Weighted with DS Boundary= 1
Downstream Boundary Weight= 0.5
Weight of XSs Associated with DS Boundary= 0.5
Sediment Output Level= 4
Mass or Volume Output= 0
Output Increment Type= 1
Profile and TS Output Increment= 10
XS Output Flag= 0
XS Output Increment= 10
Disregard all LS=0
Disregard all Conn=0
Disregard all Breaches=0
Disregard all Pumps=0

--- Cedar Creek.p01 (plan) ---

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Plan Title=Multiple Run
Short Identifier=Multiple
Geom File=g01
Flow File=f01

--- Cedar Creek.f01 (steady flow) ---

Flow Title=Multiple
Number of Profiles=5
Profile Names=10-year,25-year,50-year,100-year,500-year
River Rch & RM= Cedar Creek,Reach-1,79900
     322     420     492     563     740
River Rch & RM= Cedar Creek,Reach-1,78000
     334     437     512     585     769
River Rch & RM= Cedar Creek,Reach-1,76500
     348     454     533     609     800
River Rch & RM= Cedar Creek,Reach-1,74200
     393     513     602     687     904
River Rch & RM= Cedar Creek,Reach-1,70390
     467     608     713     814    1070
River Rch & RM= Cedar Creek,Reach-1,67500
     517     673     789     900    1183
River Rch & RM= Cedar Creek,Reach-1,65200
     559     729     855     976    1284
River Rch & RM= Cedar Creek,Reach-1,62700
     592     773     908    1039    1370
River Rch & RM= Cedar Creek,Reach-1,59260
     624     815     959    1098    1450
River Rch & RM= Cedar Creek,Reach-1,58360
     647     847     997    1143    1511
River Rch & RM= Cedar Creek,Reach-1,52770
     690     904    1066    1226    1623
River Rch & RM= Cedar Creek,Reach-1,49100
     749     983    1163    1340    1781
River Rch & RM= Cedar Creek,Reach-1,41900
     804    1056    1252    1447    1926
River Rch & RM= Cedar Creek,Reach-1,34000
     860    1132    1345    1557    2078
River Rch & RM= Cedar Creek,Reach-1,22900
     918    1211    1441    1672    2236
River Rch & RM= Cedar Creek,Reach-1,13000
     974    1286    1533    1781    2387
River Rch & RM= Cedar Creek,Reach-1,2500
    1069    1413    1689    1968    2644
Boundary for River Rch & Prof#=Cedar Creek,Reach-1,1
Up Type=0
Dn Type=3
Dn Slope=0.001
Boundary for River Rch & Prof#=Cedar Creek,Reach-1,2
Up Type=0
Dn Type=3
Dn Slope=0.001
Boundary for River Rch & Prof#=Cedar Creek,Reach-1,3
Up Type=0
Dn Type=3
Dn Slope=0.001
Boundary for River Rch & Prof#=Cedar Creek,Reach-1,4
Up Type=0
Dn Type=3
Dn Slope=0.001
Boundary for River Rch & Prof#=Cedar Creek,Reach-1,5
Up Type=0
Dn Type=3
Dn Slope=0.001

--- Cedar Creek.g04 (geometry) ---

Geom Title=Proposed
Program Version=4.10

River Reach=Cedar Creek     ,Reach-1
Reach XY= 30
      2040132.94       795610.91      2045382.96       796612.66
       2047704.1       796113.81      2049777.37       797715.05
      2050405.41       797347.95      2051269.27       792160.49
      2050727.55       787154.09      2051831.31       785404.53
      2051734.08       781852.38      2052498.15       780778.26
      2051765.31       778699.54      2053456.32       775302.72
      2051223.78       772424.32      2054233.63       766276.71
       2053806.2       765718.17      2055328.47       760877.21
       2053963.6       759420.12       2055118.6       758268.54
      2055909.24       755525.42      2054270.21       749907.13
      2055154.32        746229.5      2054509.74       744557.25
      2053108.98       743647.36      2053803.43       740550.22
      2052233.06       739459.06      2050898.71       735521.58
      2048864.05       732682.48      2047194.42       731438.49
      2044669.26       731633.05      2042411.17       730260.57

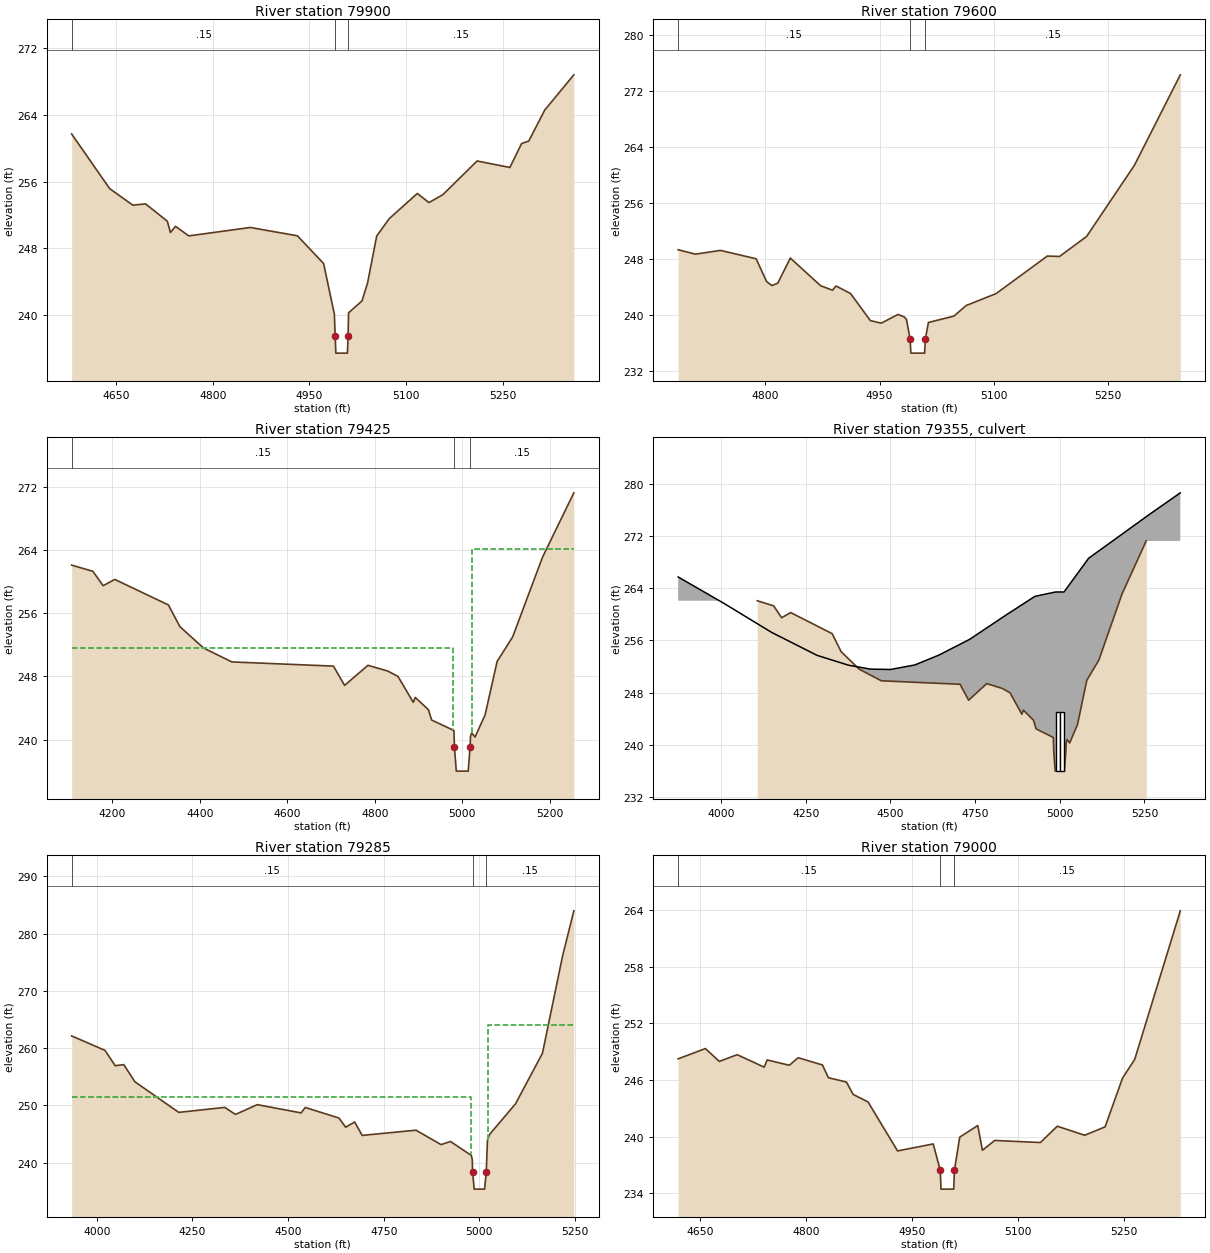
Type RM Length L Ch R = 1 ,79900   ,300,300,300
BEGIN DESCRIPTION:
CEDAR CREEK 213.0
END DESCRIPTION:
XS GIS Cut Line= 3
      2051268.78       787657.62      2050850.02       787632.68
      2050508.45       787748.91
#Sta/Elev= 30
  4580.5  261.73  4639.5  255.18  4675.5  253.19  4695.4  253.34  4729.2  251.26
    4734   249.9  4741.8  250.65  4762.6   249.5  4858.1  250.51  4931.3  249.51
    4972  246.18  4988.7  240.11    4990  237.43    4991  235.43    5009  235.43
    5010  237.43  5010.8  240.27  5031.6  241.69  5040.3  243.85  5054.5  249.49
    5074  251.57  5117.6  254.59  5135.7   253.5  5157.2  254.44  5210.5  258.49
  5261.4  257.71  5279.7  260.59  5290.7  260.87  5315.6   264.6  5360.8  268.83
#Mann= 3 ,-1 , 0
  4580.5     .15       0    4990    .045       0    5010     .15       0
Bank Sta=4990,5010
XS Rating Curve= 0 ,0
Exp/Cntr=0.3,0.1

Type RM Length L Ch R = 1 ,79600   ,175,175,175
BEGIN DESCRIPTION:
CEDAR CREEK 212.0
END DESCRIPTION:
XS GIS Cut Line= 3
      2051096.18       787309.99      2050783.69       787343.65
      2050445.99       787411.27
#Sta/Elev= 30
  4685.7  249.28  4708.6  248.65  4741.2  249.19    4788  247.99  4801.8  244.73
  4808.7  244.16  4816.5  244.51  4832.9  248.09  4872.7  244.13  4888.1   243.5
  4892.9   244.1  4911.9  243.02  4937.8  239.16  4952.1  238.78  4974.1  240.03
  4982.1  239.69  4985.2  239.33    4990   236.5    4991   234.5    5009   234.5
    5010   236.5    5014  238.88  5047.4  239.79  5063.6  241.31  5102.8  243.01
    5170  248.38    5186  248.32  5221.5  251.18  5284.4  261.39  5344.4  274.29
#Mann= 3 ,-1 , 0
  4685.7     .15       0    4990    .045       0    5010     .15       0
Bank Sta=4990,5010
XS Rating Curve= 0 ,0
Exp/Cntr=0.5,0.3

Type RM Length L Ch R = 1 ,79425   ,140,140,140
BEGIN DESCRIPTION:
CDC_Leesburg Rd-US
END DESCRIPTION:
XS GIS Cut Line= 3
      2051605.69        787332.2      2050726.02       787179.07
      2050473.18       787145.18
#Sta/Elev= 30
  4107.1  262.07  4155.5  261.29  4179.1  259.47  4205.8  260.26  4328.3  257.03
  4354.5  254.29  4408.3  251.59  4473.3  249.82  4705.6  249.29    4731  246.85
  4784.5  249.39    4830  248.66  4853.2  247.98  4888.1   244.7  4892.6  245.33
  4922.7  243.77    4930  242.47    4981  241.14  4982.2     239  4986.4     236
  5013.6     236  5017.9     239    5019  240.41  5021.4  240.83  5029.2  240.31
  5052.3  243.12  5079.7  249.88  5115.2  252.98  5183.4  263.06  5255.1  271.22
#Mann= 3 ,-1 , 0
  4107.1     .15       0  4982.2    .045       0  5017.9     .15       0
#XS Ineff= 2 , 0
       0  4978.5  251.55  5021.5       0  264.05
Permanent Ineff=
       F       F
Bank Sta=4982.2,5017.9
XS Rating Curve= 0 ,0
Exp/Cntr=0.5,0.3

Type RM Length L Ch R = 2 ,79355   ,,,
BEGIN DESCRIPTION:
CDC_Leesburg Rd-TOR
Structure ID: lds 240
Approximate Survey Structure
END DESCRIPTION:
Bridge Culvert--1,0,-1,-1, 0
Deck Dist Width WeirC Skew NumUp NumDn MinLoCord MaxHiCord MaxSubmerge Is_Ogee
9,122,3,0, 18, 18, , , 0.95, 0, 1,1,,
  3873.6  4008.7  4149.7  4284.2  4377.7  4440.9  4500.1  4571.9  4643.5  4734.2
  4843.3  4926.6  4987.5  5012.5  5085.2  5145.1  5261.9  5355.7
  265.71  261.67  257.22   253.7  252.19  251.61  251.55  252.24  253.76  256.17
  259.95  262.74  263.41  263.41  268.57  270.81  275.18  278.58
     216     216     216     216     216     216     216     216     216     216
     216     216     216     216     216     216     216     216
  3873.6  4008.7  4149.7  4284.2  4377.7  4440.9  4500.1  4571.9  4643.5  4734.2
  4843.3  4926.6  4987.5  5012.5  5085.2  5145.1  5261.9  5355.7
  265.71  261.67  257.22   253.7  252.19  251.61  251.55  252.24  253.76  256.17
  259.95  262.74  263.41  263.41  268.57  270.81  275.18  278.58
  215.39  215.39  215.39  215.39  215.39  215.39  215.39  215.39  215.39  215.39
  215.39  215.39  215.39  215.39  215.39  215.39  215.39  215.39
BR Coef= 1 , 1 , 0 ,1.25, 0 ,,,0.8,0,2,0,
WSPro=,,,, 1 ,,,, 0 ,,,, 0 ,,,,-1 ,-1 ,-1 , 0 , 0 , 0 , 0 , 0
Culvert=2,9,12,122,0.012,0.4,1,8,1,236,4993.5,235.39,4993.5,Culvert #1  , 0 ,9
Culvert Bottom n=0.012
Culvert=2,9,12,122,0.012,0.4,1,8,1,236,5006.5,235.39,5006.5,Culvert #2  , 0 ,9
Culvert Bottom n=0.012
BC Design=,, 0 ,, 0 ,,,,,,
BC HTab HWMax=271.22
BC Use User HTab Curves=0
BC User HTab FreeFlow(D)= 0

Type RM Length L Ch R = 1 ,79285   ,285,285,285
BEGIN DESCRIPTION:
CDC_Leesburg Rd-DS
END DESCRIPTION:
XS GIS Cut Line= 3
      2051799.42       787229.63      2050750.56        787041.5
      2050507.27       787000.07
#Sta/Elev= 30
  3934.4  262.14  4021.5  259.62  4048.2  256.94  4070.7  257.13  4099.6  254.14
  4214.3  248.79  4334.6  249.66  4362.6  248.43  4419.4  250.14  4534.1   248.7
  4544.9  249.65    4633   247.8  4650.5   246.2    4674  247.11  4693.7  244.77
  4834.3  245.68  4899.8  243.16  4924.4  243.71  4978.9  241.27  4981.4  240.54
  4982.2  238.39  4986.4  235.39  5013.6  235.39  5017.9  238.39  5021.1  243.95
  5026.7  244.95  5094.4  250.28  5164.8  259.12  5217.5  276.13  5246.8  283.98
#Mann= 3 ,-1 , 0
  3934.4     .15       0  4982.2    .045       0  5017.9     .15       0
#XS Ineff= 2 , 0
       0  4978.5  251.55  5021.5       0  264.05
Permanent Ineff=
       F       F
Bank Sta=4982.2,5017.9
XS Rating Curve= 0 ,0
Exp/Cntr=0.5,0.3

Type RM Length L Ch R = 1 ,79000   ,500,500,500
BEGIN DESCRIPTION:
CEDAR CREEK 208.0
END DESCRIPTION:
XS GIS Cut Line= 3
      2051356.26       787089.27      2051004.14       786944.82
      2050690.83       786843.44
#Sta/Elev= 30
  4619.4  248.24    4658  249.33  4677.6  247.97  4702.9  248.68  4741.1  247.36
  4745.3  248.12  4776.7  247.56  4789.1  248.36  4823.4  247.59  4831.9  246.24
  4857.4  245.78  4866.8  244.47  4887.9  243.67  4929.6  238.48    4980  239.22
    4990  236.43    4991  234.43    5009  234.43    5010  236.43  5017.5  239.94
    5043  241.17  5049.6  238.55  5066.9  239.59  5131.5  239.37  5155.4   241.1
  5194.1  240.14    5223  241.03  5247.7  246.21  5264.8  248.17  5329.3  263.93
#Mann= 3 ,-1 , 0
  4619.4     .15       0    4990    .045       0    5010     .15       0
Bank Sta=4990,5010
XS Rating Curve= 0 ,0
Exp/Cntr=0.3,0.1

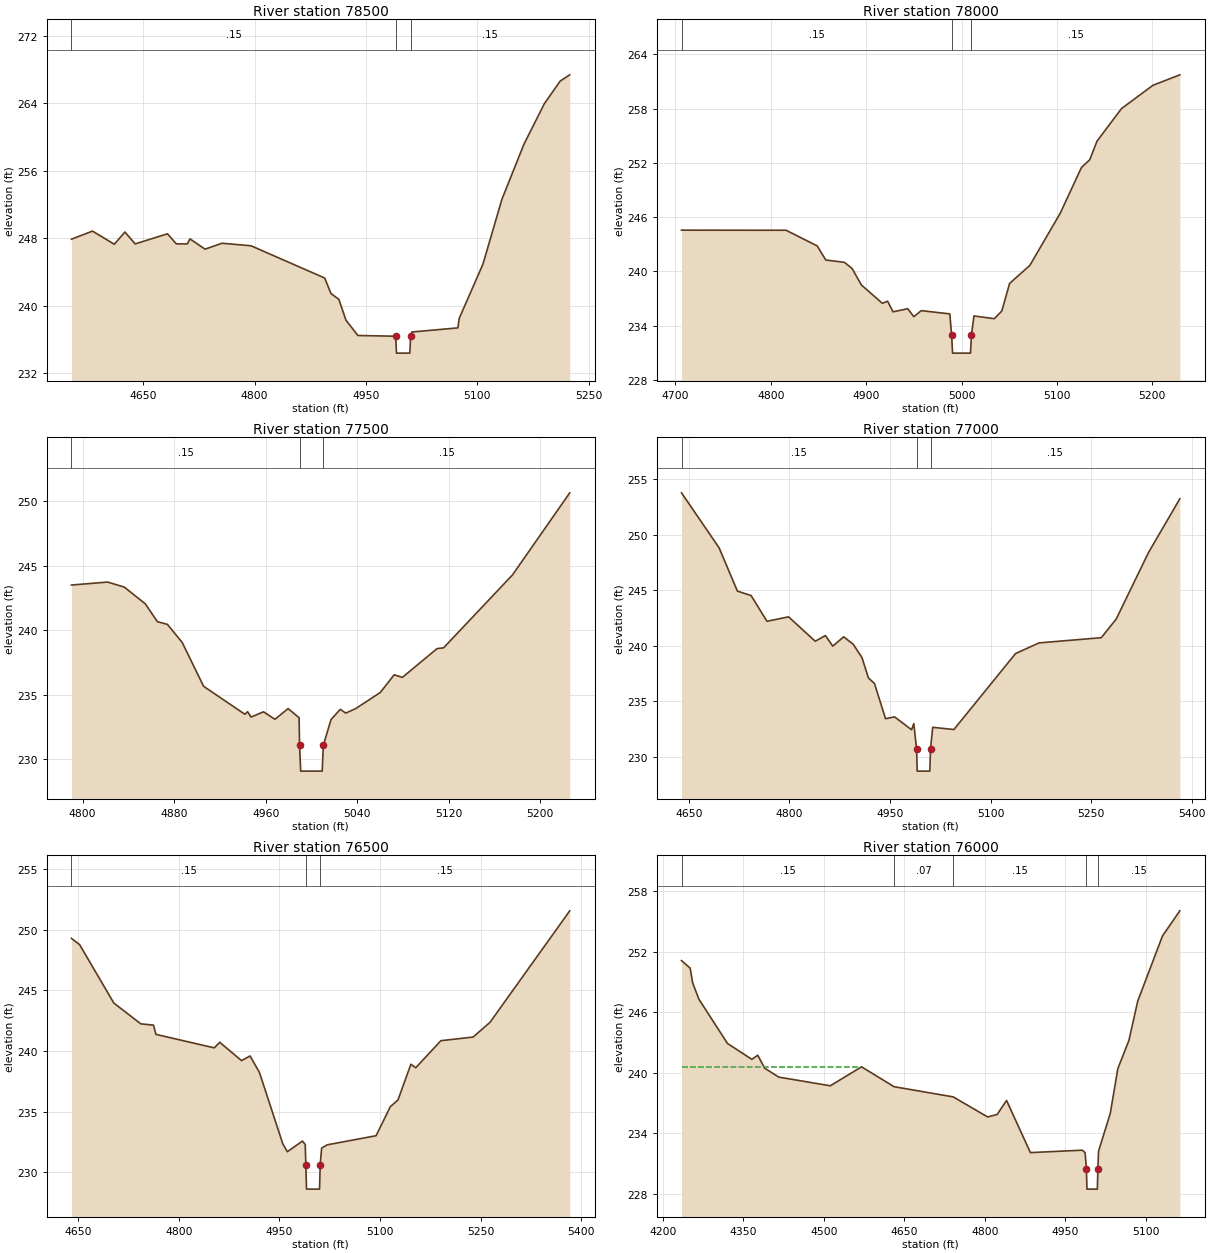
Type RM Length L Ch R = 1 ,78500   ,500,500,500
BEGIN DESCRIPTION:
CEDAR CREEK 207.0
END DESCRIPTION:
XS GIS Cut Line= 3
      2051672.91       786764.75      2051285.19       786543.11
      2051080.45       786451.51
#Sta/Elev= 30
  4553.4  247.89  4581.7  248.85  4611.1  247.29  4625.4  248.74  4639.2  247.33
  4682.7  248.53  4694.6  247.34  4709.4  247.33  4712.9  247.93  4733.3  246.71
  4756.1  247.41  4795.2  247.11  4894.4  243.29  4902.8  241.46  4913.5  240.76
    4923   238.3    4939  236.49    4990   236.4    4991   234.4    5009   234.4
    5010   236.4  5011.7   236.9  5073.7  237.39  5075.5  238.52  5107.4  244.93
    5133  252.62  5162.7  259.15  5190.1  263.93  5211.4  266.61  5224.3  267.35
#Mann= 3 ,-1 , 0
  4553.4     .15       0    4990    .045       0    5010     .15       0
Bank Sta=4990,5010
XS Rating Curve= 0 ,0
Exp/Cntr=0.3,0.1

Type RM Length L Ch R = 1 ,78000   ,500,500,500
BEGIN DESCRIPTION:
CEDAR CREEK 206.0
END DESCRIPTION:
XS GIS Cut Line= 3
      2051689.88       786092.11      2051396.55       786082.14
      2051167.79       786077.54
#Sta/Elev= 30
  4706.5  244.55  4816.1  244.54  4848.7  242.81  4857.7  241.25  4877.3  240.99
  4885.3  240.31    4895  238.49    4917  236.46  4922.5  236.69  4928.2  235.52
  4943.6  235.86    4950  234.98  4957.8  235.65  4987.7  235.29  4989.6  232.95
  4990.6  230.95  5009.4  230.95  5010.4  232.95    5013  235.06  5034.3  234.76
  5042.2   235.6  5050.4  238.66  5071.6  240.65  5103.4  246.41  5125.7  251.48
  5134.4  252.34    5142  254.39  5167.7     258  5200.6  260.57  5228.8  261.73
#Mann= 3 ,-1 , 0
  4706.5     .15       0  4989.6    .045       0  5010.4     .15       0
Bank Sta=4989.6,5010.4
XS Rating Curve= 0 ,0
Exp/Cntr=0.3,0.1

Type RM Length L Ch R = 1 ,77500   ,500,500,500
BEGIN DESCRIPTION:
CEDAR CREEK 205.0
END DESCRIPTION:
XS GIS Cut Line= 3
      2051867.19       785838.37      2051687.36       785730.31
      2051485.91        785628.3
#Sta/Elev= 30
  4790.2   243.5  4821.8  243.73  4836.4  243.34  4854.8  242.04  4865.3  240.66
  4874.1  240.45    4887  239.05  4905.7  235.65  4941.8  233.48  4944.2  233.68
  4947.2  233.26  4958.1  233.67  4968.1  233.09  4979.6  233.92  4989.2  233.21
  4989.6  231.07  4990.6  229.07  5009.4  229.07  5010.4  231.07  5017.1  233.07
  5025.2  233.86    5030  233.57  5038.9  233.93  5060.2  235.17  5072.3  236.54
  5079.5  236.34  5109.8  238.57  5115.5  238.63  5175.8  244.29  5225.8  250.65
#Mann= 3 ,-1 , 0
  4790.2     .15       0  4989.6    .045       0  5010.4     .15       0
Bank Sta=4989.6,5010.4
XS Rating Curve= 0 ,0
Exp/Cntr=0.3,0.1

Type RM Length L Ch R = 1 ,77000   ,500,500,500
BEGIN DESCRIPTION:
CEDAR CREEK 204.0
END DESCRIPTION:
XS GIS Cut Line= 3
      2052207.09       785243.44      2051847.52       785276.69
      2051468.98       785330.84
#Sta/Elev= 30
  4638.9  253.79    4695  248.83  4722.3  244.93  4742.7  244.53  4766.4  242.21
  4798.6  242.61  4838.4  240.41  4853.6  240.92  4864.6  239.97  4880.9  240.81
  4895.2  240.13  4908.1  238.94  4917.8   237.1  4926.8   236.6  4943.3  233.43
  4956.9  233.59  4982.1  232.43  4985.5  232.98  4989.6   230.7  4990.6   228.7
  5009.4   228.7  5010.4   230.7  5013.7  232.65  5045.3  232.45  5137.3   239.3
  5172.4  240.26  5265.2  240.73  5287.5  242.41  5335.7  248.41  5382.4  253.25
#Mann= 3 ,-1 , 0
  4638.9     .15       0  4989.6    .045       0  5010.4     .15       0
Bank Sta=4989.6,5010.4
XS Rating Curve= 0 ,0
Exp/Cntr=0.3,0.1

Type RM Length L Ch R = 1 ,76500   ,500,500,500
BEGIN DESCRIPTION:
CEDAR CREEK 203.0
END DESCRIPTION:
XS GIS Cut Line= 3
      2052104.32       784947.55      2051746.99         784903.
      2051364.29        784904.6
#Sta/Elev= 30
  4639.9  249.28    4652  248.77  4703.1  243.95  4743.2  242.24  4762.3  242.13
  4765.8  241.37  4852.8  240.26  4860.9  240.72  4893.4  239.21  4906.1  239.59
  4920.1  238.24  4954.9  232.36  4961.7   231.7  4984.3  232.58  4988.4  232.29
  4989.3  230.62  4990.3  228.62  5009.7  228.62  5010.7  230.62  5012.8     232
  5021.1  232.27    5094  233.02  5115.3  235.42  5126.6  235.96  5145.9  238.91
  5153.1  238.62  5190.6  240.85  5238.6  241.15  5263.8  242.36  5382.7  251.55
#Mann= 3 ,-1 , 0
  4639.9     .15       0  4989.3    .045       0  5010.7     .15       0
Bank Sta=4989.3,5010.7
XS Rating Curve= 0 ,0
Exp/Cntr=0.3,0.1

Type RM Length L Ch R = 1 ,76000   ,500,500,500
BEGIN DESCRIPTION:
CEDAR CREEK 202.0
END DESCRIPTION:
XS GIS Cut Line= 4
       2052185.3        784613.3      2051592.77       784589.01
      2051425.89       784629.72      2051267.41       784669.14
#Sta/Elev= 30
  4235.2  251.11  4251.3  250.36    4256  248.89  4267.5  247.29  4320.8   242.9
  4366.2  241.32  4377.2  241.73  4390.2  240.44  4416.5  239.56  4512.3   238.7
  4570.5  240.58  4631.1  238.61  4741.3   237.6  4805.4  235.61  4823.1  235.86
  4840.6  237.25    4885  232.08  4981.8  232.32  4986.9  232.07  4989.3  230.46
  4990.3  228.46  5009.7  228.46  5010.7  230.46  5011.9  232.21  5033.8  235.97
  5047.8  240.39  5068.5   243.2  5084.9  247.09    5131  253.55  5163.3  256.04
#Mann= 5 ,-1 , 0
  4235.2     .15       0  4631.1     .07       0  4741.3     .15       0
  4989.3    .045       0  5010.7     .15       0
#XS Ineff= 2 , 0
       0    4570   240.6               0
Permanent Ineff=
       F       F
Bank Sta=4989.3,5010.7
XS Rating Curve= 0 ,0
Exp/Cntr=0.3,0.1

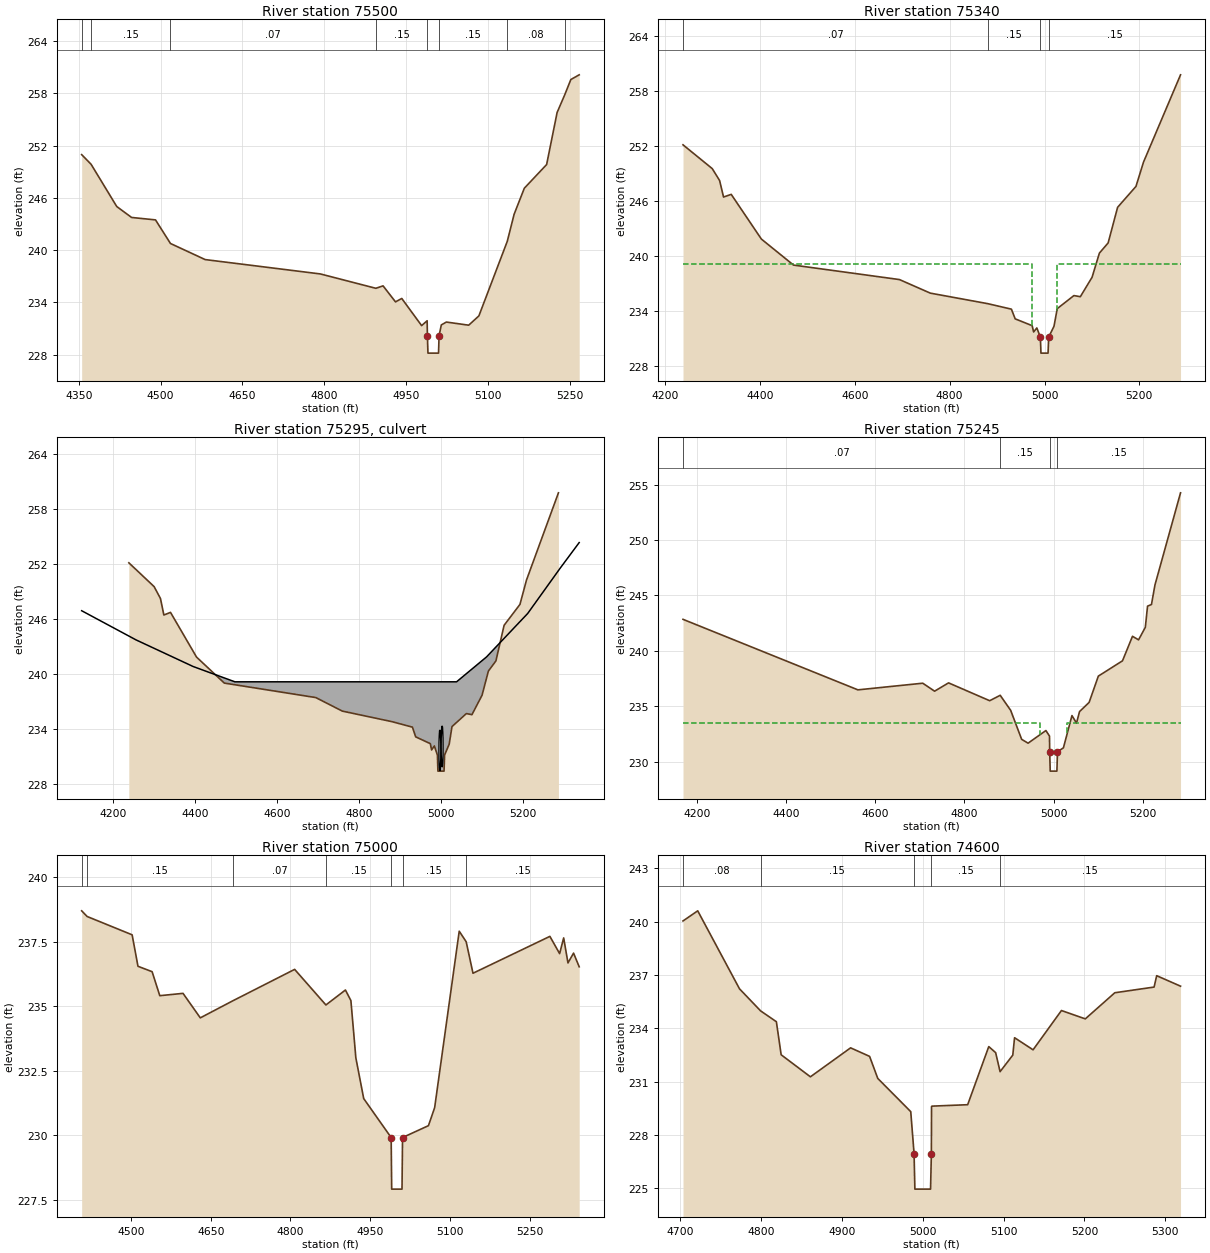
Type RM Length L Ch R = 1 ,75500   ,160,160,160
BEGIN DESCRIPTION:
CEDAR CREEK 201.0
END DESCRIPTION:
XS GIS Cut Line= 3
      2052122.14        784355.9      2051499.23       784190.11
      2051233.42       784159.21
#Sta/Elev= 30
  4355.4  250.97  4372.7  249.86  4419.7  245.01  4446.9  243.75  4490.8  243.47
  4518.2  240.76  4581.8  238.91    4793  237.26  4894.8  235.61    4908  235.89
  4930.8  234.05  4942.3  234.44  4978.7  231.32  4988.8  231.88  4989.3  230.16
  4990.3  228.16  5009.7  228.16  5010.7  230.16  5014.8   231.4  5024.1  231.73
    5065  231.37  5083.7  232.44  5135.7     241  5148.3  244.12    5167  247.11
  5207.9  249.83  5227.1  255.81  5241.4  257.89  5252.3   259.6  5267.6  260.14
#Mann= 8 ,-1 , 0
  4355.4     .07       0  4372.7     .15       0  4518.2     .07       0
  4894.8     .15       0  4989.3    .045       0  5010.7     .15       0
  5135.7     .08       0  5241.4     .15       0
Bank Sta=4989.3,5010.7
XS Rating Curve= 0 ,0
Exp/Cntr=0.5,0.3

Type RM Length L Ch R = 1 ,75340   ,95,95,95
BEGIN DESCRIPTION:
CDC_Old Leesburg Rd-US
END DESCRIPTION:
XS GIS Cut Line= 3
      2052231.92       784262.22      2051505.65       784030.32
      2051219.79       784005.93
#Sta/Elev= 30
  4237.6  252.14  4299.3  249.54  4314.8  248.24  4323.1  246.44  4339.3  246.73
  4402.9  241.85  4470.7  239.01  4694.1  237.43  4759.1  235.95  4880.3   234.8
  4930.2   234.2  4938.2  233.14  4973.9   232.4  4977.1  231.71  4983.8  232.15
  4991.3  231.15  4992.5   229.4  5007.5   229.4  5008.8  231.15    5020  232.33
  5026.9  234.26    5062  235.68  5075.6  235.56  5100.3  237.68  5115.8  240.32
  5134.2  241.43  5154.2  245.32  5192.9   247.6  5208.8  250.25  5286.9  259.78
#Mann= 4 ,-1 , 0
  4237.6     .07       0  4880.3     .15       0  4991.3    .045       0
  5008.8     .15       0
#XS Ineff= 2 , 0
       0    4974  239.15    5026       0  239.15
Permanent Ineff=
       F       F
Bank Sta=4991.3,5008.8
XS Rating Curve= 0 ,0
Exp/Cntr=0.5,0.3

Type RM Length L Ch R = 2 ,75295   ,,,
BEGIN DESCRIPTION:
CDC_Old Leesburg Rd-TOR
Structure ID: lds 241
Approximate Survey Structure
END DESCRIPTION:
Bridge Culvert--1,0,-1,-1, 0
Deck Dist Width WeirC Skew NumUp NumDn MinLoCord MaxHiCord MaxSubmerge Is_Ogee
21,48,3,0, 9, 9, , , 0.95, 0, 1,1,,
  4122.3  4254.9  4394.6  4496.6  5038.1  5111.3  5211.8  5290.9  5337.6
  246.91  243.73  240.82  239.15  239.15  241.87  246.61  251.54  254.35
   209.4   209.4   209.4   209.4   209.4   209.4   209.4   209.4   209.4
  4122.3  4254.9  4394.6  4496.6  5038.1  5111.3  5211.8  5290.9  5337.6
  246.91  243.73  240.82  239.15  239.15  241.87  246.61  251.54  254.35
  209.16  209.16  209.16  209.16  209.16  209.16  209.16  209.16  209.16
BR Coef= 1 , 1 , 0 ,1.25, 0 ,,,0.8,0,2,0,
WSPro=,,,, 1 ,,,, 0 ,,,, 0 ,,,,-1 ,-1 ,-1 , 0 , 0 , 0 , 0 , 0
Culvert=1,4.5,,48,0.012,0.2,1,1,3,229.4,4997.3,229.16,4997.3,Culvert #1  , 0 ,21
Culvert Bottom n=0.012
Culvert=1,4.5,,48,0.012,0.2,1,1,3,229.84,5002.8,229.16,5002.8,Culvert #2  , 0 ,21
Culvert Bottom n=0.012
BC Design=,, 0 ,, 0 ,,,,,,
BC HTab HWMax=259.78
BC Use User HTab Curves=0
BC User HTab FreeFlow(D)= 0

Type RM Length L Ch R = 1 ,75245   ,245,245,245
BEGIN DESCRIPTION:
CDC_Old Leesburg Rd-DS
END DESCRIPTION:
XS GIS Cut Line= 3
      2052319.95       784187.31      2051526.69       783938.38
      2051252.36       783861.49
#Sta/Elev= 30
  4168.6  242.85    4561  236.49  4706.5  237.09  4733.1  236.37  4764.4  237.12
  4856.7  235.51  4880.3     236  4903.8  234.64  4928.4  232.03  4942.8  231.68
  4982.8  232.82  4990.9  232.32  4991.3  230.91  4992.5  229.16  5007.5  229.16
  5008.8  230.91  5022.1  231.26  5041.3  234.17  5051.5  233.49  5058.3  234.53
  5079.8  235.36  5100.5  237.73  5154.7  239.11  5177.1  241.32  5190.7     241
  5205.9  242.13  5210.9  244.04  5219.7  244.19  5227.5  245.95  5284.9  254.26
#Mann= 4 ,-1 , 0
  4168.6     .07       0  4880.3     .15       0  4991.3    .045       0
  5008.8     .15       0
#XS Ineff= 2 , 0
       0    4969   233.5    5031       0   233.5
Permanent Ineff=
       F       F
Bank Sta=4991.3,5008.8
XS Rating Curve= 0 ,0
Exp/Cntr=0.5,0.3

Type RM Length L Ch R = 1 ,75000   ,400,400,400
BEGIN DESCRIPTION:
CEDAR CREEK 197.0
END DESCRIPTION:
XS GIS Cut Line= 3
      2052158.59       784097.31      2051679.68       783748.11
      2051362.05        783618.9
#Sta/Elev= 30
  4407.3   238.7  4417.6  238.48  4502.2  237.77  4513.2  236.55  4539.8  236.34
  4554.2  235.41  4597.9   235.5  4630.4  234.55  4691.4  235.21  4807.8  236.43
  4866.6  235.05  4903.3  235.63  4913.6  235.22  4922.9     233  4937.7  231.42
  4989.3  229.91  4990.3  227.91  5009.7  227.91  5010.7  229.91  5059.4  230.37
  5071.1  231.07  5117.3  237.91  5130.4   237.5  5143.2  236.28  5287.8  237.71
  5306.1  237.04  5313.7  237.65  5321.8  236.68  5332.3  237.06  5342.9  236.53
#Mann= 7 ,-1 , 0
  4407.3     .07       0  4417.6     .15       0  4691.4     .07       0
  4866.6     .15       0  4989.3    .045       0  5010.7     .15       0
  5130.4     .15       0
Bank Sta=4989.3,5010.7
XS Rating Curve= 0 ,0
Exp/Cntr=0.3,0.1

Type RM Length L Ch R = 1 ,74600   ,400,400,400
BEGIN DESCRIPTION:
CEDAR CREEK 196.0
END DESCRIPTION:
XS GIS Cut Line= 3
      2052158.56       783711.67       2051969.1        783483.6
      2051675.31       783359.57
#Sta/Elev= 30
  4703.5  240.04  4721.7  240.61  4773.4  236.22  4799.5  234.98    4819  234.37
  4824.9  232.51  4861.1  231.27  4910.8   232.9  4934.3  232.42  4944.4  231.18
  4985.2  229.31  4989.3  226.95  4990.3  224.95  5009.7  224.95  5010.7  226.95
  5010.9  229.59  5011.3  229.62  5055.6   229.7  5081.7  232.97  5090.2  232.63
  5095.7  231.56  5111.4  232.49  5113.6  233.47  5136.5  232.79  5171.6     235
  5201.1  234.53  5237.6     236  5286.2  236.32  5289.4  236.96  5318.9  236.37
#Mann= 5 ,-1 , 0
  4703.5     .08       0  4799.5     .15       0  4989.3    .045       0
  5010.7     .15       0  5095.7     .15       0
Bank Sta=4989.3,5010.7
XS Rating Curve= 0 ,0
Exp/Cntr=0.3,0.1

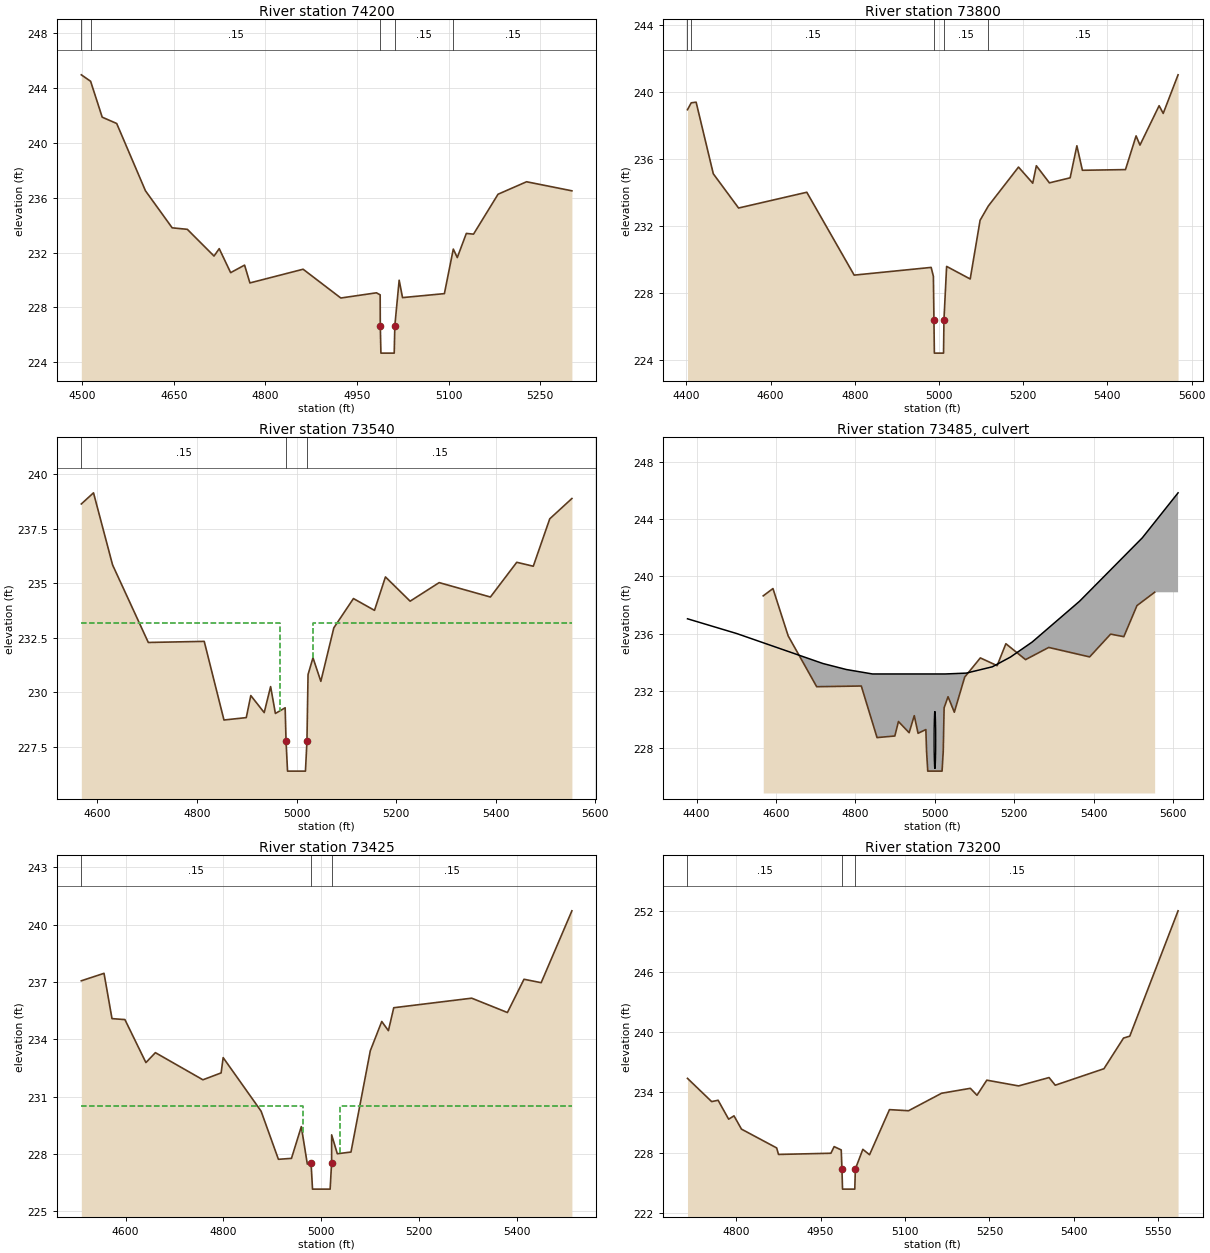
Type RM Length L Ch R = 1 ,74200   ,400,400,400
BEGIN DESCRIPTION:
CEDAR CREEK 195.0
END DESCRIPTION:
XS GIS Cut Line= 3
      2052418.39        782983.2      2051934.26       783112.88
      2051665.66       783250.29
#Sta/Elev= 30
  4498.8  244.97    4514   244.5    4533  241.88  4556.7  241.42  4603.8  236.51
  4647.5  233.81  4672.3   233.7    4716  231.75  4724.5  232.29  4743.2  230.54
    4766  231.09  4774.7  229.79  4861.8  230.79  4923.5  228.69  4981.8  229.07
  4987.9  228.92  4988.1  226.67  4989.1  224.67  5010.9  224.67  5011.9  226.67
    5019  229.99  5024.5  228.72    5093  229.01  5107.6  232.26  5114.1  231.64
  5128.9   233.4  5140.7  233.35  5180.8  236.26  5227.5  237.17  5301.7  236.51
#Mann= 5 ,-1 , 0
  4498.8     .09       0    4514     .15       0  4988.1    .045       0
  5011.9     .15       0  5107.6     .15       0
Bank Sta=4988.1,5011.9
XS Rating Curve= 0 ,0
Exp/Cntr=0.3,0.1

Type RM Length L Ch R = 1 ,73800   ,260,260,260
BEGIN DESCRIPTION:
CEDAR CREEK 194.0
END DESCRIPTION:
XS GIS Cut Line= 3
       2052241.1        782628.2      2051686.29        782848.9
      2051165.43       783074.97
#Sta/Elev= 30
  4402.9  238.93  4411.7  239.34  4423.4  239.38  4464.2  235.11  4524.2  233.07
  4686.2  234.01  4798.7  229.07  4981.5  229.53  4986.8     229  4988.1  226.42
  4989.1  224.42  5010.9  224.42  5011.9  226.42  5018.2  229.59  5074.2  228.84
  5097.7  232.34  5117.2  233.19  5188.9  235.51  5222.7  234.55  5231.3  235.59
  5262.3  234.57  5311.5  234.87  5327.5  236.78  5340.6  235.32  5442.9  235.36
  5468.1  237.37  5477.3  236.82  5522.8  239.17  5532.5  238.71  5567.8  241.01
#Mann= 5 ,-1 , 0
  4402.9     .09       0  4411.7     .15       0  4988.1    .045       0
  5011.9     .15       0  5117.2     .15       0
Bank Sta=4988.1,5011.9
XS Rating Curve= 0 ,0
Exp/Cntr=0.5,0.3

Type RM Length L Ch R = 1 ,73540   ,115,115,115
BEGIN DESCRIPTION:
CDC_Roberts Rd-US
END DESCRIPTION:
XS GIS Cut Line= 3
       2052137.8       782410.78      2051760.33       782621.51
      2051262.73       782863.45
#Sta/Elev= 30
  4567.7  238.63  4592.2  239.14  4630.5  235.84  4702.3  232.29  4814.6  232.34
  4854.3  228.74  4899.1  228.85  4908.2  229.86  4935.1  229.08    4948  230.27
  4957.6  229.04  4977.2   229.3    4979  227.78    4982   226.4    5018   226.4
    5021  227.78  5023.2  230.82  5033.1  231.59  5048.9  230.51    5075  232.96
  5114.4   234.3  5156.7  233.76  5178.7  235.29  5228.3  234.18  5286.6  235.03
  5389.6  234.37  5442.5  235.96  5475.7  235.78  5508.8  237.95  5553.3  238.88
#Mann= 3 ,-1 , 0
  4567.7     .15       0    4979    .045       0    5021     .15       0
#XS Ineff= 2 , 0
       0    4967  233.18    5033       0  233.18
Permanent Ineff=
       F       F
Bank Sta=4979,5021
XS Rating Curve= 0 ,0
Exp/Cntr=0.5,0.3

Type RM Length L Ch R = 2 ,73485   ,,,
BEGIN DESCRIPTION:
CDC_Roberts Rd-TOR
Structure ID: lds 244
Approximate Survey Structure
END DESCRIPTION:
Bridge Culvert--1,0,-1,-1, 0
Deck Dist Width WeirC Skew NumUp NumDn MinLoCord MaxHiCord MaxSubmerge Is_Ogee
31,48,3,0, 13, 13, , , 0.95, 0, 1,1,,
    4377    4501    4718  4777.2  4842.9  5025.8  5079.1  5144.6  5190.3    5245
  5364.4  5522.2  5612.3
  237.03     236  233.91  233.49  233.18  233.18  233.24  233.68  234.36  235.41
  238.26  242.68  245.82
   206.4   206.4   206.4   206.4   206.4   206.4   206.4   206.4   206.4   206.4
   206.4   206.4   206.4
    4377    4501    4718  4777.2  4842.9  5025.8  5079.1  5144.6  5190.3    5245
  5364.4  5522.2  5612.3
  237.03     236  233.91  233.49  233.18  233.18  233.24  233.68  234.36  235.41
  238.26  242.68  245.82
  206.16  206.16  206.16  206.16  206.16  206.16  206.16  206.16  206.16  206.16
  206.16  206.16  206.16
BR Coef= 1 , 1 , 0 ,1.25, 0 ,,,0.8,0,2,0,
WSPro=,,,, 1 ,,,, 0 ,,,, 0 ,,,,-1 ,-1 ,-1 , 0 , 0 , 0 , 0 , 0
Culvert=1,4,,48,0.012,0.2,1,1,3,226.57,5000,226.33,5000,Culvert #1  , 0 ,31
Culvert Bottom n=0.012
BC Design=,, 0 ,, 0 ,,,,,,
BC HTab HWMax=239.14
BC Use User HTab Curves=0
BC User HTab FreeFlow(D)= 0

Type RM Length L Ch R = 1 ,73425   ,225,225,225
BEGIN DESCRIPTION:
CDC_Roberts Rd-DS
END DESCRIPTION:
XS GIS Cut Line= 4
      2052035.65       782167.43      2051837.68       782412.06
      2051701.26       782522.94      2051231.16       782726.03
#Sta/Elev= 30
  4509.5  237.06  4555.9  237.45  4572.2  235.08  4598.6  235.03  4641.5  232.78
  4660.9   233.3    4758  231.88  4795.2  232.24  4799.4  233.04  4876.9  230.24
  4912.3  227.72    4939  227.77  4959.1  229.43  4971.4  227.47    4979  227.54
    4982  226.16    5018  226.16    5021  227.54  5021.1     229  5032.7  228.01
  5060.6   228.1  5100.1   233.4  5123.5  234.93  5137.1  234.45    5148  235.65
  5307.3  236.15  5380.3   235.4  5414.2  237.14  5449.3  236.96  5512.1  240.72
#Mann= 3 ,-1 , 0
  4509.5     .15       0    4979    .045       0    5021     .15       0
#XS Ineff= 2 , 0
       0    4962   230.5    5038       0   230.5
Permanent Ineff=
       F       F
Bank Sta=4979,5021
XS Rating Curve= 0 ,0
Exp/Cntr=0.5,0.3

Type RM Length L Ch R = 1 ,73200   ,500,500,500
BEGIN DESCRIPTION:
CEDAR CREEK 190.0
END DESCRIPTION:
XS GIS Cut Line= 3
      2051975.15       782212.82      2051702.68       782300.72
      2051133.82       782438.05
#Sta/Elev= 30
  4713.7  235.38  4756.6  233.07  4768.1   233.2  4786.8  231.32  4796.3  231.65
  4809.6  230.33  4872.1  228.46  4875.4  227.81  4968.5  227.93  4974.2  228.59
  4986.8  228.26  4988.1  226.36  4989.1  224.36  5010.9  224.36  5011.9  226.36
  5025.2  228.32  5037.1  227.78  5072.5  232.27  5106.4  232.16  5165.1   233.9
  5216.2  234.39    5228   233.7  5245.4   235.2  5301.9  234.63    5356  235.46
    5367   234.7  5453.5  236.34  5488.3  239.39  5499.4  239.58  5585.2  252.05
#Mann= 3 ,-1 , 0
  4713.7     .15       0  4988.1    .045       0  5011.9     .15       0
Bank Sta=4988.1,5011.9
XS Rating Curve= 0 ,0
Exp/Cntr=0.3,0.1