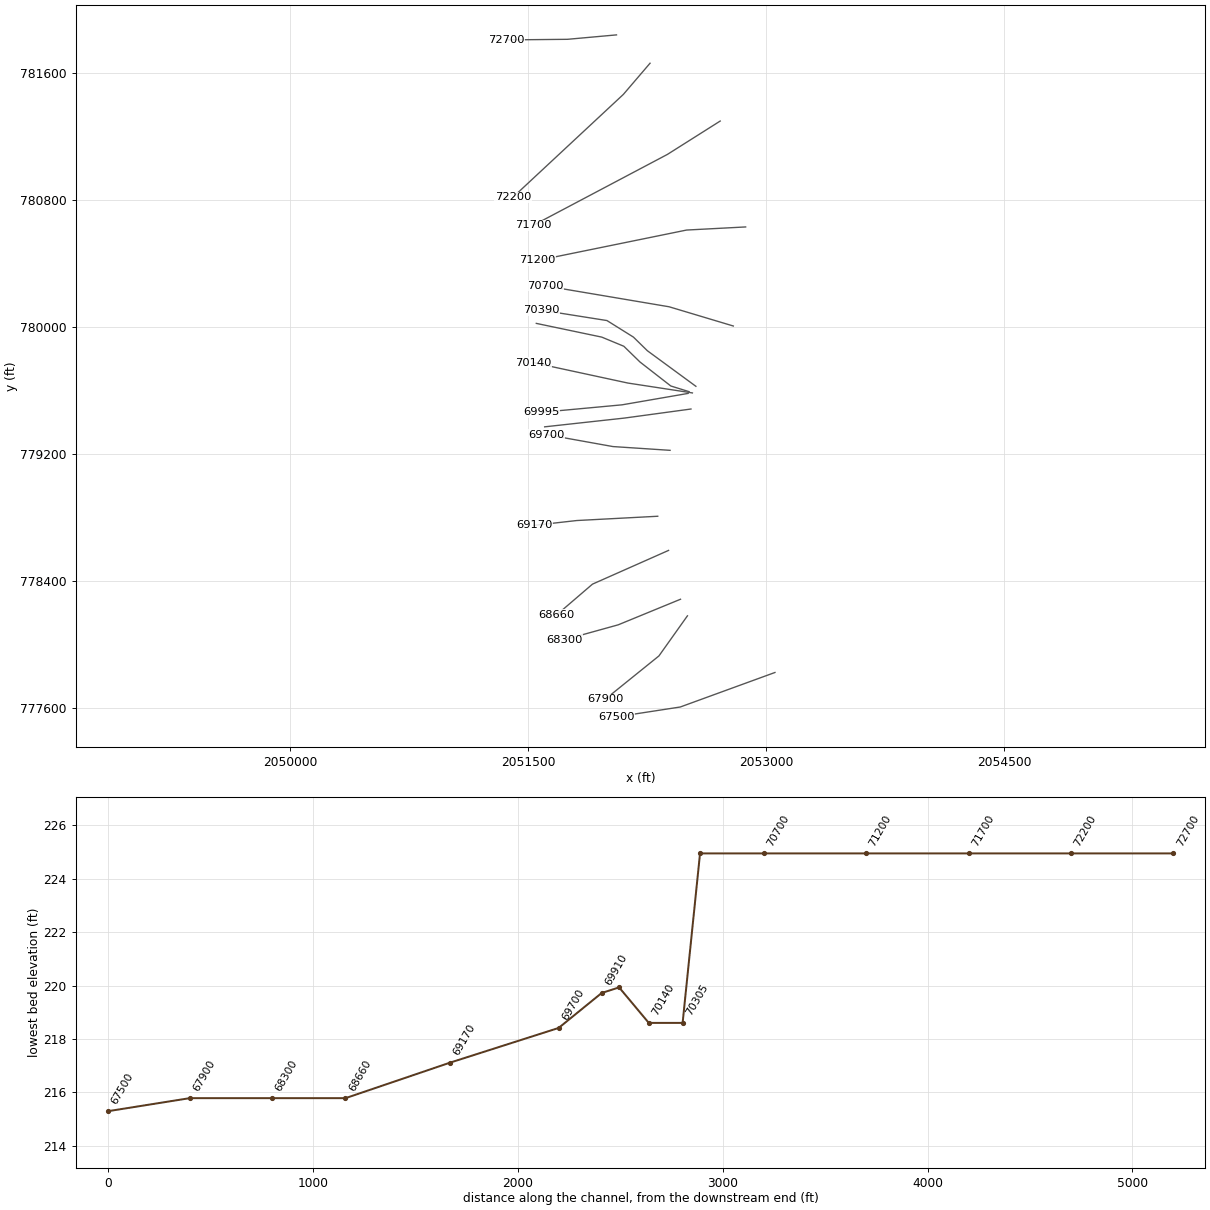
HEC-RAS study Cedar Creek.prj: Cedar Creek Limited Detail Study

--- Cedar Creek.g04 (geometry) --- (continued)

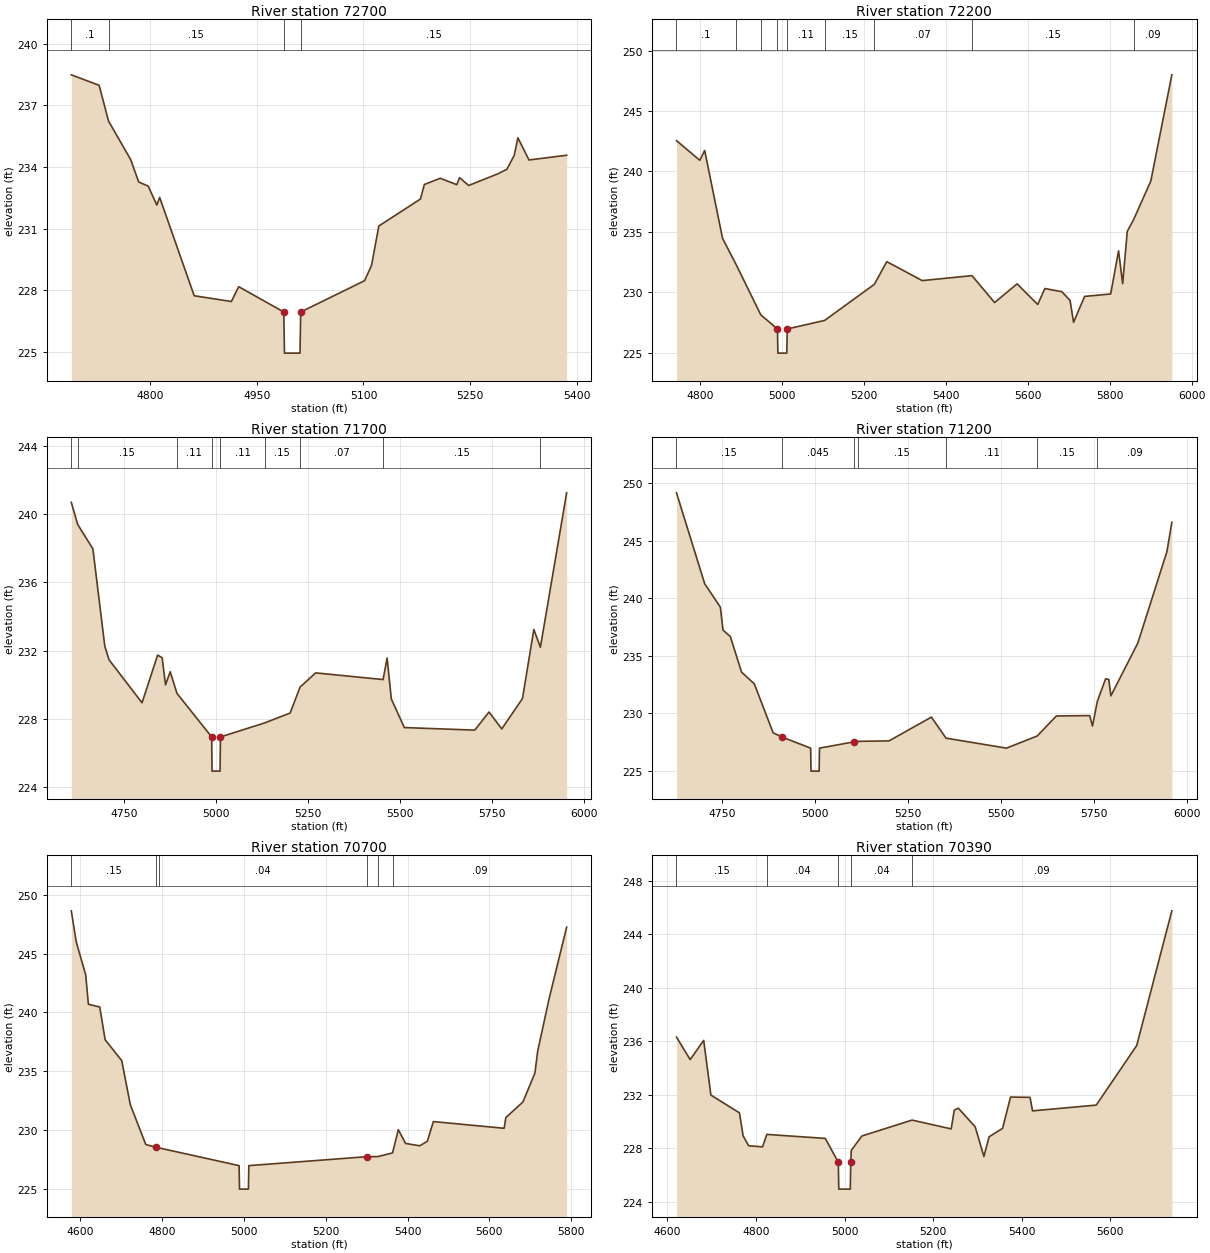
Type RM Length L Ch R = 1 ,72700   ,500,500,500
BEGIN DESCRIPTION:
CEDAR CREEK 189.0
END DESCRIPTION:
XS GIS Cut Line= 3
      2052056.53       781840.69      2051747.49       781812.79
       2051362.1       781809.13
#Sta/Elev= 30
  4689.7  238.48  4728.8  237.97    4742  236.23  4773.1  234.36  4784.3  233.27
  4797.7  233.07  4809.8  232.15  4813.8  232.52  4862.3  227.74  4914.5  227.46
  4924.8  228.18  4988.1  226.95  4989.1  224.95  5010.9  224.95  5011.9  226.95
  5101.6  228.47  5111.4  229.22  5121.6  231.13    5180  232.44  5185.6  233.15
  5207.8  233.45  5231.1  233.14    5235  233.48  5247.8   233.1  5289.7  233.68
  5301.5  233.89  5311.7  234.56  5316.9  235.42  5332.5  234.34  5385.4  234.57
#Mann= 4 ,-1 , 0
  4689.7      .1       0    4742     .15       0  4988.1    .045       0
  5011.9     .15       0
Bank Sta=4988.1,5011.9
XS Rating Curve= 0 ,0
Exp/Cntr=0.3,0.1

Type RM Length L Ch R = 1 ,72200   ,500,500,500
BEGIN DESCRIPTION:
CEDAR CREEK 188.0
END DESCRIPTION:
XS GIS Cut Line= 3
      2052267.85       781662.24      2052099.71       781465.76
      2051403.37       780817.19
#Sta/Elev= 30
  4741.4  242.56  4798.2  240.93  4810.3  241.74  4853.9  234.46  4886.5  232.33
  4947.4  228.12  4988.1  226.95  4989.1  224.95  5010.9  224.95  5011.9  226.95
  5103.3  227.66  5224.8  230.65  5255.2  232.53  5341.7  230.96  5463.3  231.37
  5518.6  229.14  5573.5  230.69  5623.9  228.98  5641.3   230.3    5683  230.04
    5703  229.31  5711.5   227.5  5738.5  229.65  5802.2  229.85  5821.4  233.43
  5831.5  230.71  5842.7  235.04    5858     236  5900.2   239.2  5951.6  248.01
#Mann= 9 ,-1 , 0
  4741.4      .1       0  4886.5     .15       0  4947.4     .11       0
  4988.1    .045       0  5011.9     .11       0  5103.3     .15       0
  5224.8     .07       0  5463.3     .15       0    5858     .09       0
Bank Sta=4988.1,5011.9
XS Rating Curve= 0 ,0
Exp/Cntr=0.3,0.1

Type RM Length L Ch R = 1 ,71700   ,500,500,500
BEGIN DESCRIPTION:
CEDAR CREEK 187.0
END DESCRIPTION:
XS GIS Cut Line= 3
      2052709.78       781297.98      2052377.13       781087.77
      2051534.51       780642.36
#Sta/Elev= 30
  4606.5  240.68  4623.8  239.39  4665.2  237.96  4697.6  232.26    4709  231.47
  4798.8  228.95  4841.1  231.74  4853.4  231.59  4862.7     230  4875.3  230.77
  4893.8   229.5  4988.1  226.95  4989.1  224.95  5010.9  224.95  5011.9  226.95
  5131.9  227.77  5201.4  228.35  5228.4  229.87  5270.8   230.7  5454.1  230.31
    5465  231.57  5476.5  229.17  5511.9   227.5  5703.3  227.35  5742.1  228.41
  5776.7  227.42    5833   229.2  5863.9  233.24  5881.7   232.2  5953.1  241.24
#Mann= 9 ,-1 , 0
  4606.5      .1       0  4623.8     .15       0  4893.8     .11       0
  4988.1    .045       0  5011.9     .11       0  5131.9     .15       0
  5228.4     .07       0  5454.1     .15       0  5881.7     .09       0
Bank Sta=4988.1,5011.9
XS Rating Curve= 0 ,0
Exp/Cntr=0.3,0.1

Type RM Length L Ch R = 1 ,71200   ,500,500,500
BEGIN DESCRIPTION:
CEDAR CREEK 186.0
END DESCRIPTION:
XS GIS Cut Line= 3
      2052870.06       780630.94      2052498.17       780611.37
      2051558.74       780419.67
#Sta/Elev= 30
  4627.6  249.16  4703.3  241.26  4745.4  239.22  4752.6  237.22  4772.4  236.65
  4802.5  233.56  4836.8  232.54  4887.2  228.29    4910  227.93  4988.1  226.95
  4989.1  224.95  5010.9  224.95  5011.9  226.95    5105   227.5  5114.4  227.54
  5198.7  227.58  5312.7  229.65  5351.9  227.82  5514.4  226.95  5597.1  228.01
  5648.5  229.75    5738  229.78  5745.5  228.87  5758.6  231.02  5780.8  232.98
  5789.3  232.93    5795   231.5  5867.5   236.1  5945.6  244.05  5958.8   246.6
#Mann= 7 ,-1 , 0
  4627.6     .15       0    4910    .045       0    5105     .11       0
  5114.4     .15       0  5351.9     .11       0  5597.1     .15       0
  5758.6     .09       0
Bank Sta=4910,5105
XS Rating Curve= 0 ,0
Exp/Cntr=0.3,0.1

Type RM Length L Ch R = 1 ,70700   ,310,310,310
BEGIN DESCRIPTION:
CEDAR CREEK 185.0
END DESCRIPTION:
XS GIS Cut Line= 3
      2052792.31       780006.88      2052387.87       780128.06
      2051609.78       780259.41
#Sta/Elev= 30
  4577.8  248.64  4589.8     246    4613  243.19  4619.6  240.69  4647.4  240.45
  4660.5  237.67  4701.1  235.89  4722.1  232.14  4759.9  228.75    4785  228.51
  4793.2  228.45  4988.1  226.95  4989.1  224.95  5010.9  224.95  5011.9  226.95
    5300  227.71  5327.2  227.72  5363.3  228.03  5377.5  230.01  5395.2  228.84
  5429.7  228.64  5448.4  229.02  5463.2   230.7  5636.2  230.13  5640.4  231.04
  5682.2  232.37  5711.5  234.83  5718.2  236.68  5746.1  241.15  5789.1  247.25
#Mann= 6 ,-1 , 0
  4577.8     .15       0    4785    .045       0  4793.2     .04       0
    5300     .04       0  5327.2     .11       0  5363.3     .09       0
Bank Sta=4785,5300
XS Rating Curve= 0 ,0
Exp/Cntr=0.3,0.1

Type RM Length L Ch R = 1 ,70390   ,85,85,85
BEGIN DESCRIPTION:
CDC_Dam (3)-US
END DESCRIPTION:
XS GIS Cut Line= 5
      2052556.57       779627.05      2052250.76       779851.27
       2052163.2       779936.97      2051996.34       780041.26
      2051582.19       780106.81
#Sta/Elev= 30
  4620.8  236.31  4651.7  234.63  4682.2  236.07  4698.4  231.98  4762.9  230.65
  4771.1  228.93  4783.7  228.19  4815.1  228.11  4824.6  229.04  4956.6  228.74
    4986  226.95    4987  224.95    5013  224.95    5014  226.95  5015.3  227.85
  5039.2  228.92  5152.4  230.11  5240.7  229.45  5247.6  230.85  5256.8     231
  5294.8  229.61  5314.5  227.39  5326.2  228.86  5356.6  229.49  5374.6  231.83
  5418.6  231.81  5424.2   230.8    5568  231.23  5659.3  235.68  5738.6  245.75
#Mann= 5 ,-1 , 0
  4620.8     .15       0  4824.6     .04       0    4986    .045       0
    5014     .04       0  5152.4     .09       0
Bank Sta=4986,5014
XS Rating Curve= 0 ,0
Exp/Cntr=0.3,0.1

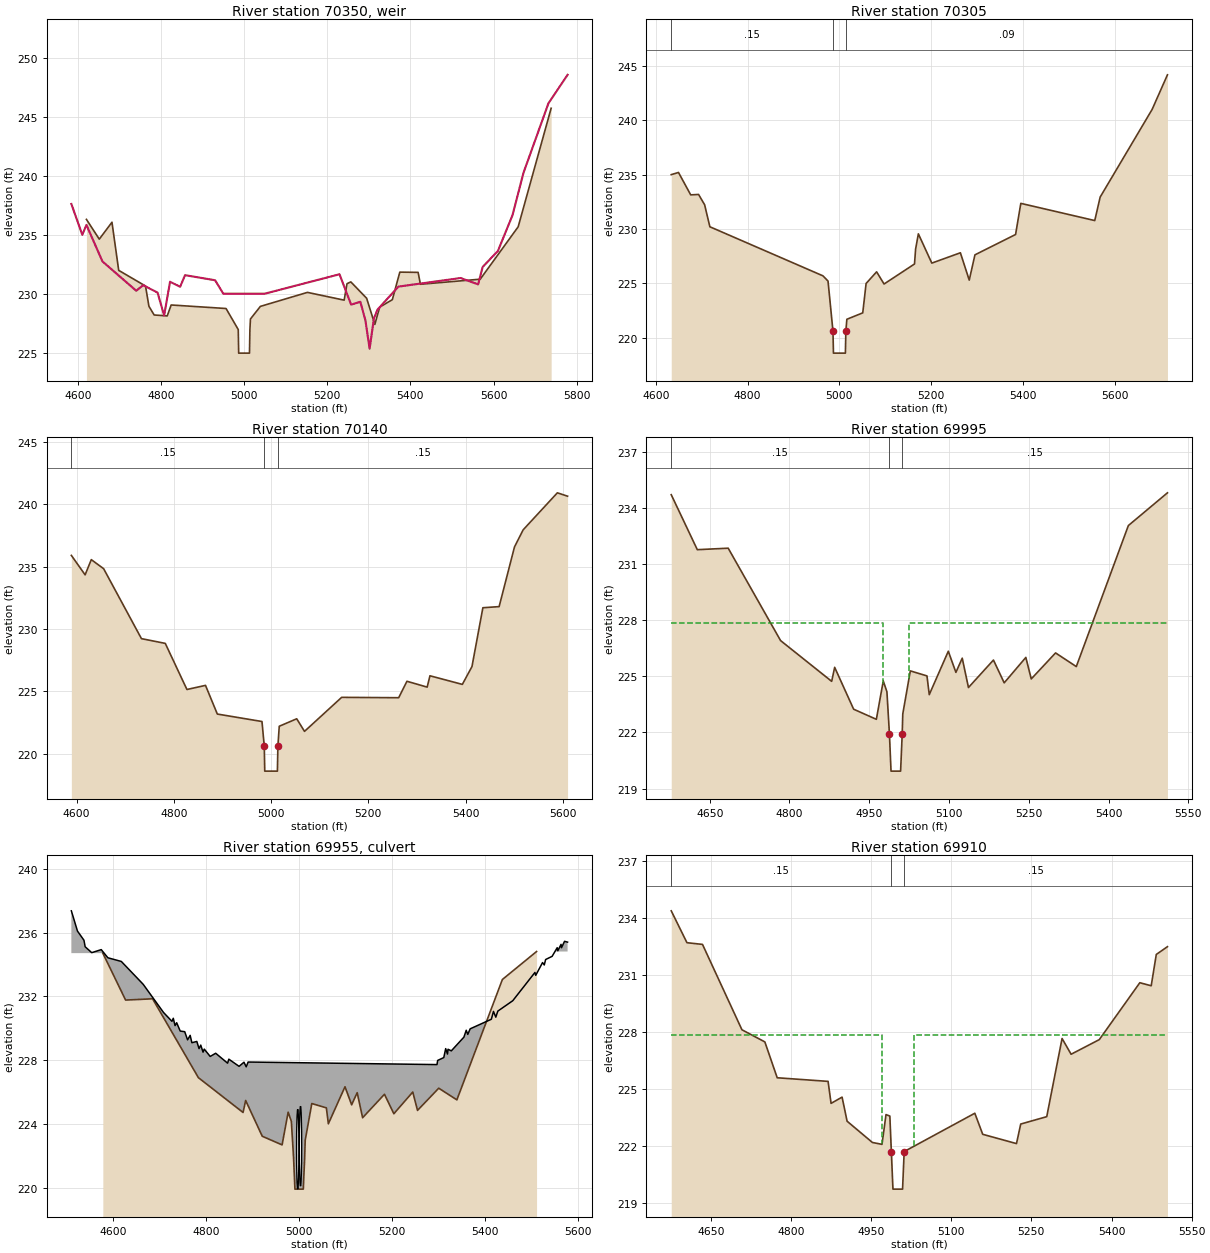
Type RM Length L Ch R = 5 ,70350   ,,,
BEGIN DESCRIPTION:
CDC_Dam (3)-TOR
Structure ID: Dam ID 245 - ESTIMATED
Approximate Survey Structure
END DESCRIPTION:
IW Pilot Flow=0
#Inline Weir SE= 30
  4584.5  237.62  4610.8     235  4620.8  235.84  4659.3  232.74  4740.5  230.25
  4757.3  230.72  4791.9  230.09  4807.7  228.15  4821.9  231.01  4846.2  230.59
  4857.9  231.57  4930.3  231.14    4950     230    5050     230  5229.5  231.65
  5257.4  229.07  5279.7  229.31  5291.9  227.72  5301.9  225.33  5312.4  227.91
  5320.8  228.64  5371.2   230.6  5520.8  231.33  5562.9  230.79  5573.9  232.27
  5610.6  233.63  5645.6  236.66    5672  240.26  5732.1  246.17  5778.1  248.59
IW Dist,WD,Coef,Skew,MaxSub,Min_El,Is_Ogee,SpillHt,DesHd
30,20,3,0,0.95,, 0 ,,,1,1,

Type RM Length L Ch R = 1 ,70305   ,165,165,165
BEGIN DESCRIPTION:
CDC_Dam (3)-DS
END DESCRIPTION:
XS GIS Cut Line= 6
      2052513.85       779593.29      2052398.61       779629.06
      2052204.83       779779.84      2052102.62       779879.36
      2051963.56       779936.97       2051551.4       780023.37
#Sta/Elev= 30
  4633.8     235  4649.6   235.2  4676.2  233.14  4693.3  233.18  4706.5  232.23
  4717.9  230.21  4964.2   225.7  4975.2  225.22    4986   220.6    4987   218.6
    5013   218.6    5014   220.6  5016.2  221.71  5050.8   222.3  5058.1     225
    5081  226.07  5097.2  224.95  5163.5  226.79  5165.9  228.16  5171.9  229.56
  5201.2  226.87  5263.4  227.82  5282.7  225.31  5295.1  227.63  5383.6   229.5
    5395  232.36    5556  230.78  5567.8  232.94  5680.9  240.99  5714.3  244.17
#Mann= 3 ,-1 , 0
  4633.8     .15       0    4986    .045       0    5014     .09       0
Bank Sta=4986,5014
XS Rating Curve= 0 ,0
Exp/Cntr=0.3,0.1

Type RM Length L Ch R = 1 ,70140   ,145,145,145
BEGIN DESCRIPTION:
CEDAR CREEK 181.0
END DESCRIPTION:
XS GIS Cut Line= 3
      2052534.69       779585.35      2052128.81       779647.44
      2051533.02       779775.97
#Sta/Elev= 30
  4589.4  235.91  4617.7  234.35  4630.4  235.57  4655.8  234.84  4733.5  229.23
  4782.5  228.85    4827  225.15  4865.2  225.48  4889.5  223.18  4981.3  222.58
    4986   220.6    4987   218.6    5013   218.6    5014   220.6  5016.8   222.2
  5052.7   222.8  5068.7  221.79  5145.1  224.52  5262.3  224.49  5279.3  225.81
  5320.9  225.34  5326.6  226.25  5393.2  225.56    5413  226.99  5435.4  231.71
  5468.8   231.8  5500.4  236.59  5518.2  237.96  5588.5  240.93  5609.5  240.66
#Mann= 3 ,-1 , 0
  4589.4     .15       0    4986    .045       0    5014     .15       0
Bank Sta=4986,5014
XS Rating Curve= 0 ,0
Exp/Cntr=0.5,0.3

Type RM Length L Ch R = 1 ,69995   ,85,85,85
BEGIN DESCRIPTION:
CDC_Harmon Rd-US
END DESCRIPTION:
XS GIS Cut Line= 3
      2052507.85       779582.37      2052091.73       779510.39
      2051583.11       779463.18
#Sta/Elev= 30
  4577.7  234.71  4626.7  231.77  4684.8  231.85  4783.3  226.91  4879.4  224.73
    4885  225.48  4920.7  223.24  4963.4   222.7  4976.4  224.75  4983.3  224.17
    4988  221.91    4991  219.93    5009  219.93    5012  221.91  5013.1  222.99
  5027.3  225.29  5058.6  225.02  5062.9  224.02  5098.7  226.34    5113  225.21
  5124.9  225.97  5136.6   224.4  5183.6  225.87  5203.8  224.65  5244.5  226.01
  5254.7  224.86  5300.4  226.25  5339.4  225.52  5437.3  233.06  5510.8  234.81
#Mann= 3 ,-1 , 0
  4577.7     .15       0    4988    .045       0    5012     .15       0
#XS Ineff= 2 , 0
       0  4975.5  227.85  5024.5       0  227.85
Permanent Ineff=
       F       F
Bank Sta=4988,5012
XS Rating Curve= 0 ,0
Exp/Cntr=0.5,0.3

Type RM Length L Ch R = 2 ,69955   ,,,
BEGIN DESCRIPTION:
CDC_Harmon Rd-TOR
Structure ID: lds 246
Approximate Survey Structure
END DESCRIPTION:
Bridge Culvert--1,0,-1,-1, 0
Deck Dist Width WeirC Skew NumUp NumDn MinLoCord MaxHiCord MaxSubmerge Is_Ogee
19,42,3,0, 60, 60, , , 0.95, 0, 1,1,,
    4510  4523.2  4537.1  4539.7  4553.8  4574.3  4588.6  4617.5  4664.5  4708.4
  4726.4  4729.3  4733.1  4736.6  4744.2  4753.9    4760  4765.6  4769.3  4779.9
  4784.7  4788.4  4793.3  4795.9  4808.7  4820.5  4846.1  4848.8  4870.8  4881.4
  4886.1  4890.3  5296.6    5298  5311.2  5315.3  5319.2  5320.3  5327.4  5354.5
  5359.5  5362.8    5368  5413.5  5418.1  5423.1  5427.5  5459.6  5507.3    5509
  5523.7  5527.4  5530.3  5544.3  5555.2  5556.5  5563.5  5564.4    5571  5577.5
  237.36  236.09  235.52  235.11  234.74  234.93  234.42  234.19  232.76  230.99
  230.44  230.63  230.17  230.35  229.83  229.79  229.28  229.56   229.1  229.18
  228.73  228.95  228.51   228.7  228.24  228.44  227.82  228.07  227.62  227.88
  227.59  227.89  227.73  227.99  228.17  228.73  228.39  228.69  228.59  229.45
  229.88  229.62  229.97  230.57  231.06   230.7  231.08  231.73   233.5  233.32
  234.12  233.97  234.31  234.51  235.05  234.86  235.26  235.05  235.45   235.4
  199.93  199.93  199.93  199.93  199.93  199.93  199.93  199.93  199.93  199.93
  199.93  199.93  199.93  199.93  199.93  199.93  199.93  199.93  199.93  199.93
  199.93  199.93  199.93  199.93  199.93  199.93  199.93  199.93  199.93  199.93
  199.93  199.93  199.93  199.93  199.93  199.93  199.93  199.93  199.93  199.93
  199.93  199.93  199.93  199.93  199.93  199.93  199.93  199.93  199.93  199.93
  199.93  199.93  199.93  199.93  199.93  199.93  199.93  199.93  199.93  199.93
    4510  4523.2  4537.1  4539.7  4553.8  4574.3  4588.6  4617.5  4664.5  4708.4
  4726.4  4729.3  4733.1  4736.6  4744.2  4753.9    4760  4765.6  4769.3  4779.9
  4784.7  4788.4  4793.3  4795.9  4808.7  4820.5  4846.1  4848.8  4870.8  4881.4
  4886.1  4890.3  5296.6    5298  5311.2  5315.3  5319.2  5320.3  5327.4  5354.5
  5359.5  5362.8    5368  5413.5  5418.1  5423.1  5427.5  5459.6  5507.3    5509
  5523.7  5527.4  5530.3  5544.3  5555.2  5556.5  5563.5  5564.4    5571  5577.5
  237.36  236.09  235.52  235.11  234.74  234.93  234.42  234.19  232.76  230.99
  230.44  230.63  230.17  230.35  229.83  229.79  229.28  229.56   229.1  229.18
  228.73  228.95  228.51   228.7  228.24  228.44  227.82  228.07  227.62  227.88
  227.59  227.89  227.73  227.99  228.17  228.73  228.39  228.69  228.59  229.45
  229.88  229.62  229.97  230.57  231.06   230.7  231.08  231.73   233.5  233.32
  234.12  233.97  234.31  234.51  235.05  234.86  235.26  235.05  235.45   235.4
  199.72  199.72  199.72  199.72  199.72  199.72  199.72  199.72  199.72  199.72
  199.72  199.72  199.72  199.72  199.72  199.72  199.72  199.72  199.72  199.72
  199.72  199.72  199.72  199.72  199.72  199.72  199.72  199.72  199.72  199.72
  199.72  199.72  199.72  199.72  199.72  199.72  199.72  199.72  199.72  199.72
  199.72  199.72  199.72  199.72  199.72  199.72  199.72  199.72  199.72  199.72
  199.72  199.72  199.72  199.72  199.72  199.72  199.72  199.72  199.72  199.72
BR Coef= 1 , 1 , 0 ,1.25, 0 ,,,0.8,0,2,0,
WSPro=,,,, 1 ,,,, 0 ,,,, 0 ,,,,-1 ,-1 ,-1 , 0 , 0 , 0 , 0 , 0
Culvert=1,5,,42,0.012,0.2,1,1,3,219.93,4997,219.72,4997,Culvert #1  , 0 ,19
Culvert Bottom n=0.012
Culvert=1,5,,42,0.012,0.2,1,1,3,220.12,5003,219.72,5003,Culvert #2  , 0 ,19
Culvert Bottom n=0.012
BC Design=,, 0 ,, 0 ,,,,,,
BC HTab HWMax=234.81
BC Use User HTab Curves=0
BC User HTab FreeFlow(D)= 0

Type RM Length L Ch R = 1 ,69910   ,210,210,210
BEGIN DESCRIPTION:
CDC_Harmon Rd-DS
END DESCRIPTION:
XS GIS Cut Line= 3
      2052525.73       779484.04       2052105.7       779426.88
      2051604.01        779371.8
#Sta/Elev= 30
  4576.1  234.39  4605.5  232.71  4634.6  232.62  4708.4  228.12  4751.3  227.48
  4774.4  225.59  4869.6   225.4  4875.2  224.24  4895.8  224.57  4905.2   223.3
  4952.5  222.18  4970.5  222.08    4978  223.65  4985.2  223.57    4988   221.7
    4991  219.72    5009  219.72    5012   221.7  5144.2  223.72    5159  222.61
  5222.2  222.12  5230.1  223.15  5278.8  223.54  5307.5  227.66  5324.4  226.83
  5377.1   227.6    5453   230.6  5474.3  230.44  5483.8  232.09  5504.7   232.5
#Mann= 3 ,-1 , 0
  4576.1     .15       0    4988    .045       0    5012     .15       0
#XS Ineff= 2 , 0
       0  4970.5  227.85  5029.5       0  227.85
Permanent Ineff=
       F       F
Bank Sta=4988,5012
XS Rating Curve= 0 ,0
Exp/Cntr=0.5,0.3

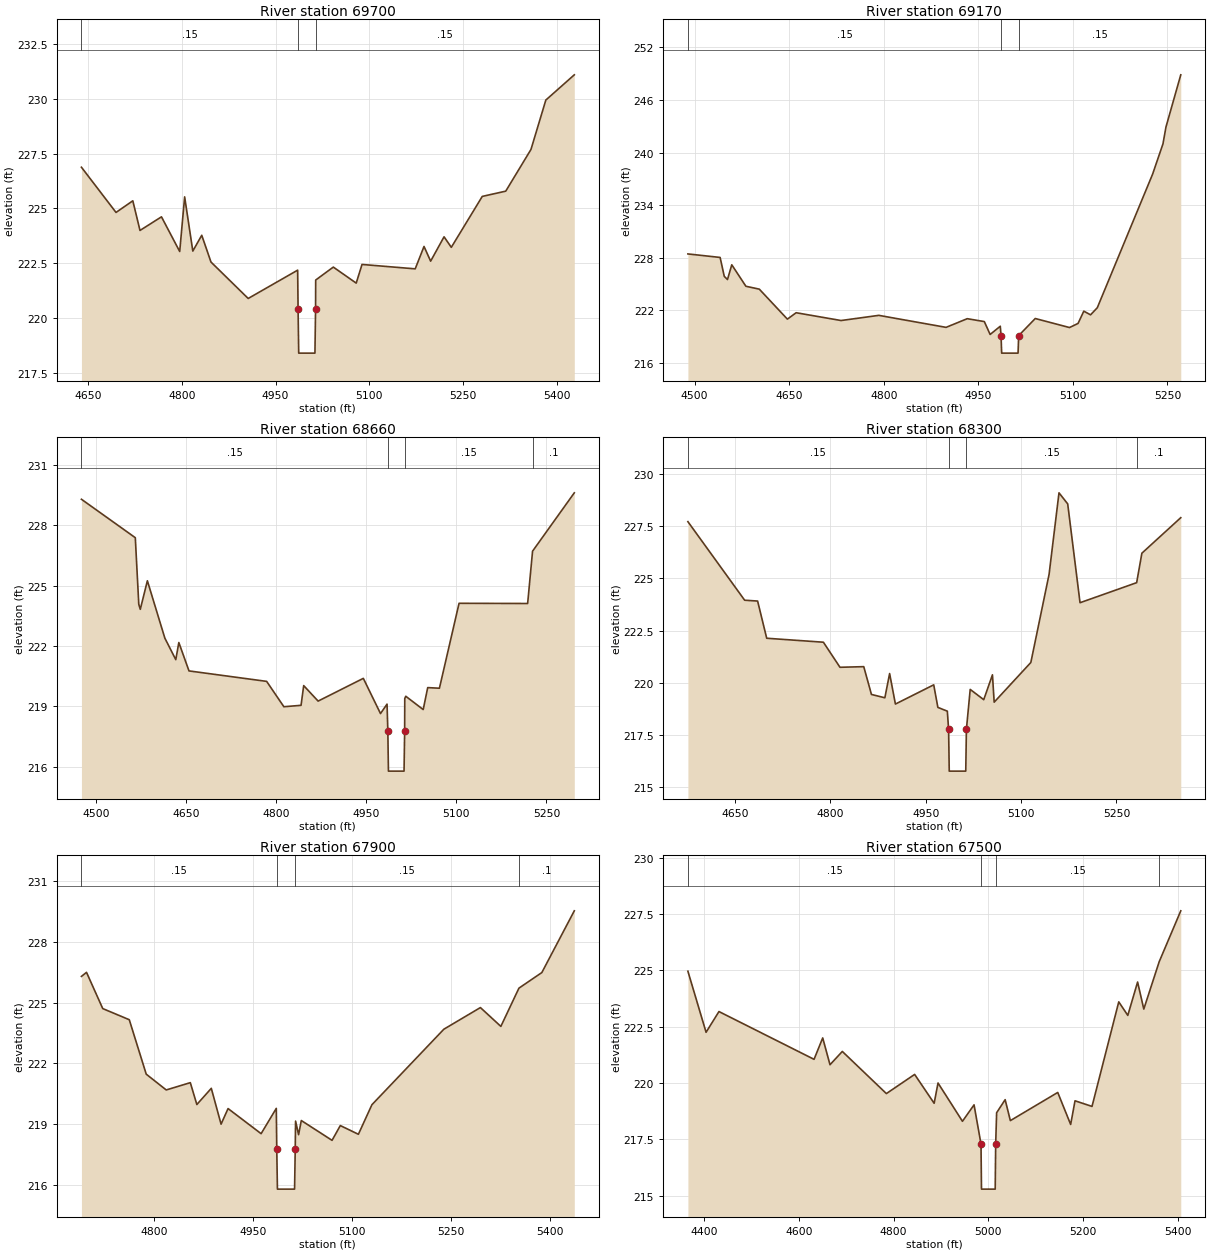
Type RM Length L Ch R = 1 ,69700   ,530,530,530
BEGIN DESCRIPTION:
CEDAR CREEK 177.0
END DESCRIPTION:
XS GIS Cut Line= 3
      2052394.09       779223.75      2052033.87        779247.5
      2051612.23       779323.31
#Sta/Elev= 30
    4639  226.88  4694.4  224.82  4721.3  225.35  4732.8     224  4767.2  224.62
  4796.4  223.04  4804.3  225.53  4817.4  223.06  4831.7  223.78  4846.5  222.56
  4906.1   220.9  4985.3  222.19    4986  220.41    4987  218.41    5013  218.41
    5014  220.41  5014.2  221.74  5042.4  222.33  5079.1   221.6  5088.4  222.45
  5173.6  222.25  5187.7  223.27  5198.3   222.6  5219.8  223.71  5231.4  223.23
    5281  225.55  5318.6  225.79    5359  227.69  5382.8  229.94  5428.4  231.09
#Mann= 3 ,-1 , 0
    4639     .15       0    4986    .045       0    5014     .15       0
Bank Sta=4986,5014
XS Rating Curve= 0 ,0
Exp/Cntr=0.3,0.1

Type RM Length L Ch R = 1 ,69170   ,510,510,510
BEGIN DESCRIPTION:
CEDAR CREEK 176.0
END DESCRIPTION:
XS GIS Cut Line= 3
      2052316.36       778808.52      2051806.37       778781.54
      2051536.97       778751.22
#Sta/Elev= 30
  4489.3  228.43  4540.4  228.03    4547  225.87  4552.1  225.51  4558.9  227.19
  4581.3  224.74  4602.6  224.41  4647.1  220.99    4661  221.72  4732.3  220.83
  4792.1  221.42  4898.8  220.05  4932.4  221.04  4959.5  220.71  4968.7  219.24
  4984.8  220.18    4986  219.11    4987  217.11    5013  217.11    5014  219.11
  5040.3  221.06  5094.6  220.03  5108.2   220.5  5117.3   221.9    5128  221.48
  5138.7  222.29  5226.4  237.53  5242.9     241  5247.6  242.91  5271.1  248.87
#Mann= 3 ,-1 , 0
  4489.3     .15       0    4986    .045       0    5014     .15       0
Bank Sta=4986,5014
XS Rating Curve= 0 ,0
Exp/Cntr=0.3,0.1

Type RM Length L Ch R = 1 ,68660   ,360,360,360
BEGIN DESCRIPTION:
CEDAR CREEK 175.0
END DESCRIPTION:
XS GIS Cut Line= 3
      2052384.44       778593.39      2051905.23       778380.92
       2051680.2       778187.86
#Sta/Elev= 30
  4475.8  229.29  4565.5  227.38  4571.3  224.07  4573.8  223.82  4585.6  225.24
  4614.7  222.39  4632.9  221.32    4638  222.17  4654.9  220.76  4784.2  220.24
  4812.9  218.98  4841.5  219.05  4845.9  220.03  4869.9  219.26  4945.2  220.39
  4973.8  218.64  4984.7  219.11    4986  217.78    4987  215.78    5013  215.78
    5014  217.78  5014.2  219.39  5015.9   219.5  5044.9  218.84  5052.4  219.93
  5071.9   219.9  5104.6  224.12  5218.8  224.11    5227  226.71  5296.5  229.61
#Mann= 4 ,-1 , 0
  4475.8     .15       0    4986    .045       0    5014     .15       0
    5227      .1       0
Bank Sta=4986,5014
XS Rating Curve= 0 ,0
Exp/Cntr=0.3,0.1

Type RM Length L Ch R = 1 ,68300   ,400,400,400
BEGIN DESCRIPTION:
CEDAR CREEK 174.0
END DESCRIPTION:
XS GIS Cut Line= 3
      2052459.71       778285.73       2052067.3        778124.6
      2051728.77       778030.75
#Sta/Elev= 30
  4575.8  227.72  4665.1  223.96  4685.5  223.92  4699.8  222.14    4789  221.95
  4815.1  220.75  4852.5  220.78  4864.6  219.45  4885.7  219.29  4893.2  220.45
  4902.3  218.99  4962.6  219.91  4969.1  218.83    4984  218.65    4986  217.78
    4987  215.78    5013  215.78    5014  217.78    5020  219.69  5041.3   219.2
    5055  220.39  5057.7  219.08  5115.4  220.98  5144.1   225.2  5159.7   229.1
  5173.4  228.57  5192.8  223.84  5281.9   224.8  5290.1  226.21  5351.3  227.91
#Mann= 4 ,-1 , 0
  4575.8     .15       0    4986    .045       0    5014     .15       0
  5281.9      .1       0
Bank Sta=4986,5014
XS Rating Curve= 0 ,0
Exp/Cntr=0.3,0.1

Type RM Length L Ch R = 1 ,67900   ,400,400,400
BEGIN DESCRIPTION:
CEDAR CREEK 173.0
END DESCRIPTION:
XS GIS Cut Line= 3
      2052503.39       778181.32      2052323.78       777928.66
      2051983.72       777654.36
#Sta/Elev= 30
    4690  226.29  4697.7  226.49  4722.3   224.7  4762.5  224.15  4788.2  221.46
  4818.5  220.68    4855  221.04  4864.9  219.96  4886.8  220.76  4901.6  218.99
  4912.2  219.76  4962.3  218.52  4985.3  219.77    4986  217.78    4987  215.78
    5013  215.78    5014  217.78  5014.5  219.14  5019.1  218.47  5023.2  219.17
  5069.8  218.19  5082.3  218.92  5109.7  218.49  5130.2  219.95  5239.2  223.68
  5294.6  224.75  5325.6  223.82    5353  225.71  5387.7  226.48  5436.9  229.53
#Mann= 4 ,-1 , 0
    4690     .15       0    4986    .045       0    5014     .15       0
    5353      .1       0
Bank Sta=4986,5014
XS Rating Curve= 0 ,0
Exp/Cntr=0.3,0.1

Type RM Length L Ch R = 1 ,67500   ,400,400,400
BEGIN DESCRIPTION:
CEDAR CREEK 172.0
END DESCRIPTION:
XS GIS Cut Line= 3
      2053054.63       777824.36      2052458.31         777607.
      2052056.55       777545.09
#Sta/Elev= 30
  4365.3  224.96  4403.7  222.25  4430.9  223.17  4631.8  221.05  4650.1     222
  4665.5  220.81  4691.5   221.4  4784.6  219.53  4844.3  220.38  4885.5   219.1
  4893.7     220  4945.3   218.3  4969.8  219.03  4984.5  217.29  4985.5  215.29
  5014.5  215.29  5015.5  217.29  5017.5  218.68  5035.5  219.26  5046.5  218.33
  5146.6  219.58  5173.9  218.16  5183.1  219.21    5219  218.96  5275.5   223.6
  5294.6     223  5315.3  224.48  5328.4  223.28  5360.9  225.38  5406.5  227.64
#Mann= 4 ,-1 , 0
  4365.3     .15       0  4984.5    .045       0  5015.5     .15       0
  5360.9      .1       0
Bank Sta=4984.5,5015.5
XS Rating Curve= 0 ,0
Exp/Cntr=0.3,0.1