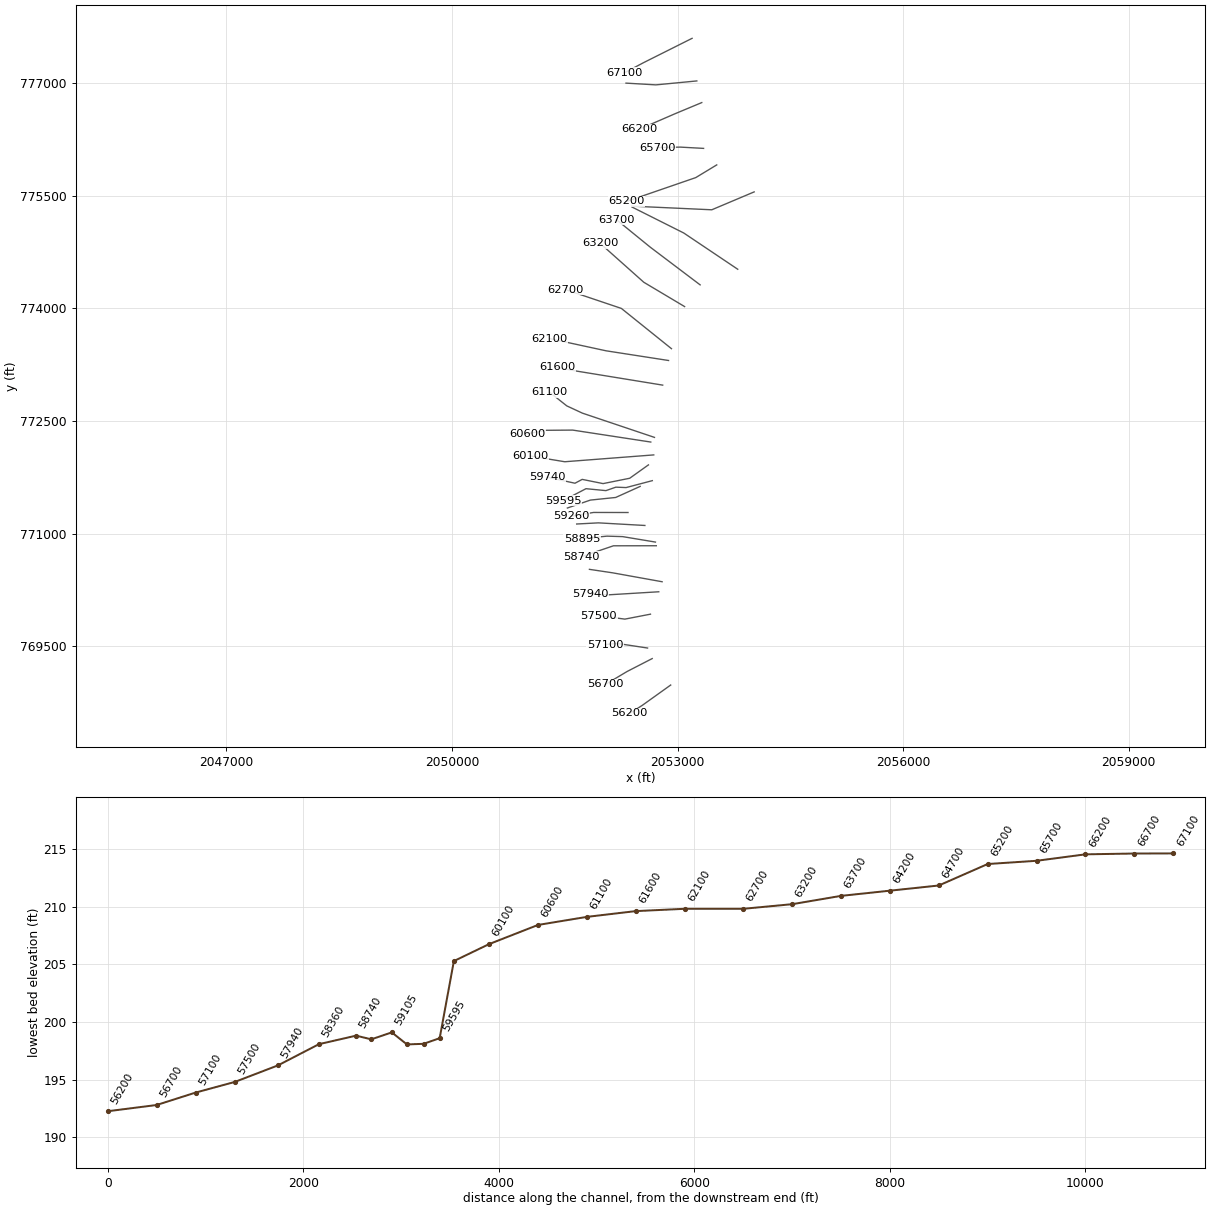
HEC-RAS study Cedar Creek.prj: Cedar Creek Limited Detail Study

--- Cedar Creek.g04 (geometry) --- (continued)

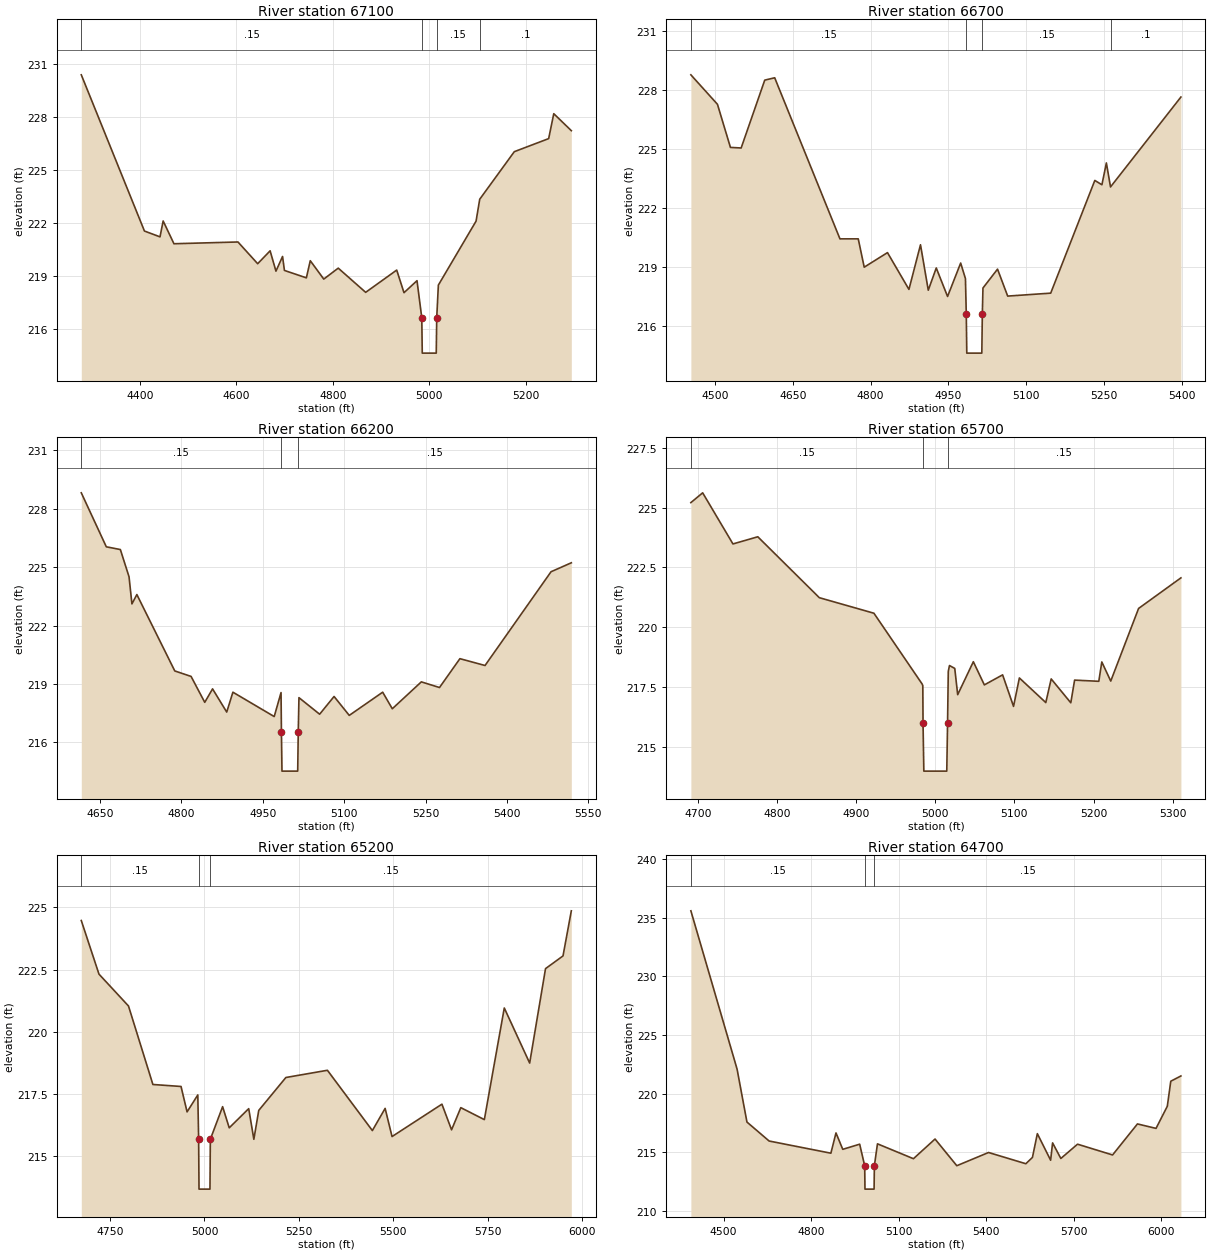
Type RM Length L Ch R = 1 ,67100   ,400,400,400
BEGIN DESCRIPTION:
CEDAR CREEK 171.0
END DESCRIPTION:
XS GIS Cut Line= 3
      2053192.98       777593.64      2052547.76       777270.09
      2052287.26       777132.29
#Sta/Elev= 30
  4278.2  230.36  4409.2  221.52  4441.5  221.19    4448  222.09  4470.4   220.8
  4603.2   220.9  4644.1  219.67  4669.9   220.4    4682  219.25  4695.7  220.08
  4699.6  219.29  4745.1  218.87  4753.2  219.84  4781.2   218.8  4811.2  219.42
  4868.1  218.05  4932.5  219.31  4947.6  218.03  4974.6  218.71  4984.5  216.61
  4985.5  214.61  5014.5  214.61  5015.5  216.61  5018.9  218.46  5097.1  222.08
  5104.7  223.32  5176.4  226.01  5247.7  226.75  5258.3  228.16  5294.7   227.2
#Mann= 4 ,-1 , 0
  4278.2     .15       0  4984.5    .045       0  5015.5     .15       0
  5104.7      .1       0
Bank Sta=4984.5,5015.5
XS Rating Curve= 0 ,0
Exp/Cntr=0.3,0.1

Type RM Length L Ch R = 1 ,66700   ,500,500,500
BEGIN DESCRIPTION:
CEDAR CREEK 170.0
END DESCRIPTION:
XS GIS Cut Line= 3
      2053256.13       777026.65      2052711.85        776974.2
      2052313.94       776997.52
#Sta/Elev= 30
  4453.2  228.75  4504.5  227.25  4529.5  225.06  4550.2  225.03  4595.7  228.48
  4614.9   228.6  4740.8  220.41  4776.1  220.41  4787.6  218.97  4832.5  219.71
  4873.9  217.84  4896.2  220.11  4911.2   217.8  4926.6  218.93  4948.4  217.48
  4973.7  219.18  4982.9  218.39  4984.5   216.6  4985.5   214.6  5014.5   214.6
  5015.5   216.6  5016.7  217.91  5044.8  218.87  5064.4   217.5  5147.4  217.65
  5232.5  223.38  5246.2  223.16  5254.8  224.27  5262.8  223.05  5398.6  227.62
#Mann= 4 ,-1 , 0
  4453.2     .15       0  4984.5    .045       0  5015.5     .15       0
  5262.8      .1       0
Bank Sta=4984.5,5015.5
XS Rating Curve= 0 ,0
Exp/Cntr=0.3,0.1

Type RM Length L Ch R = 1 ,66200   ,500,500,500
BEGIN DESCRIPTION:
CEDAR CREEK 169.0
END DESCRIPTION:
XS GIS Cut Line= 3
      2053321.72       776738.43      2052967.05       776590.45
      2052491.25        776383.9
#Sta/Elev= 30
  4615.7  228.81  4661.8  226.04  4687.7   225.9  4703.7   224.5    4709  223.11
  4718.1  223.59    4788  219.67    4818  219.39  4843.2  218.06  4857.6  218.75
  4883.7  217.56  4895.1  218.58  4971.2  217.33  4983.8  218.56  4984.5  216.53
  4985.5  214.53  5014.5  214.53  5015.5  216.53  5016.8   218.3  5054.9  217.45
  5081.5  218.36  5109.5  217.39  5171.1  218.58  5188.8  217.73  5242.3  219.11
  5275.8  218.82  5313.4   220.3  5359.7  219.95  5481.3  224.76  5518.7  225.22
#Mann= 3 ,-1 , 0
  4615.7     .15       0  4984.5    .045       0  5015.5     .15       0
Bank Sta=4984.5,5015.5
XS Rating Curve= 0 ,0
Exp/Cntr=0.3,0.1

Type RM Length L Ch R = 1 ,65700   ,500,500,500
BEGIN DESCRIPTION:
CEDAR CREEK 168.0
END DESCRIPTION:
XS GIS Cut Line= 3
      2053345.94       776128.93       2053037.4       776145.77
      2052726.96       776139.76
#Sta/Elev= 30
    4691  225.21  4705.9  225.62  4744.2  223.48  4775.6  223.78  4853.4  221.23
  4922.4  220.58  4983.3  217.62  4984.2  217.55  4984.5  215.97  4985.5  213.97
  5014.5  213.97  5015.5  215.97  5016.4  218.14  5017.9  218.39  5024.6  218.27
  5028.3  217.17  5048.1  218.55    5062  217.58  5085.1     218  5098.9  216.68
  5106.3  217.87  5139.7  216.84  5146.5  217.83  5171.3  216.83  5176.1  217.78
  5206.7  217.73  5210.5  218.54  5221.8  217.74    5257  220.78  5310.5  222.06
#Mann= 3 ,-1 , 0
    4691     .15       0  4984.5    .045       0  5015.5     .15       0
Bank Sta=4984.5,5015.5
XS Rating Curve= 0 ,0
Exp/Cntr=0.3,0.1

Type RM Length L Ch R = 1 ,65200   ,500,500,500
BEGIN DESCRIPTION:
CEDAR CREEK 167.0
END DESCRIPTION:
XS GIS Cut Line= 3
      2053520.86       775909.19       2053241.9       775740.11
      2052323.65        775423.5
#Sta/Elev= 30
  4673.8  224.47  4720.6  222.32  4798.8  221.04  4863.4  217.89  4937.9  217.81
  4953.9  216.79  4982.3  217.47  4984.5  215.69  4985.5  213.69  5014.5  213.69
  5015.5  215.69    5048     217  5065.5  216.15  5117.1  216.92  5130.7  215.69
  5143.7  216.85  5215.5  218.17  5325.5  218.46  5444.5  216.04  5478.3  216.93
  5496.6   215.8  5628.7   217.1  5654.2  216.07  5678.7  216.96    5741  216.48
  5793.8  220.96    5861  218.75    5903  222.54  5949.3  223.05  5971.3  224.86
#Mann= 3 ,-1 , 0
  4673.8     .15       0  4984.5    .045       0  5015.5     .15       0
Bank Sta=4984.5,5015.5
XS Rating Curve= 0 ,0
Exp/Cntr=0.3,0.1

Type RM Length L Ch R = 1 ,64700   ,500,500,500
BEGIN DESCRIPTION:
CEDAR CREEK 166.0
END DESCRIPTION:
XS GIS Cut Line= 3
      2054018.61       775549.78      2053454.85       775311.64
      2052389.26       775360.38
#Sta/Elev= 30
    4388  235.61  4546.2  222.09  4580.1  217.56  4656.1  215.94  4867.6   214.9
  4885.1  216.63  4908.3  215.23  4966.2  215.67  4983.4  213.83  4984.4  211.83
  5015.6  211.83  5016.6  213.83  5027.2   215.7  5150.4  214.43  5224.4  216.11
    5299  213.83  5407.7  214.96  5535.5     214  5558.1  214.54  5574.9  216.57
  5620.4   214.3  5627.1  215.78  5655.4  214.45  5712.6  215.67  5832.6  214.75
  5917.8   217.4  5981.5  217.02  6020.1  218.91    6032  221.05  6066.7   221.5
#Mann= 3 ,-1 , 0
    4388     .15       0  4983.4    .045       0  5016.6     .15       0
Bank Sta=4983.4,5016.6
XS Rating Curve= 0 ,0
Exp/Cntr=0.3,0.1

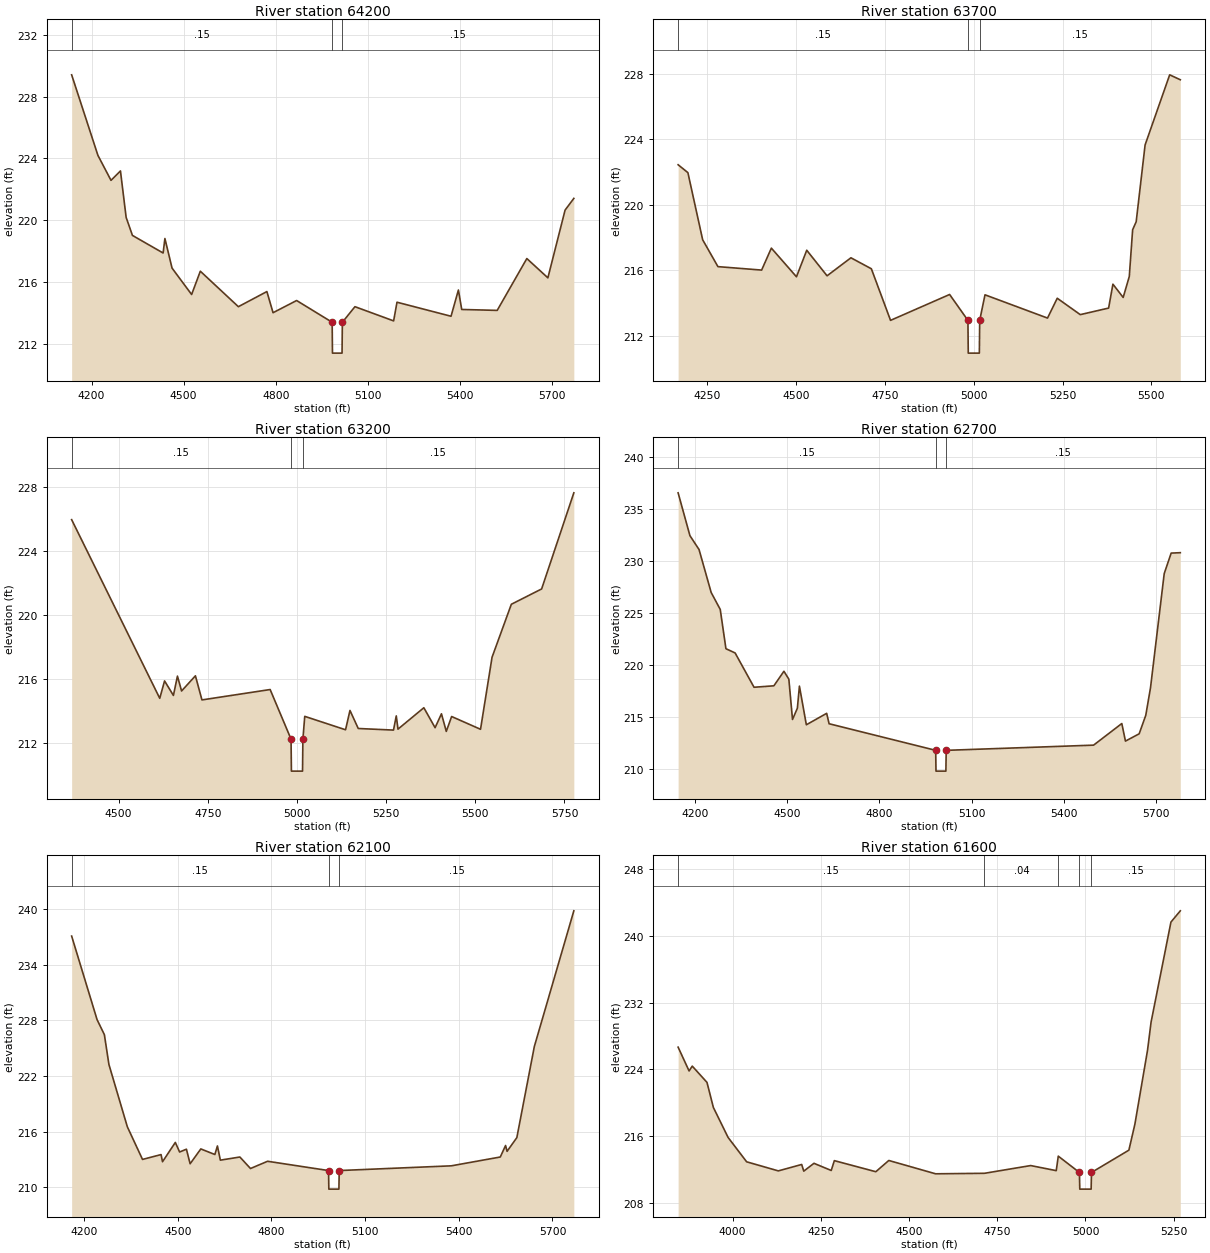
Type RM Length L Ch R = 1 ,64200   ,500,500,500
BEGIN DESCRIPTION:
CEDAR CREEK 165.0
END DESCRIPTION:
XS GIS Cut Line= 3
      2053800.04       774520.22      2053082.36       775002.55
       2052394.1       775348.24
#Sta/Elev= 30
  4135.3  229.42  4220.8   224.2  4263.4  222.58  4294.2  223.19  4312.7  220.18
  4333.2  219.01  4433.1  217.87  4438.9  218.81  4462.2  216.89  4525.9  215.18
  4554.2  216.69  4678.1  214.39  4770.9  215.37    4791     214  4867.7  214.79
  4983.4  213.38  4984.4  211.38  5015.6  211.38  5016.6  213.38  5057.6  214.39
  5183.5  213.47  5194.5  214.68  5370.4  213.77  5394.4  215.47  5405.2  214.21
  5520.7  214.15  5617.2  217.51  5685.7  216.26  5741.7  220.65  5770.2  221.41
#Mann= 3 ,-1 , 0
  4135.3     .15       0  4983.4    .045       0  5016.6     .15       0
Bank Sta=4983.4,5016.6
XS Rating Curve= 0 ,0
Exp/Cntr=0.3,0.1

Type RM Length L Ch R = 1 ,63700   ,500,500,500
BEGIN DESCRIPTION:
CEDAR CREEK 164.0
END DESCRIPTION:
XS GIS Cut Line= 3
      2053299.82       774312.36        2052636.       774814.58
      2052185.26       775181.66
#Sta/Elev= 30
  4167.6  222.43  4195.1  221.95  4236.7  217.85  4279.7  216.21  4402.7     216
  4430.1  217.34  4500.8  215.59  4529.7  217.21  4586.9  215.65  4654.1  216.75
  4711.6  216.08  4765.6  212.93  4931.9  214.51  4983.4  212.93  4984.4  210.93
  5015.6  210.93  5016.6  212.93  5031.5  214.49  5207.5  213.07  5234.9  214.28
  5299.7  213.28  5379.5  213.68  5391.6  215.14  5420.5  214.33  5437.7  215.61
  5447.1  218.46  5457.1  218.95  5482.2  223.64  5551.4  227.92  5581.3  227.62
#Mann= 3 ,-1 , 0
  4167.6     .15       0  4983.4    .045       0  5016.6     .15       0
Bank Sta=4983.4,5016.6
XS Rating Curve= 0 ,0
Exp/Cntr=0.3,0.1

Type RM Length L Ch R = 1 ,63200   ,500,500,500
BEGIN DESCRIPTION:
CEDAR CREEK 163.0
END DESCRIPTION:
XS GIS Cut Line= 3
      2053093.47       774023.36      2052550.93       774346.92
      2051971.61       774863.53
#Sta/Elev= 30
  4368.3  225.96  4615.3  214.77  4628.8  215.86  4653.6  214.95  4664.9  216.16
  4676.5  215.23  4715.3  216.18  4733.6  214.67  4924.8  215.32  4983.4  212.21
  4984.4  210.21  5015.6  210.21  5016.6  212.21  5021.8  213.64  5136.2   212.8
  5148.6  214.01  5171.8  212.88  5270.6  212.78  5278.4  213.67  5283.2  212.84
  5355.7  214.18  5387.2  212.93  5405.1   213.8  5418.6   212.7  5433.6  213.63
  5514.6  212.83  5546.9  217.34    5601  220.66  5685.9  221.62  5776.2  227.64
#Mann= 3 ,-1 , 0
  4368.3     .15       0  4983.4    .045       0  5016.6     .15       0
Bank Sta=4983.4,5016.6
XS Rating Curve= 0 ,0
Exp/Cntr=0.3,0.1

Type RM Length L Ch R = 1 ,62700   ,600,600,600
BEGIN DESCRIPTION:
CEDAR CREEK 162.0
END DESCRIPTION:
XS GIS Cut Line= 3
      2052918.64       773463.14      2052252.63       773998.81
      2051515.03       774247.51
#Sta/Elev= 30
  4145.3  236.59  4183.7  232.47  4213.4  231.13  4252.8     227  4282.3  225.37
  4300.8  221.59  4330.7  221.18  4392.2  217.88  4456.7  218.02  4489.4  219.42
  4505.4  218.66  4517.3  214.78  4533.1  215.86  4539.8  217.99  4562.3  214.27
  4628.4  215.37  4636.3  214.37  4982.9  211.81  4983.9  209.81  5016.1  209.81
  5017.1  211.81  5496.4  212.31  5588.2  214.39    5600   212.7  5644.6   213.4
  5666.1  215.18  5681.5  217.83  5726.1  228.82  5748.7  230.79  5778.4  230.83
#Mann= 3 ,-1 , 0
  4145.3     .15       0  4982.9    .045       0  5017.1     .15       0
Bank Sta=4982.9,5017.1
XS Rating Curve= 0 ,0
Exp/Cntr=0.3,0.1

Type RM Length L Ch R = 1 ,62100   ,500,500,500
BEGIN DESCRIPTION:
CEDAR CREEK 161.0
END DESCRIPTION:
XS GIS Cut Line= 3
      2052879.78       773305.81      2052050.01       773434.57
      2051299.02        773597.2
#Sta/Elev= 30
  4160.3  237.07  4241.7  228.07  4265.1  226.45  4279.7  223.23  4338.7  216.52
  4387.2  213.01  4446.6  213.53  4451.3  212.76  4492.3  214.84    4506  213.81
  4527.8  214.11  4539.7  212.54  4573.9  214.14  4618.9  213.54  4627.1  214.46
  4636.5  212.93    4699  213.27    4733  212.03  4787.7  212.81  4982.9  211.81
  4983.9  209.81  5016.1  209.81  5017.1  211.81  5376.1  212.32  5532.9  213.27
  5549.8  214.51  5554.6  213.88  5585.9  215.36  5641.9  225.17  5768.4  239.79
#Mann= 3 ,-1 , 0
  4160.3     .15       0  4982.9    .045       0  5017.1     .15       0
Bank Sta=4982.9,5017.1
XS Rating Curve= 0 ,0
Exp/Cntr=0.3,0.1

Type RM Length L Ch R = 1 ,61600   ,500,500,500
BEGIN DESCRIPTION:
CEDAR CREEK 160.0
END DESCRIPTION:
XS GIS Cut Line= 3
      2052802.04         772978.       2051662.7       773163.85
      2051398.53       773213.54
#Sta/Elev= 30
  3845.6  226.66  3876.7   223.8  3885.7  224.38  3927.4  222.43  3945.5  219.42
  3987.2  215.82  4039.8  212.89  4129.6   211.8  4195.8  212.57  4201.7  211.77
  4230.6  212.71  4279.5  211.85  4288.4  213.03  4405.9   211.7  4442.7  213.05
  4575.3  211.45  4713.8  211.51  4844.8  212.44  4917.2  211.83    4923  213.57
  4982.9  211.61  4983.9  209.61  5016.1  209.61  5017.1  211.61  5123.1  214.29
  5140.1  217.41  5175.8  226.25    5186  229.67  5242.3  241.68  5268.8  243.03
#Mann= 5 ,-1 , 0
  3845.6     .15       0  4713.8     .04       0    4923     .15       0
  4982.9    .045       0  5017.1     .15       0
Bank Sta=4982.9,5017.1
XS Rating Curve= 0 ,0
Exp/Cntr=0.3,0.1

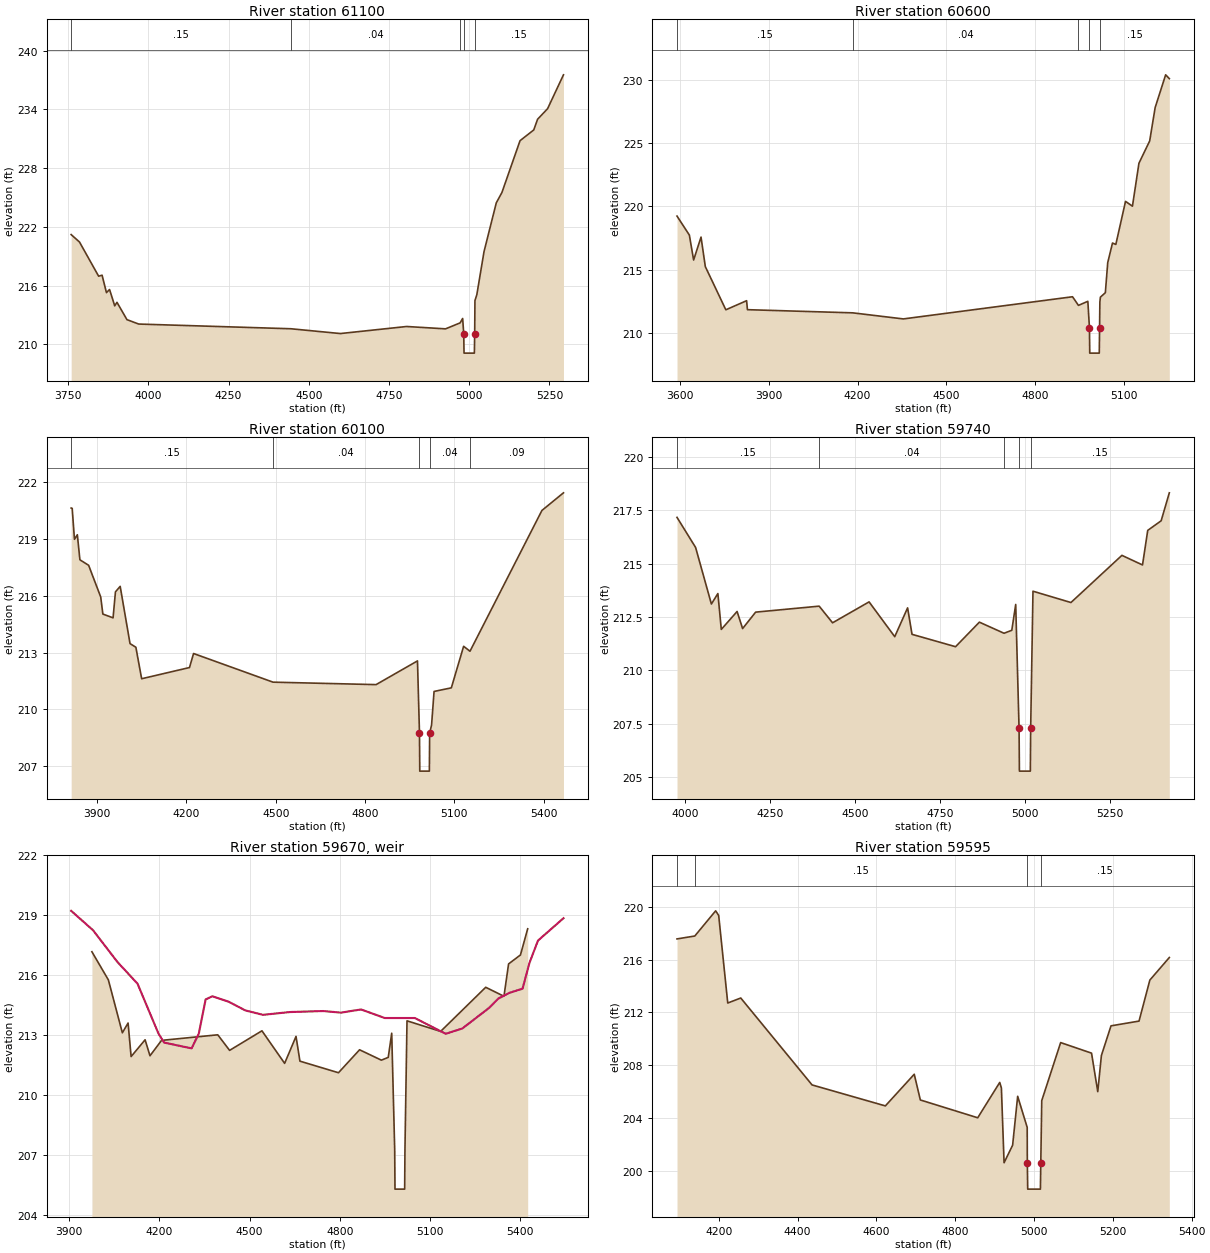
Type RM Length L Ch R = 1 ,61100   ,500,500,500
BEGIN DESCRIPTION:
CEDAR CREEK 159.0
END DESCRIPTION:
XS GIS Cut Line= 4
       2052692.8        772282.3      2051733.61       772605.26
      2051526.44       772701.66      2051296.49       772884.54
#Sta/Elev= 30
  3759.4  221.22  3785.4  220.46    3845  216.97  3855.8  217.07  3869.4  215.29
  3879.1  215.61  3895.2  213.94  3902.2   214.3  3933.3  212.53    3970  212.08
  4443.9   211.6  4598.5  211.11    4805  211.83  4926.3  211.59  4971.7   212.2
  4979.6  212.65  4982.9  211.11  4983.9  209.11  5016.1  209.11  5017.1  211.11
  5017.9  214.48  5023.8  215.08  5046.2  219.48  5084.4  224.46    5102  225.52
  5158.4  230.81  5201.2  231.91  5213.1     233  5244.3  234.08  5293.8  237.54
#Mann= 5 ,-1 , 0
  3759.4     .15       0  4443.9     .04       0  4971.7     .15       0
  4982.9    .045       0  5017.1     .15       0
Bank Sta=4982.9,5017.1
XS Rating Curve= 0 ,0
Exp/Cntr=0.3,0.1

Type RM Length L Ch R = 1 ,60600   ,500,500,500
BEGIN DESCRIPTION:
CEDAR CREEK 158.0
END DESCRIPTION:
XS GIS Cut Line= 4
      2052643.85       772220.34      2051604.92       772379.43
      2051246.27        772376.7      2050997.86       772330.87
#Sta/Elev= 30
  3590.3  219.23    3632  217.73  3646.4  215.76  3671.4  217.57  3685.9  215.24
  3755.2  211.83  3825.3  212.55  3828.1  211.84  4183.7  211.59  4354.4  211.11
  4925.8  212.86  4945.8  212.18  4977.5   212.5  4982.9  210.41  4983.9  208.41
  5016.1  208.41  5017.1  210.41  5018.1  212.44  5019.9  212.83  5036.6  213.18
  5044.6  215.55  5060.7   217.1    5072  216.99  5104.7  220.39  5128.1  220.01
    5150   223.4  5186.3  225.16  5204.8   227.8  5240.2  230.38  5252.6  230.08
#Mann= 5 ,-1 , 0
  3590.3     .15       0  4183.7     .04       0  4945.8     .09       0
  4982.9    .045       0  5017.1     .15       0
Bank Sta=4982.9,5017.1
XS Rating Curve= 0 ,0
Exp/Cntr=0.3,0.1

Type RM Length L Ch R = 1 ,60100   ,360,360,360
BEGIN DESCRIPTION:
CEDAR CREEK 157.0
END DESCRIPTION:
XS GIS Cut Line= 3
      2052683.11       772049.19      2051499.41       771958.15
      2051039.12       772034.62
#Sta/Elev= 30
  3812.8  220.62  3816.3   220.6  3823.9  218.97  3833.6  219.21  3842.2  217.89
  3871.5   217.6  3912.1  215.93  3919.3  215.03  3953.6  214.83  3961.6   216.2
  3977.5  216.49  4010.6  213.47  4030.2  213.28  4049.6  211.62  4210.3  212.21
    4224  212.95  4490.9  211.44  4837.1  211.31  4976.2  212.56  4982.9  208.75
  4983.9  206.75  5016.1  206.75  5017.1  208.75  5023.5  209.18  5031.9  210.95
  5089.9  211.14  5131.2  213.33  5152.6  213.07  5394.2  220.49  5466.6  221.42
#Mann= 5 ,-1 , 0
  3812.8     .15       0  4490.9     .04       0  4982.9    .045       0
  5017.1     .04       0  5152.6     .09       0
Bank Sta=4982.9,5017.1
XS Rating Curve= 0 ,0
Exp/Cntr=0.3,0.1

Type RM Length L Ch R = 1 ,59740   ,145,145,145
BEGIN DESCRIPTION:
CDC_Dam (2)-US
END DESCRIPTION:
XS GIS Cut Line= 6
      2052612.38       771916.35      2052363.34       771738.46
      2052009.25       771667.31      2051731.55       771723.36
      2051635.65       771672.29      2051261.68       771753.92
#Sta/Elev= 30
  3975.1  217.17  4029.9  215.76  4076.4  213.11  4095.5   213.6  4105.6  211.92
  4152.1  212.76  4168.4  211.96  4206.8  212.73    4394  213.01  4433.4  212.23
    4541  213.21  4616.6  211.58  4654.5  212.93  4667.5  211.69  4795.8  211.11
    4866  212.26  4938.6  211.74  4961.5  211.88    4973  213.09  4982.9  207.28
  4983.9  205.28  5016.1  205.28  5017.1  207.28  5023.9  213.71  5135.8  213.18
  5285.9  215.39  5346.6  214.94    5362  216.56  5401.5  217.01  5425.6  218.32
#Mann= 5 ,-1 , 0
  3975.1     .15       0    4394     .04       0  4938.6     .15       0
  4982.9    .045       0  5017.1     .15       0
Bank Sta=4982.9,5017.1
XS Rating Curve= 0 ,0
Exp/Cntr=0.3,0.1

Type RM Length L Ch R = 5 ,59670   ,,,
BEGIN DESCRIPTION:
CDC_Dam (2)-TOR
Structure ID: LDS 266
Approximate Survey Structure
END DESCRIPTION:
IW Pilot Flow=0
#Inline Weir SE= 28
    3906  219.22  3978.7  218.25  4059.9  216.66  4126.9  215.57  4196.7  213.07
  4215.6  212.62  4306.9  212.33  4330.9  213.07  4353.6  214.78  4375.9  214.94
  4429.8  214.67    4486  214.23  4544.4  214.01  4633.9  214.15  4744.8   214.2
  4804.5  214.12  4870.8  214.28    4950  213.85    5050  213.85  5152.7  213.06
  5208.4  213.33  5297.3  214.36  5328.4  214.83  5364.5  215.11  5408.5  215.32
  5431.4  216.61  5459.9  217.73  5544.7  218.85
IW Dist,WD,Coef,Skew,MaxSub,Min_El,Is_Ogee,SpillHt,DesHd
61,18,3,0,0.95,, 0 ,,,1,1,

Type RM Length L Ch R = 1 ,59595   ,165,165,165
BEGIN DESCRIPTION:
CDC_Dam (2)-DS
END DESCRIPTION:
XS GIS Cut Line= 6
      2052663.83       771706.51      2052314.94       771614.38
      2052179.25       771619.95      2052047.11       771573.87
      2051782.01       771599.51      2051477.58       771440.84
#Sta/Elev= 30
  4093.8  217.57  4138.9  217.79  4191.9   219.7  4199.6  219.35  4222.6  212.71
  4255.6  213.09  4436.6   206.5  4622.6  204.91  4695.9  207.31  4711.4  205.36
    4857  204.01  4912.9  206.69  4917.1  206.27  4923.9   200.6  4945.6  201.93
  4958.4  205.64  4982.6  203.28  4982.9   200.6  4983.9   198.6  5016.1   198.6
  5017.1   200.6  5019.5  205.31  5067.5  209.71  5145.9  208.91  5161.7  205.99
  5170.9  208.73  5195.3  210.98  5266.4  211.34  5293.9  214.45  5343.3  216.16
#Mann= 4 ,-1 , 0
  4093.8     .04       0  4138.9     .15       0  4982.9    .045       0
  5017.1     .15       0
Bank Sta=4982.9,5017.1
XS Rating Curve= 0 ,0
Exp/Cntr=0.3,0.1

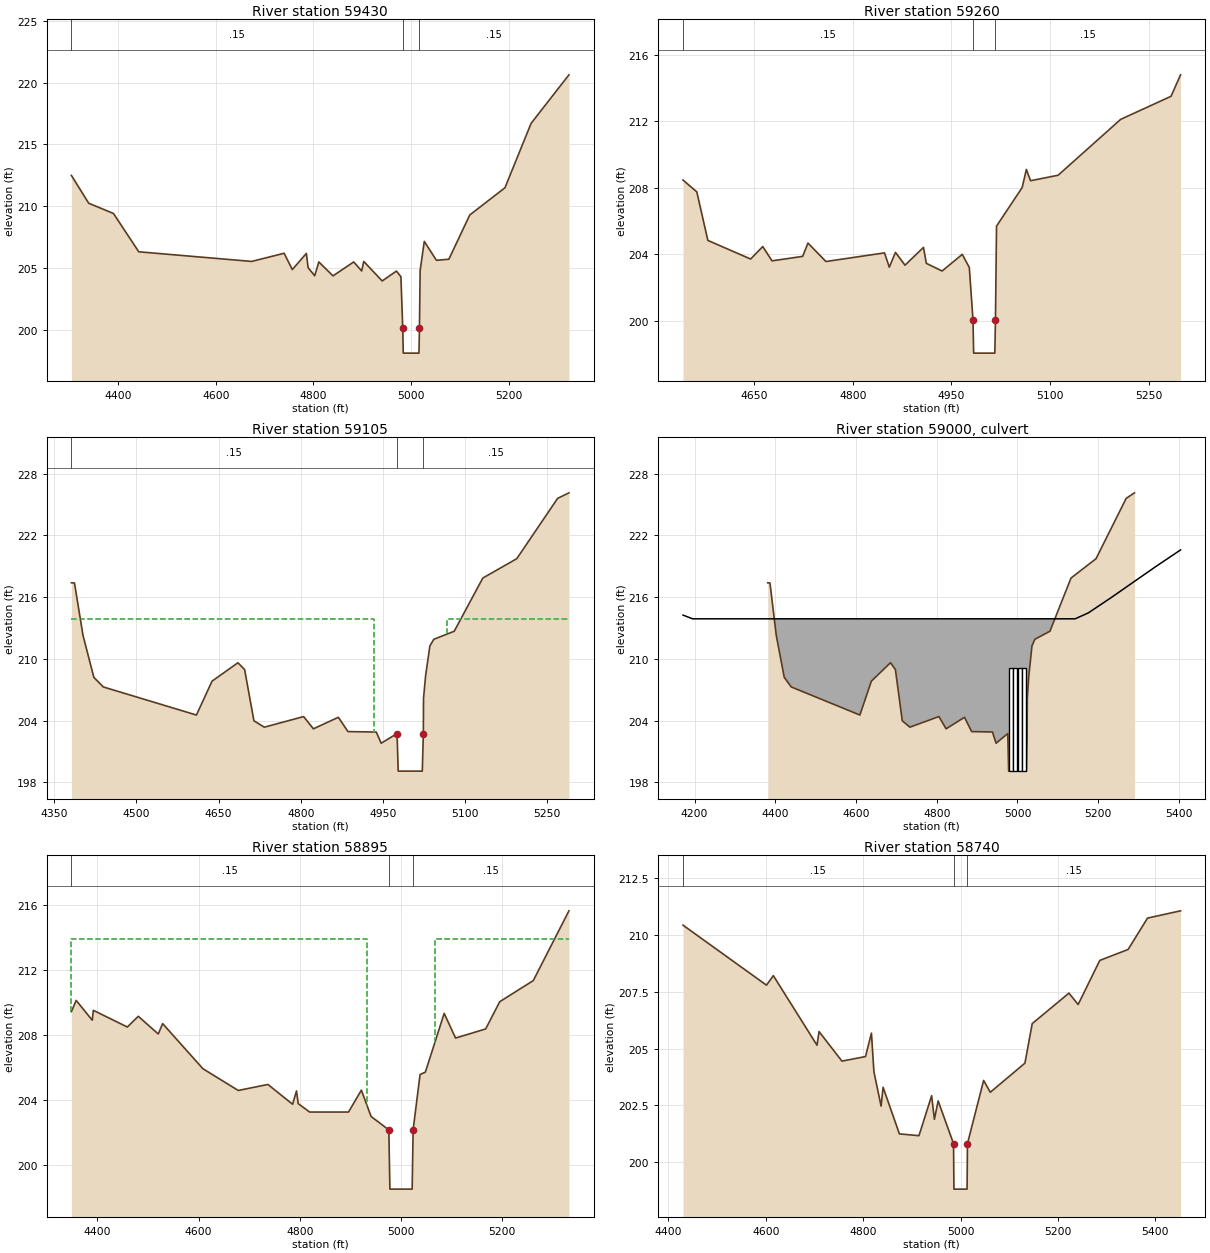
Type RM Length L Ch R = 1 ,59430   ,170,170,170
BEGIN DESCRIPTION:
CEDAR CREEK 153.0
END DESCRIPTION:
XS GIS Cut Line= 4
      2052502.61       771630.05      2052176.94       771482.76
      2051840.17       771447.89      2051534.42       771342.52
#Sta/Elev= 30
    4304  212.49  4339.4  210.24  4390.2  209.41    4442  206.31  4673.2  205.53
  4739.8  206.19  4756.6  204.87  4785.4  206.18    4789  205.02  4802.5  204.37
  4810.9  205.49    4840  204.36  4882.4  205.49  4898.7  204.76    4903  205.53
  4940.7  203.95    4970  204.75  4979.1  204.29  4982.9  200.11  4983.9  198.11
  5016.1  198.11  5017.1  200.11  5018.5  204.79    5027  207.15  5051.9  205.62
  5077.4  205.71  5120.2  209.29  5192.3  211.49  5245.8   216.7  5323.4  220.63
#Mann= 3 ,-1 , 0
    4304     .15       0  4982.9    .045       0  5017.1     .15       0
Bank Sta=4982.9,5017.1
XS Rating Curve= 0 ,0
Exp/Cntr=0.3,0.1

Type RM Length L Ch R = 1 ,59260   ,155,155,155
BEGIN DESCRIPTION:
CEDAR CREEK 152.0
END DESCRIPTION:
XS GIS Cut Line= 3
       2052340.6       771282.54       2051882.4       771283.24
      2051587.93       771233.77
#Sta/Elev= 30
  4541.8  208.47  4562.8  207.76  4579.6  204.84  4644.7  203.72  4663.1  204.47
  4677.2  203.61  4723.8  203.88  4731.9  204.68  4759.2  203.57  4848.3  204.09
  4855.6  203.23    4865  204.12  4879.5  203.35  4907.6  204.42  4911.9  203.46
  4935.9     203  4966.6     204  4977.3  203.21  4982.9  200.06  4983.9  198.06
  5016.1  198.06  5017.1  200.06  5018.7   205.7  5057.7  208.02  5064.1  209.11
  5070.5  208.43  5112.4  208.76  5207.5  212.12  5284.2  213.51  5298.6   214.8
#Mann= 3 ,-1 , 0
  4541.8     .15       0  4982.9    .045       0  5017.1     .15       0
Bank Sta=4982.9,5017.1
XS Rating Curve= 0 ,0
Exp/Cntr=0.5,0.3

Type RM Length L Ch R = 1 ,59105   ,210,210,210
BEGIN DESCRIPTION:
CDC_Garners Ferry Rd-US
END DESCRIPTION:
XS GIS Cut Line= 3
      2052565.21       771110.03      2051947.49       771144.75
      2051657.99       771129.54
#Sta/Elev= 30
  4381.3   217.4  4386.9  217.38  4402.5  212.28  4422.3  208.21  4439.5  207.28
  4609.6  204.55  4638.1  207.84  4685.4  209.63  4697.6  208.97  4714.6  203.99
  4733.6  203.37  4805.4   204.4  4823.2  203.21  4868.8  204.33  4886.4  202.94
    4938   202.9    4947  201.81    4976  202.75  4978.1   199.1  5022.1   199.1
    5024  202.75  5024.3  206.16  5028.2  208.39  5035.9  211.26  5043.1  211.91
  5080.4  212.69  5132.6  217.86  5194.6  219.74  5269.2   225.6  5289.9  226.14
#Mann= 3 ,-1 , 0
  4381.3     .15       0    4976    .045       0    5024     .15       0
#XS Ineff= 2 , 0
       0  4933.5   213.9  5066.5       0   213.9
Permanent Ineff=
       F       F
Bank Sta=4976,5024
XS Rating Curve= 0 ,0
Exp/Cntr=0.5,0.3

Type RM Length L Ch R = 2 ,59000   ,,,
BEGIN DESCRIPTION:
CDC_Garners Ferry Rd-TOR
Structure ID: LDS 268
Approximate Survey Structure
END DESCRIPTION:
Bridge Culvert--1,0,-1,-1, 0
Deck Dist Width WeirC Skew NumUp NumDn MinLoCord MaxHiCord MaxSubmerge Is_Ogee
45,120,3,0, 7, 7, , , 0.95, 0, 1,1,,
  4171.5  4195.1  5142.9  5175.3  5230.6  5343.1  5403.9
  214.26   213.9   213.9  214.47  215.92  218.99  220.59
   179.1   179.1   179.1   179.1   179.1   179.1   179.1
  4171.5  4195.1  5142.9  5175.3  5230.6  5343.1  5403.9
  214.26   213.9   213.9  214.47  215.92  218.99  220.59
   178.5   178.5   178.5   178.5   178.5   178.5   178.5
BR Coef= 1 , 1 , 0 ,1.25, 0 ,,,0.8,0,2,0,
WSPro=,,,, 1 ,,,, 0 ,,,, 0 ,,,,-1 ,-1 ,-1 , 0 , 0 , 0 , 0 , 0
Culvert=2,10,10,120,0.012,0.4,1,8,1,199.1,4983.5,198.5,4983.5,Culvert #1  , 0 ,45
Culvert Bottom n=0.012
Culvert=2,10,10,120,0.012,0.4,1,8,1,199.1,4994.5,198.5,4994.5,Culvert #2  , 0 ,45
Culvert Bottom n=0.012
Culvert=2,10,10,120,0.012,0.4,1,8,1,199.1,5005.5,198.5,5005.5,Culvert #3  , 0 ,45
Culvert Bottom n=0.012
Culvert=2,10,10,120,0.012,0.4,1,8,1,199.1,5016.5,198.5,5016.5,Culvert #4  , 0 ,45
Culvert Bottom n=0.012
BC Design=,, 0 ,, 0 ,,,,,,
BC HTab HWMax=226.14
BC Use User HTab Curves=0
BC User HTab FreeFlow(D)= 0

Type RM Length L Ch R = 1 ,58895   ,155,155,155
BEGIN DESCRIPTION:
CDC_Garners Ferry Rd-DS
END DESCRIPTION:
XS GIS Cut Line= 4
      2052705.67       770888.93      2052269.27       770961.66
      2052060.38       770967.83      2051729.98       770935.33
#Sta/Elev= 30
  4348.6  209.44    4358  210.13  4389.8  208.91  4391.9  209.52  4459.1  208.49
  4480.8  209.15  4520.3  208.06  4528.9   208.7  4608.5  205.92  4678.4  204.58
    4737  204.95  4785.8  203.73  4793.5  204.55  4796.9  203.77  4819.5  203.25
  4896.3  203.25  4921.7   204.6  4940.9  202.98    4976  202.15  4978.1   198.5
  5022.1   198.5    5024  202.15  5037.7  205.56  5048.2  205.71  5085.4  209.33
  5107.9  207.81  5167.4  208.37  5195.2  210.05  5261.5  211.35    5332  215.65
#Mann= 3 ,-1 , 0
  4348.6     .15       0    4976    .045       0    5024     .15       0
#XS Ineff= 2 , 0
       0  4933.5   213.9  5066.5       0   213.9
Permanent Ineff=
       F       F
Bank Sta=4976,5024
XS Rating Curve= 0 ,0
Exp/Cntr=0.5,0.3

Type RM Length L Ch R = 1 ,58740   ,380,380,380
BEGIN DESCRIPTION:
CEDAR CREEK 148.0
END DESCRIPTION:
XS GIS Cut Line= 3
       2052717.2       770840.18       2052147.3       770839.51
      2051719.48       770693.98
#Sta/Elev= 30
  4430.1  210.43  4601.6  207.79  4615.6  208.21  4705.3  205.15  4709.5  205.75
  4756.5  204.45  4804.9  204.65  4817.1  205.68  4822.2  203.98  4836.9  202.47
    4841   203.3  4874.5  201.25  4914.7  201.17  4940.7  202.93  4946.4  201.89
  4954.1   202.7  4985.7  200.82  4986.5  198.82  5013.5  198.82  5014.3  200.82
  5047.5   203.6  5061.2  203.08  5132.3  204.36  5147.3   206.1  5222.7  207.44
  5241.6  206.94  5286.1  208.88  5344.2  209.36  5384.1  210.74  5451.9  211.06
#Mann= 3 ,-1 , 0
  4430.1     .15       0  4985.7    .045       0  5014.3     .15       0
Bank Sta=4985.7,5014.3
XS Rating Curve= 0 ,0
Exp/Cntr=0.3,0.1

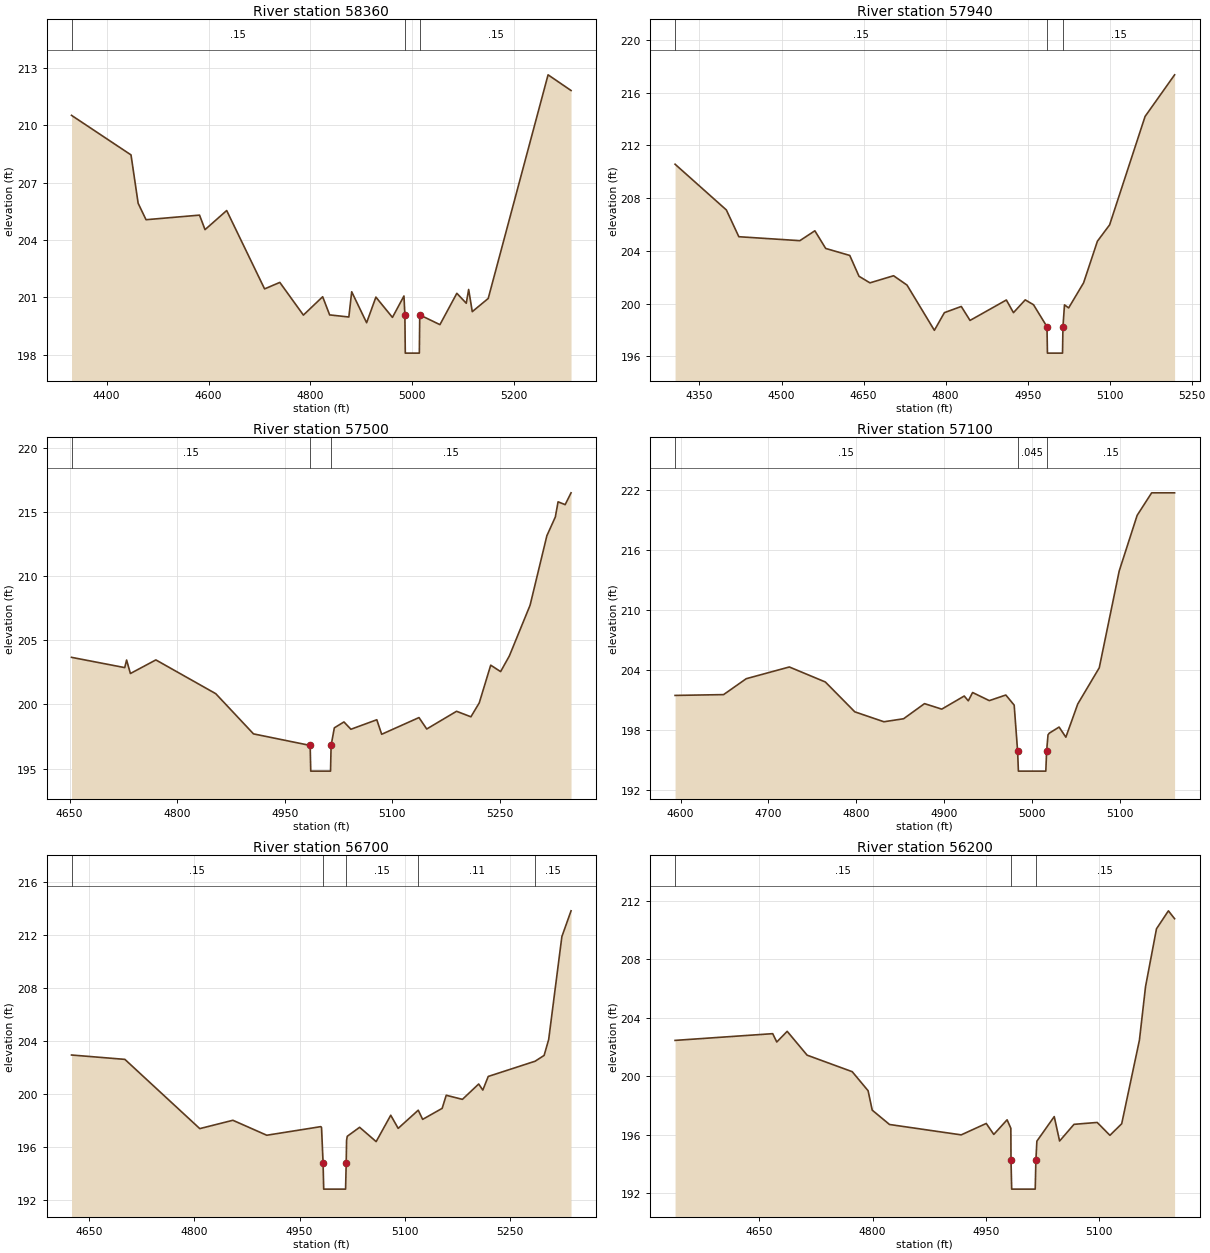
Type RM Length L Ch R = 1 ,58360   ,420,420,420
BEGIN DESCRIPTION:
CEDAR CREEK 147.0
END DESCRIPTION:
XS GIS Cut Line= 3
      2052794.23       770361.06      2052135.86       770479.84
      2051827.69       770525.99
#Sta/Elev= 30
    4331  210.52  4447.8  208.45  4461.8  205.92  4477.3  205.06  4582.3   205.3
  4593.1  204.54  4635.6  205.54    4710  201.44  4739.9  201.78  4786.2  200.07
    4824  201.03  4837.7  200.08  4875.4  199.97    4881  201.29  4910.3  199.67
  4928.5  201.01    4961  199.95  4983.6  201.07  4985.4  200.08  4986.2  198.08
  5013.8  198.08  5014.6  200.08  5054.2  199.57  5087.4  201.21  5105.9  200.69
  5110.6  201.41  5117.7  200.25    5149  200.94  5266.5  212.64  5311.6  211.82
#Mann= 3 ,-1 , 0
    4331     .15       0  4985.4    .045       0  5014.6     .15       0
Bank Sta=4985.4,5014.6
XS Rating Curve= 0 ,0
Exp/Cntr=0.3,0.1

Type RM Length L Ch R = 1 ,57940   ,440,440,440
BEGIN DESCRIPTION:
CEDAR CREEK 146.0
END DESCRIPTION:
XS GIS Cut Line= 3
      2052749.72       770227.54      2052056.39       770185.45
      2051838.35       770202.38
#Sta/Elev= 30
  4305.4  210.57  4399.2   207.1    4422  205.07  4533.6  204.77    4561  205.52
  4580.8  204.18  4624.8  203.65  4641.7  202.07  4661.7  201.57  4704.9  202.11
  4729.5   201.4  4779.5  197.97  4797.8  199.31  4828.7  199.78  4844.7  198.72
  4911.1  200.27  4924.1  199.31  4945.6  200.28  4960.8  199.91  4985.4  198.24
  4986.2  196.24  5013.8  196.24  5014.6  198.24  5017.4   199.9    5025  199.67
  5052.3  201.57  5077.6  204.73  5099.9  205.97  5164.7  214.19  5218.7  217.35
#Mann= 3 ,-1 , 0
  4305.4     .15       0  4985.4    .045       0  5014.6     .15       0
Bank Sta=4985.4,5014.6
XS Rating Curve= 0 ,0
Exp/Cntr=0.3,0.1

Type RM Length L Ch R = 1 ,57500   ,400,400,400
BEGIN DESCRIPTION:
CEDAR CREEK 145.0
END DESCRIPTION:
XS GIS Cut Line= 3
      2052639.48       769929.54      2052298.51       769863.53
      2051952.54       769910.18
#Sta/Elev= 30
  4652.7  203.67  4726.9  202.87  4729.5  203.46  4734.8  202.41  4770.3  203.47
  4853.8  200.84  4906.4  197.71  4985.4  196.81  4986.2  194.81  5013.8  194.81
  5014.6  196.81  5019.1  198.18  5032.5  198.64  5042.2  198.07  5078.3  198.81
  5085.1  197.68  5137.1  198.98  5147.9  198.09  5189.5  199.47  5209.5  199.04
  5221.1  200.12  5237.1  203.06  5250.9  202.56  5263.1  203.78    5292  207.73
  5315.4  213.14  5327.2   214.6    5331  215.78  5340.9  215.56  5349.1  216.48
#Mann= 3 ,-1 , 0
  4652.7     .15       0  4985.4    .045       0  5014.6     .15       0
Bank Sta=4985.4,5014.6
XS Rating Curve= 0 ,0
Exp/Cntr=0.3,0.1

Type RM Length L Ch R = 1 ,57100   ,400,400,400
BEGIN DESCRIPTION:
CEDAR CREEK 144.0
END DESCRIPTION:
XS GIS Cut Line= 3
      2052600.69       769478.67      2052199.12       769539.79
      2052037.68       769525.11
#Sta/Elev= 30
  4593.8  201.45    4649  201.53  4674.8  203.12  4723.8  204.29  4764.8  202.79
  4798.3  199.81  4831.4  198.82  4853.8  199.12  4877.6  200.63  4897.2  200.08
  4922.8  201.39  4927.4  200.91  4932.3  201.74  4951.3  200.93  4970.1  201.49
  4979.6  200.48  4983.5  195.89  4984.4  193.89  5015.6  193.89  5016.5  195.89
  5018.1  197.51  5019.5  197.68  5030.7  198.29  5038.4  197.28  5051.9  200.59
  5076.4  204.21  5099.1  213.88  5119.5  219.43    5136  221.68  5162.1  221.68
#Mann= 3 ,-1 , 0
  4593.8     .15       0  4983.5    .045       0  5016.5     .15       0
Bank Sta=4983.5,5016.5
XS Rating Curve= 0 ,0
Exp/Cntr=0.3,0.1

Type RM Length L Ch R = 1 ,56700   ,500,500,500
BEGIN DESCRIPTION:
CEDAR CREEK 143.0
END DESCRIPTION:
XS GIS Cut Line= 3
      2052662.63       769338.55      2052329.09       769166.72
      2052039.54        768994.1
#Sta/Elev= 30
  4624.8  202.94  4700.9  202.61  4807.7  197.38  4854.9  198.01  4903.2  196.88
  4980.3  197.53  4981.3  197.47  4983.5  194.81  4984.4  192.81  5015.6  192.81
  5016.5  194.81    5017  196.49    5018   196.8  5035.6  197.48  5059.2   196.4
    5080  198.39  5090.6   197.4  5119.2  198.77  5125.5  198.08  5153.3  198.91
  5159.1   199.9  5182.2  199.59  5205.4  200.75  5211.3  200.29    5219  201.32
  5285.8  202.47  5298.7  202.91  5305.2  204.11    5324  211.88  5337.1  213.83
#Mann= 5 ,-1 , 0
  4624.8     .15       0  4983.5    .045       0  5016.5     .15       0
  5119.2     .11       0  5285.8     .15       0
Bank Sta=4983.5,5016.5
XS Rating Curve= 0 ,0
Exp/Cntr=0.3,0.1

Type RM Length L Ch R = 1 ,56200   ,500,500,500
BEGIN DESCRIPTION:
CEDAR CREEK 142.0
END DESCRIPTION:
XS GIS Cut Line= 3
      2052908.41       768986.37      2052532.97       768717.65
      2052364.67       768609.05
#Sta/Elev= 30
  4538.3  202.44  4667.7   202.9  4673.1  202.33  4686.9  203.06  4713.3  201.43
  4773.1   200.3  4794.1     199  4799.6  197.67  4822.5  196.69  4917.5  195.98
  4950.7  196.76  4960.7  196.01  4978.3  197.01  4983.3  196.43  4983.5  194.27
  4984.4  192.27  5015.6  192.27  5016.5  194.27  5017.8  195.55  5040.8  197.23
  5047.9  195.56    5067   196.7  5097.7  196.83  5114.6  195.95  5130.2  196.74
  5153.7  202.46  5161.8  206.12  5176.3  210.07  5192.1   211.3  5200.3  210.76
#Mann= 3 ,-1 , 0
  4538.3     .15       0  4983.5    .045       0  5016.5     .15       0
Bank Sta=4983.5,5016.5
XS Rating Curve= 0 ,0
Exp/Cntr=0.3,0.1