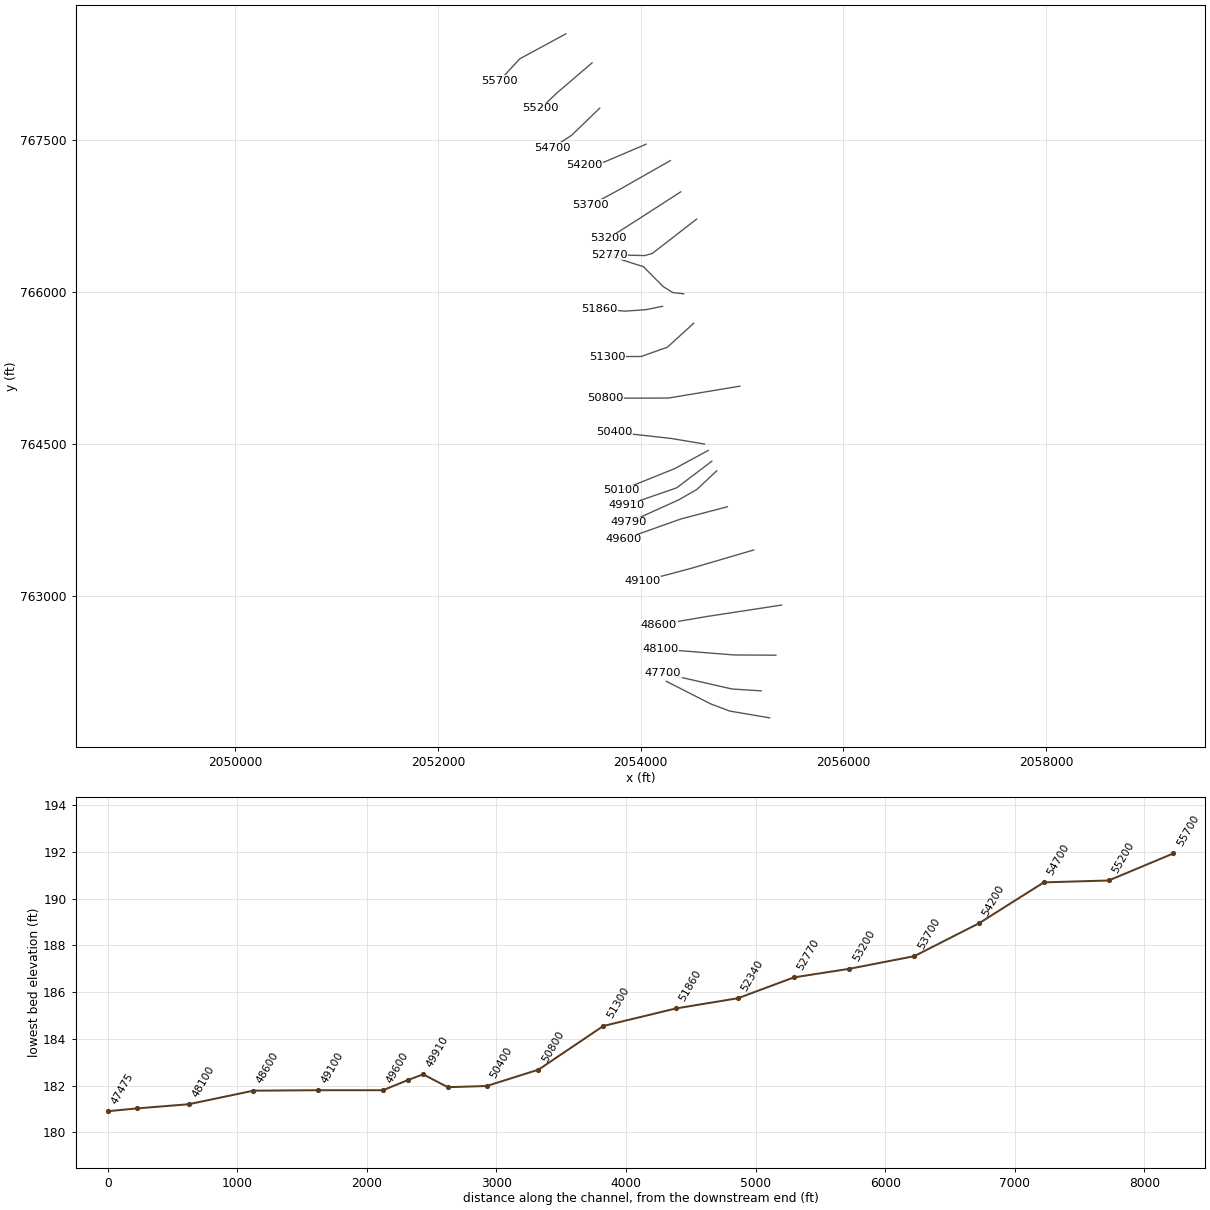
HEC-RAS study Cedar Creek.prj: Cedar Creek Limited Detail Study

--- Cedar Creek.g04 (geometry) --- (continued)

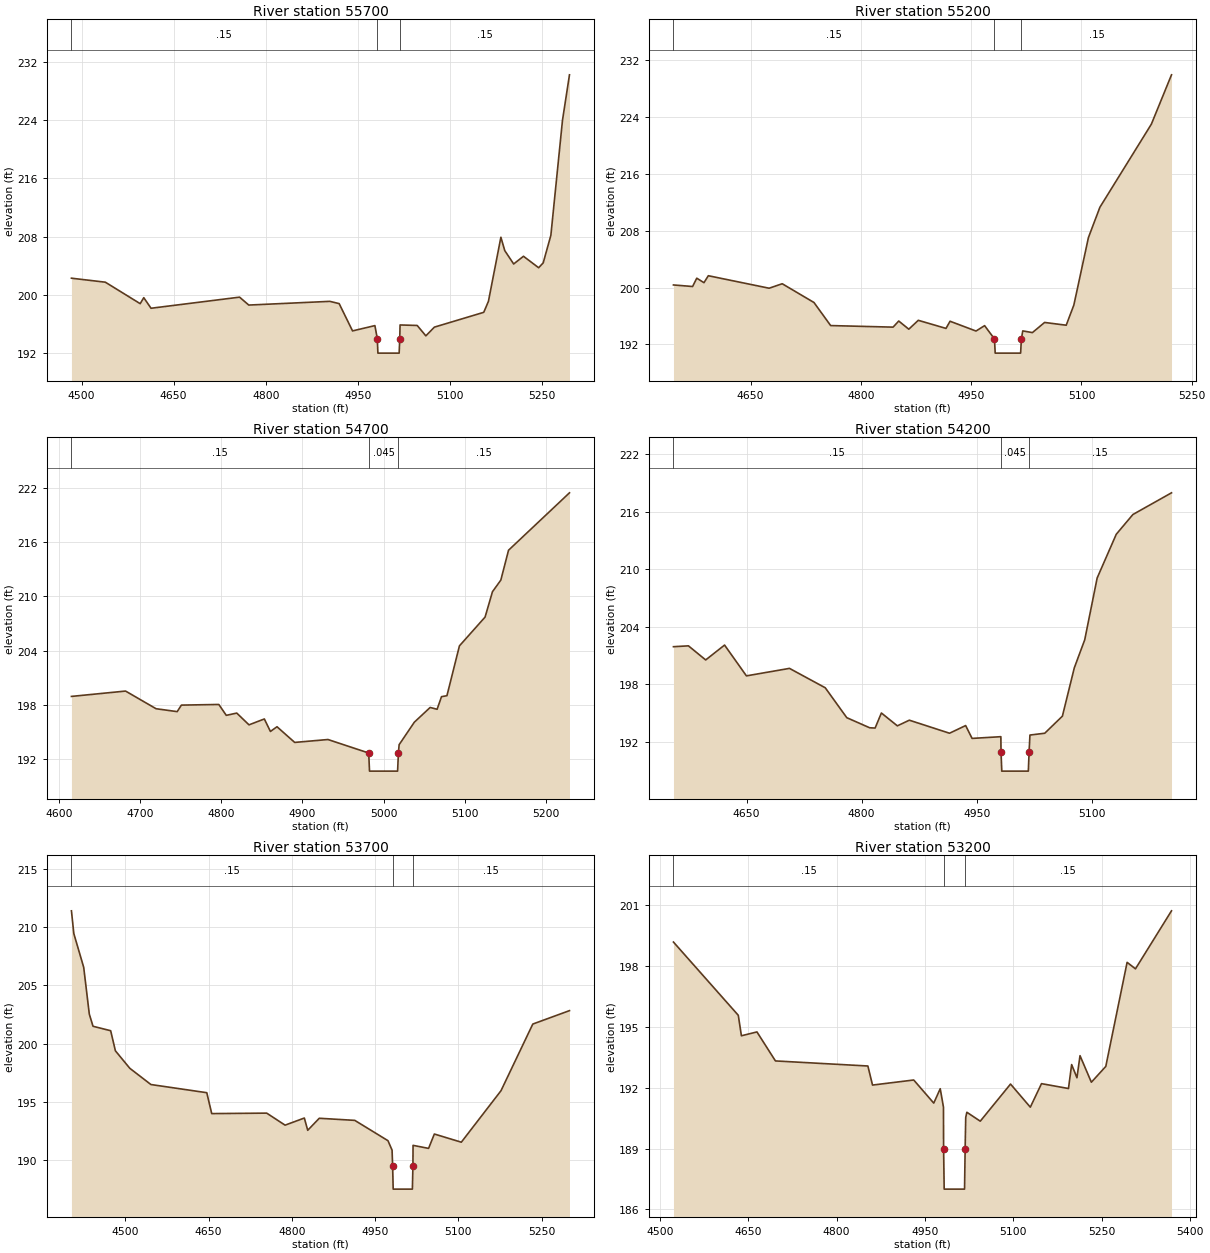
Type RM Length L Ch R = 1 ,55700   ,500,500,500
BEGIN DESCRIPTION:
CEDAR CREEK 141.0
END DESCRIPTION:
XS GIS Cut Line= 3
       2053262.5       768548.07      2052808.51       768301.96
      2052608.45       768085.57
#Sta/Elev= 30
  4483.6  202.26  4538.8  201.71  4595.6  198.75  4601.4  199.58  4613.2  198.12
  4757.4  199.65  4772.4  198.56  4904.4  199.07  4919.6  198.76  4941.4     195
  4977.8  195.73  4981.7  193.94  4982.7  191.94  5017.3  191.94  5018.3  193.94
  5018.8  195.82  5046.7  195.75  5060.8  194.32  5074.7  195.52  5155.1  197.56
  5162.7  199.07    5183   207.9  5189.3  206.06  5203.8  204.22  5219.8  205.28
  5244.5   203.7  5251.9  204.37  5264.4  208.17  5283.3     224  5294.7  230.27
#Mann= 3 ,-1 , 0
  4483.6     .15       0  4981.7    .045       0  5018.3     .15       0
Bank Sta=4981.7,5018.3
XS Rating Curve= 0 ,0
Exp/Cntr=0.3,0.1

Type RM Length L Ch R = 1 ,55200   ,500,500,500
BEGIN DESCRIPTION:
CEDAR CREEK 140.0
END DESCRIPTION:
XS GIS Cut Line= 3
      2053521.86        768262.3      2053176.26       767966.51
      2053014.86       767813.36
#Sta/Elev= 30
  4545.1  200.38  4571.1  200.16  4576.8  201.33  4586.6   200.7  4592.5  201.68
  4675.2  199.92    4693  200.55  4736.2  197.91  4758.9  194.66  4843.8  194.44
  4851.5   195.3  4865.2  194.15  4878.1   195.4  4915.8  194.26  4921.3  195.27
  4956.6  193.89  4968.3  194.65  4981.7  192.78  4982.7  190.78  5017.3  190.78
  5018.3  192.78  5020.2  193.91  5033.3  193.67  5049.9   195.1  5079.3  194.71
  5089.7  197.56  5109.5  207.05  5125.1  211.32  5195.1  223.02  5222.5  229.97
#Mann= 3 ,-1 , 0
  4545.1     .15       0  4981.7    .045       0  5018.3     .15       0
Bank Sta=4981.7,5018.3
XS Rating Curve= 0 ,0
Exp/Cntr=0.3,0.1

Type RM Length L Ch R = 1 ,54700   ,500,500,500
BEGIN DESCRIPTION:
CEDAR CREEK 139.0
END DESCRIPTION:
XS GIS Cut Line= 3
      2053597.29       767815.26      2053320.43        767548.3
        2053129.       767422.45
#Sta/Elev= 30
  4615.4  198.95  4682.1  199.54  4719.7  197.59  4745.7  197.27  4750.9  197.99
    4797  198.06  4806.2  196.86  4819.1  197.11  4834.2  195.81  4853.1  196.46
  4860.6  195.08  4868.7   195.6  4890.5  193.87  4931.5  194.19  4981.7   192.7
  4982.7   190.7  5017.3   190.7  5018.3   192.7  5019.2  193.62  5037.9   196.1
  5057.4  197.73    5066  197.53  5071.4  198.92  5078.1  199.03  5093.5  204.53
  5125.1  207.71  5134.2  210.51  5144.5  211.79    5154  215.09  5229.1  221.43
#Mann= 3 ,-1 , 0
  4615.4     .15       0  4981.7    .045       0  5018.3     .15       0
Bank Sta=4981.7,5018.3
XS Rating Curve= 0 ,0
Exp/Cntr=0.3,0.1

Type RM Length L Ch R = 1 ,54200   ,500,500,500
BEGIN DESCRIPTION:
CEDAR CREEK 138.0
END DESCRIPTION:
XS GIS Cut Line= 3
      2054054.02       767459.24      2053644.37       767284.91
      2053442.52       767256.05
#Sta/Elev= 30
  4554.8  201.92  4574.3  202.01  4596.8  200.54  4621.4  202.09  4649.9  198.88
    4706  199.66  4752.6  197.64  4780.7  194.52  4810.5  193.47  4817.6  193.44
  4825.8  195.01  4846.6  193.67  4862.2  194.26  4914.6   192.9  4935.6   193.7
    4944  192.36  4981.5  192.54  4981.7  190.95  4982.7  188.95  5017.3  188.95
  5018.3  190.95  5019.4  192.71  5038.7   192.9  5061.7  194.68  5077.2  199.71
  5090.8  202.64    5107  209.08  5131.9  213.64  5153.6   215.7  5203.9  217.96
#Mann= 3 ,-1 , 0
  4554.8     .15       0  4981.7    .045       0  5018.3     .15       0
Bank Sta=4981.7,5018.3
XS Rating Curve= 0 ,0
Exp/Cntr=0.3,0.1

Type RM Length L Ch R = 1 ,53700   ,500,500,500
BEGIN DESCRIPTION:
CEDAR CREEK 137.0
END DESCRIPTION:
XS GIS Cut Line= 3
      2054293.96       767297.66      2053774.76       767002.77
      2053510.27       766860.34
#Sta/Elev= 30
  4402.9  211.38  4407.2  209.43    4425  206.54  4435.1  202.53  4441.8  201.49
  4473.6  201.11  4482.1  199.39  4508.1  197.89  4546.1   196.5  4646.8   195.8
  4655.7  194.01  4754.8  194.05  4787.9  193.02  4822.6  193.63  4828.7  192.58
  4849.5  193.61  4913.5  193.43  4973.3  191.69  4980.7  190.88  4981.7  189.54
  4982.7  187.54  5017.3  187.54  5018.3  189.54  5018.5  191.29  5046.5  191.03
  5056.9  192.26  5105.5  191.56    5177  195.97  5234.3  201.68  5300.4  202.83
#Mann= 3 ,-1 , 0
  4402.9     .15       0  4981.7    .045       0  5018.3     .15       0
Bank Sta=4981.7,5018.3
XS Rating Curve= 0 ,0
Exp/Cntr=0.3,0.1

Type RM Length L Ch R = 1 ,53200   ,430,430,430
BEGIN DESCRIPTION:
CEDAR CREEK 136.0
END DESCRIPTION:
XS GIS Cut Line= 3
      2054396.45       766989.94      2053995.83       766730.86
       2053684.4       766533.31
#Sta/Elev= 30
  4522.9  199.18    4633  195.57  4638.3  194.56  4664.7  194.75  4696.1  193.32
  4853.1  193.07    4861  192.13    4931  192.38    4965  191.24    4976  191.95
  4981.5  191.04  4981.7     189  4982.7     187  5017.3     187  5018.3     189
  5019.3  190.53  5021.2  190.79    5044  190.35  5095.4  192.18    5129  191.04
    5148   192.2  5193.8  191.96  5199.2  193.14  5208.2  192.49  5213.4  193.58
  5232.7  192.27  5257.2  193.05  5293.4  198.18  5307.6  197.86  5368.8  200.72
#Mann= 3 ,-1 , 0
  4522.9     .15       0  4981.7    .045       0  5018.3     .15       0
Bank Sta=4981.7,5018.3
XS Rating Curve= 0 ,0
Exp/Cntr=0.3,0.1

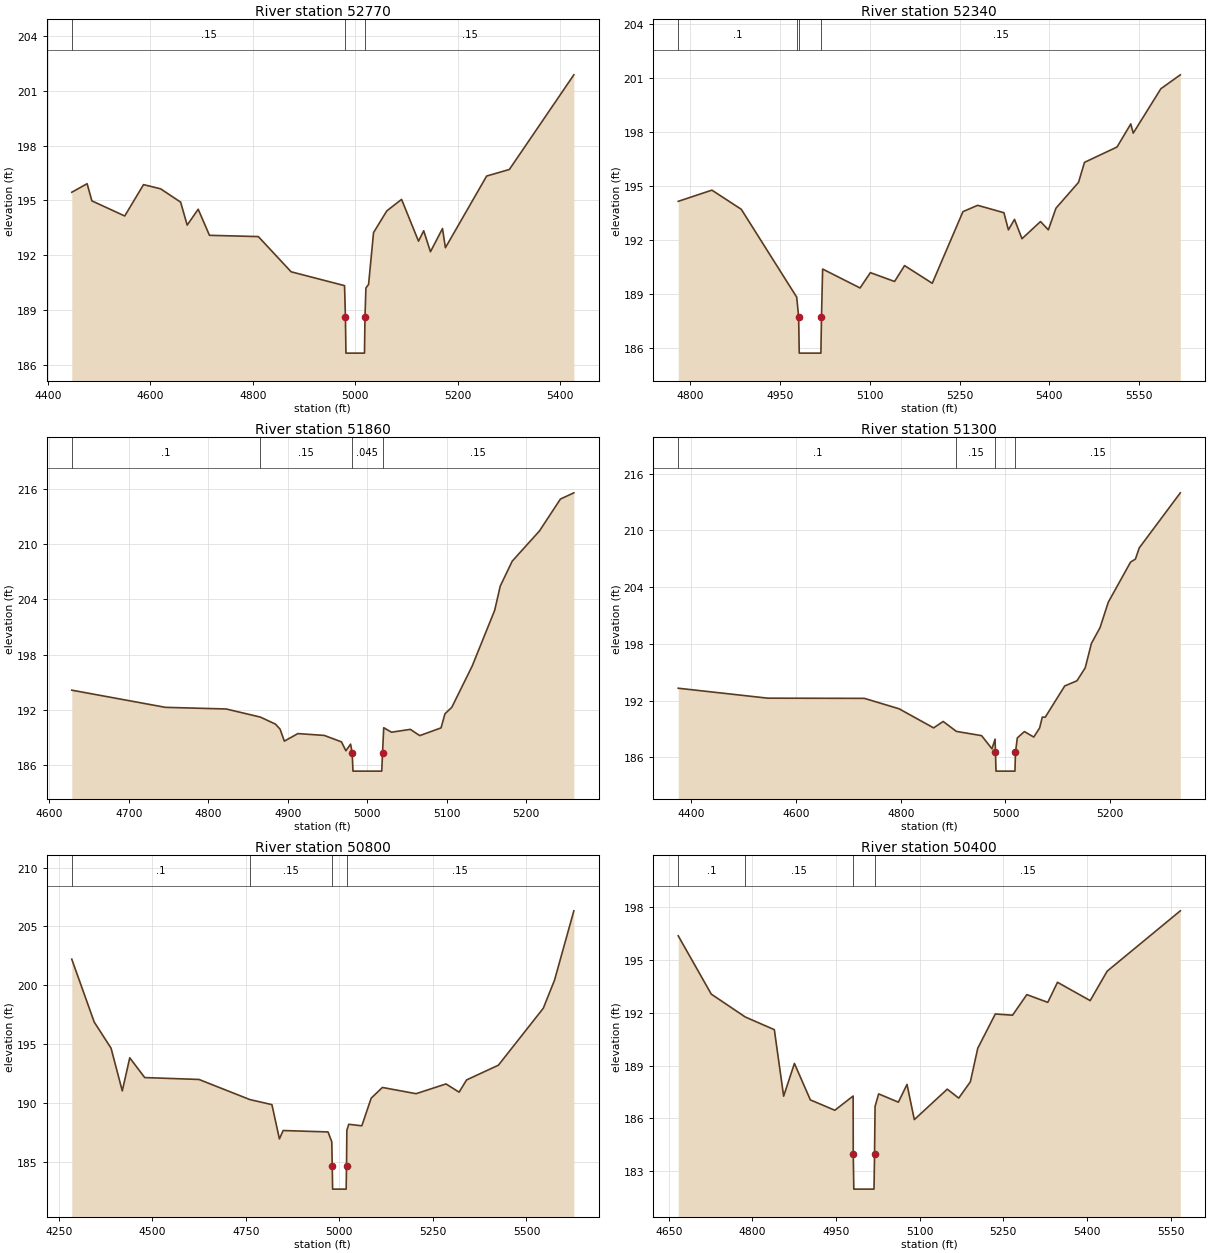
Type RM Length L Ch R = 1 ,52770   ,430,430,430
BEGIN DESCRIPTION:
CEDAR CREEK 135.0
END DESCRIPTION:
XS GIS Cut Line= 4
      2054553.21       766720.98      2054115.91         766382.
      2054042.37       766361.07      2053692.12       766368.81
#Sta/Elev= 30
  4446.7  195.45  4476.7  195.92  4485.9  194.98  4550.1  194.15  4586.8  195.87
  4620.1  195.64  4659.2  194.91    4672  193.65  4693.5  194.52  4715.5  193.09
  4810.9  193.02  4874.9  191.09  4979.2  190.33  4980.9  188.63  4981.9  186.63
  5018.1  186.63  5019.1  188.63  5020.9   190.2  5026.1   190.4  5035.8  193.24
  5061.7  194.43  5090.5  195.06  5123.6  192.77  5133.7  193.34  5146.9  192.19
  5170.4  193.46  5176.1  192.41  5256.6  196.34  5300.9   196.7  5426.8  201.89
#Mann= 3 ,-1 , 0
  4446.7     .15       0  4980.9    .045       0  5019.1     .15       0
Bank Sta=4980.9,5019.1
XS Rating Curve= 0 ,0
Exp/Cntr=0.3,0.1

Type RM Length L Ch R = 1 ,52340   ,480,480,480
BEGIN DESCRIPTION:
CEDAR CREEK 134.0
END DESCRIPTION:
XS GIS Cut Line= 5
      2054425.56       765984.11      2054319.09       765995.73
      2054222.57       766055.06      2054028.83       766251.16
      2053701.78       766355.66
#Sta/Elev= 30
  4779.6  194.15  4835.9  194.77    4885  193.71  4977.7  188.84  4980.9  187.74
  4981.9  185.74  5018.1  185.74  5019.1  187.74    5021   190.4  5083.6  189.35
  5100.8   190.2  5141.3  189.71    5158  190.59  5204.3  189.61  5255.6  193.58
  5280.2  193.93  5324.1  193.52  5331.6  192.57  5341.8  193.15  5354.3  192.08
  5385.3  193.03  5398.4  192.57  5411.1  193.77  5448.8   195.2  5458.8  196.31
  5513.2  197.16  5536.2  198.44  5540.3  197.93  5586.5  200.39    5619  201.16
#Mann= 4 ,-1 , 0
  4779.6      .1       0  4977.7     .15       0  4980.9    .045       0
  5019.1     .15       0
Bank Sta=4980.9,5019.1
XS Rating Curve= 0 ,0
Exp/Cntr=0.3,0.1

Type RM Length L Ch R = 1 ,51860   ,560,560,560
BEGIN DESCRIPTION:
CEDAR CREEK 133.0
END DESCRIPTION:
XS GIS Cut Line= 4
      2054216.49       765860.65      2054055.92       765827.77
      2053848.45       765812.88      2053589.56       765834.54
#Sta/Elev= 30
  4628.1  194.12  4745.9  192.25  4822.4  192.07  4865.3  191.19  4884.4  190.42
  4890.2  189.87  4895.6  188.57  4912.6  189.39  4945.8  189.19  4967.4  188.49
    4973  187.52  4978.9  188.24  4980.9   187.3  4981.9   185.3  5018.1   185.3
  5019.1   187.3  5020.6  190.03  5030.4  189.54  5054.1  189.85  5065.9  189.17
  5092.7  190.01  5097.6  191.54  5106.3  192.26  5131.9  196.75  5160.2  202.82
  5167.2  205.46  5182.3  208.18  5216.5  211.46  5242.9  214.94  5259.8  215.62
#Mann= 4 ,-1 , 0
  4628.1      .1       0  4865.3     .15       0  4980.9    .045       0
  5019.1     .15       0
Bank Sta=4980.9,5019.1
XS Rating Curve= 0 ,0
Exp/Cntr=0.3,0.1

Type RM Length L Ch R = 1 ,51300   ,500,500,500
BEGIN DESCRIPTION:
CEDAR CREEK 132.0
END DESCRIPTION:
XS GIS Cut Line= 4
      2054524.19       765693.27       2054264.9        765457.2
      2054006.57       765365.44      2053672.77       765364.32
#Sta/Elev= 30
  4375.2  193.31  4546.1  192.26  4730.6  192.24  4796.8  191.14  4862.8  189.12
  4881.1   189.8  4906.2  188.75  4954.4   188.3  4974.2  186.91  4980.1  187.93
  4980.9  186.55  4981.9  184.55  5018.1  184.55  5019.1  186.55  5022.6  188.06
  5036.1  188.73    5054  188.15  5065.2  189.11  5070.3  190.26  5075.9  190.25
  5113.1  193.55  5136.5   194.1  5152.2  195.46  5164.1  198.05  5180.5  199.71
  5196.3   202.4  5238.8  206.64  5248.1  206.96  5255.4  208.14  5333.8  213.96
#Mann= 4 ,-1 , 0
  4375.2      .1       0  4906.2     .15       0  4980.9    .045       0
  5019.1     .15       0
Bank Sta=4980.9,5019.1
XS Rating Curve= 0 ,0
Exp/Cntr=0.3,0.1

Type RM Length L Ch R = 1 ,50800   ,400,400,400
BEGIN DESCRIPTION:
CEDAR CREEK 131.0
END DESCRIPTION:
XS GIS Cut Line= 3
      2054979.97        765072.7      2054274.35       764955.38
      2053647.65       764954.08
#Sta/Elev= 30
  4284.7  202.22  4344.7  196.88  4389.7  194.66  4419.7  191.03  4439.7  193.84
  4479.7  192.16  4624.7     192  4760.7  190.29  4819.7  189.86  4839.7  186.95
  4849.7  187.66  4969.7  187.54  4979.7   186.7  4980.9  184.68  4981.9  182.68
  5018.1  182.68  5019.1  184.68    5020  187.68    5025  188.19    5060  188.06
    5085  190.41    5115  191.32    5205  190.79    5285  191.62    5320  190.92
    5340  191.96    5425  193.21    5545  198.05    5575  200.43  5626.7  206.33
#Mann= 4 ,-1 , 0
  4284.7      .1       0  4760.7     .15       0  4980.9    .045       0
  5019.1     .15       0
Bank Sta=4980.9,5019.1
XS Rating Curve= 0 ,0
Exp/Cntr=0.3,0.1

Type RM Length L Ch R = 1 ,50400   ,300,300,300
BEGIN DESCRIPTION:
CEDAR CREEK 130.0
END DESCRIPTION:
XS GIS Cut Line= 3
      2054630.66       764501.66      2054302.37       764556.83
      2053738.56        764619.7
#Sta/Elev= 30
  4667.1  196.37  4726.3  193.06  4787.2  191.76  4839.4  191.04  4856.1  187.26
  4875.4  189.12    4904  187.05  4947.9  186.46  4980.7  187.27  4980.9  183.98
  4981.9  181.98  5018.1  181.98  5019.1  183.98    5020  186.68  5026.5  187.39
  5061.8  186.92  5077.3  187.93  5090.4  185.93  5149.5  187.66    5170  187.15
  5190.9  188.08  5204.1  189.98  5235.6  191.93  5266.5  191.86  5292.1  193.03
  5329.7  192.59  5347.1  193.73  5405.7  192.69  5436.1  194.36  5567.3  197.79
#Mann= 4 ,-1 , 0
  4667.1      .1       0  4787.2     .15       0  4980.9    .045       0
  5019.1     .15       0
Bank Sta=4980.9,5019.1
XS Rating Curve= 0 ,0
Exp/Cntr=0.3,0.1

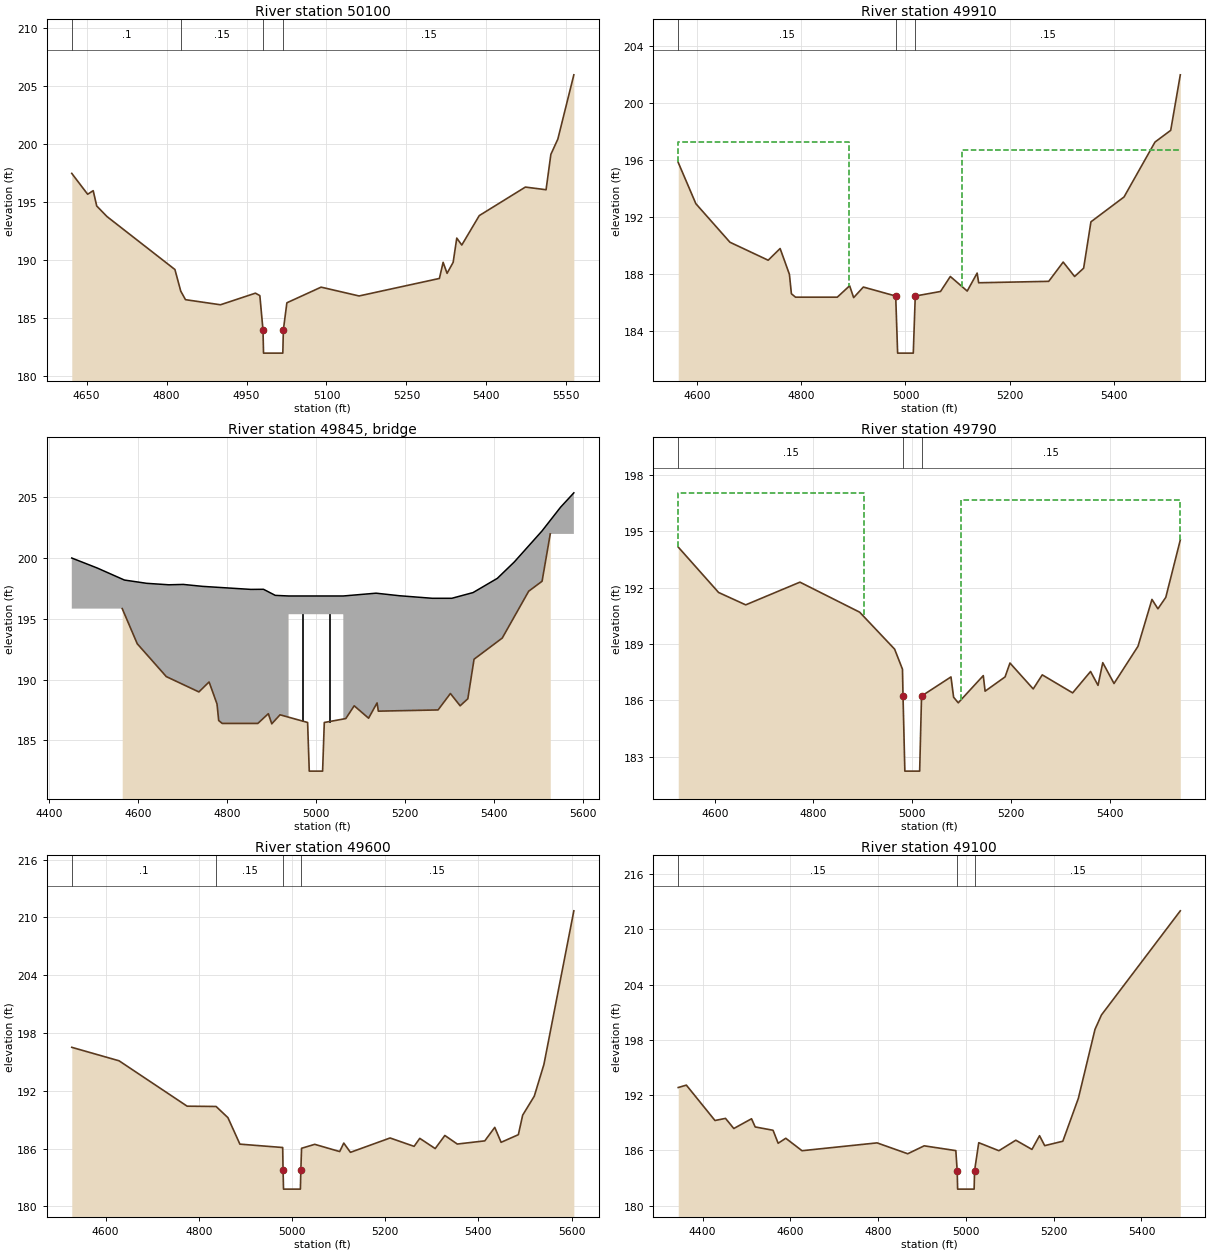
Type RM Length L Ch R = 1 ,50100   ,190,190,190
BEGIN DESCRIPTION:
CEDAR CREEK 129.0
END DESCRIPTION:
XS GIS Cut Line= 3
      2054667.41       764438.39      2054335.11       764258.63
      2053812.12       764047.51
#Sta/Elev= 30
  4622.2  197.43    4652  195.63  4662.4  195.94    4669  194.62  4688.2  193.71
  4815.7  189.14  4826.6  187.28  4835.5  186.54  4901.1   186.1  4966.7   187.1
    4975  186.89  4980.9  183.93  4981.9  181.93  5018.1  181.93  5019.1  183.93
  5025.7  186.27  5089.9  187.62  5161.1  186.86  5311.8  188.37  5318.8  189.76
  5326.2  188.81  5337.6  189.76  5344.4  191.85  5353.8  191.25  5386.6  193.79
  5473.1  196.25  5511.9  196.02  5520.9  199.07    5534  200.39    5564  205.93
#Mann= 4 ,-1 , 0
  4622.2      .1       0  4826.6     .15       0  4980.9    .045       0
  5019.1     .15       0
Bank Sta=4980.9,5019.1
XS Rating Curve= 0 ,0
Exp/Cntr=0.5,0.3

Type RM Length L Ch R = 1 ,49910   ,120,120,120
BEGIN DESCRIPTION:
CDC_Crossing Creek Rd-US
END DESCRIPTION:
XS GIS Cut Line= 3
      2054703.42       764332.46      2054356.05       764069.79
      2053858.41       763896.96
#Sta/Elev= 30
  4564.5  195.84  4598.3  192.95  4663.6  190.25  4736.9  188.99  4759.8  189.81
  4777.6     188  4781.4  186.64  4789.3   186.4  4869.4   186.4    4893   187.2
  4900.7  186.37  4919.3  187.11  4981.3  186.48    4985  182.48    5015  182.48
  5018.8  186.48  5067.2   186.8    5086  187.85  5118.4  186.83  5137.4  188.09
  5140.3  187.41  5274.6  187.51  5302.3  188.86  5324.2  187.85  5341.5  188.43
  5355.5  191.68  5418.9  193.42  5478.3  197.27  5508.4  198.09  5526.8  201.98
#Mann= 3 ,-1 , 0
  4564.5     .15       0  4981.3    .045       0  5018.8     .15       0
#XS Ineff= 2 , 0
       0  4891.5  197.25  5108.5       0  196.69
Permanent Ineff=
       F       F
Bank Sta=4981.3,5018.8
XS Rating Curve= 0 ,0
Exp/Cntr=0.5,0.3

Type RM Length L Ch R = 3 ,49845   ,,,
BEGIN DESCRIPTION:
CDC_Crossing Creek Rd-TOR
Structure ID: LDS 272
Approximate Survey Structure
END DESCRIPTION:
Bridge Culvert--1,0,-1,-1, 0
Deck Dist Width WeirC Skew NumUp NumDn MinLoCord MaxHiCord MaxSubmerge Is_Ogee
47,36,3,0, 24, 24, , , 0.95, 0, 1,1,,
  4451.1  4508.3  4569.4  4619.7  4669.2  4701.8  4745.2  4853.9  4882.1  4908.6
  4938.5  4938.5  5061.5  5061.5  5135.2  5187.8  5261.6  5305.5  5353.2  5407.8
    5446  5508.1    5550  5579.8
     200  199.18  198.19  197.92   197.8  197.83  197.67  197.42  197.43  196.93
  196.88  196.88  196.88  196.88  197.11   196.9  196.69  196.69  197.16  198.33
  199.68  202.22  204.18  205.36
  162.48  162.48  162.48  162.48  162.48  162.48  162.48  162.48  162.48  162.48
  162.48  195.38  195.38  162.48  162.48  162.48  162.48  162.48  162.48  162.48
  162.48  162.48  162.48  162.48
  4451.1  4508.3  4569.4  4619.7  4669.2  4701.8  4745.2  4853.9  4882.1  4908.6
  4938.5  4938.5  5061.5  5061.5  5135.2  5187.8  5261.6  5305.5  5353.2  5407.8
    5446  5508.1    5550  5579.8
     200  199.18  198.19  197.92   197.8  197.83  197.67  197.42  197.43  196.93
  196.88  196.88  196.88  196.88  197.11   196.9  196.69  196.69  197.16  198.33
  199.68  202.22  204.18  205.36
  162.48  162.48  162.48  162.48  162.48  162.48  162.48  162.48  162.48  162.48
  162.48  195.38  195.38  162.48  162.48  162.48  162.48  162.48  162.48  162.48
  162.48  162.48  162.48  162.48
Pier Skew, UpSta & Num, DnSta & Num=  ,4969.3, 2 ,4969.3, 2 , 0 , 0 , 0 ,0,0
       1       1
  186.46  195.38
       1       1
   188.3  195.38
Pier Skew, UpSta & Num, DnSta & Num=  ,5030.8, 2 ,5030.8, 2 , 0 , 0 , 0 ,0,0
       1       1
  186.21  195.38
       1       1
  186.54  195.38
Abutment Skew #Up #Dn= , 2 , 2
  4938.5  4953.5
  195.38  186.71
  4938.5  4953.5
  195.38  189.15
Abutment Skew #Up #Dn= , 2 , 2
  5046.5  5061.5
  187.16  195.38
  5046.5  5061.5
  186.47  195.38
BR Coef= 1 , 1 , 0 ,1.25, 0 ,,,0.8,0,2,0,
WSPro=,,,, 1 ,,,, 0 ,,,, 0 ,,,,-1 ,-1 ,-1 , 0 , 0 , 0 , 0 , 0
BC Design=,, 0 ,, 0 ,,,,,,
BC HTab HWMax=201.98
BC Use User HTab Curves=0
BC User HTab FreeFlow(D)= 0

Type RM Length L Ch R = 1 ,49790   ,190,190,190
BEGIN DESCRIPTION:
CDC_Crossing Creek Rd-DS
END DESCRIPTION:
XS GIS Cut Line= 4
      2054751.62       764238.06      2054556.01       764054.01
      2054377.98       763951.93      2053883.48       763728.34
#Sta/Elev= 30
  4526.2  194.17  4607.9  191.75  4662.8  191.09  4772.6   192.3  4893.5   190.7
  4964.3  188.73  4980.2  187.66  4981.3  186.23    4985  182.23    5015  182.23
  5018.8  186.23  5078.4  187.25  5083.7  186.17  5093.1  185.87  5143.8  187.32
  5147.5  186.49  5187.9  187.25  5197.8  187.99  5244.9  186.61  5263.2  187.36
  5324.7   186.4    5361  187.54  5376.1   186.8  5385.7  188.01  5408.5   186.9
    5457  188.88  5485.3  191.38  5497.4  190.88  5513.3  191.49  5542.7  194.55
#Mann= 3 ,-1 , 0
  4526.2     .15       0  4981.3    .045       0  5018.8     .15       0
#XS Ineff= 2 , 0
       0  4901.5  197.06  5098.5       0  196.69
Permanent Ineff=
       F       F
Bank Sta=4981.3,5018.8
XS Rating Curve= 0 ,0
Exp/Cntr=0.5,0.3

Type RM Length L Ch R = 1 ,49600   ,500,500,500
BEGIN DESCRIPTION:
CEDAR CREEK 125.0
END DESCRIPTION:
XS GIS Cut Line= 3
      2054857.04       763883.41      2054400.08       763763.22
      2053829.95       763561.08
#Sta/Elev= 30
  4527.5  196.52  4629.1  195.12  4775.1  190.41  4837.2  190.38  4862.6  189.22
  4888.3  186.47  4980.1  186.12  4980.9   183.8  4981.9   181.8  5018.1   181.8
  5019.1   183.8  5020.6  186.04  5048.9  186.45  5102.4   185.7  5111.2  186.58
  5125.5  185.62  5210.6  187.11  5262.1  186.24  5274.3  187.07  5307.4  186.01
  5328.1  187.37  5354.8  186.48  5413.8  186.81  5435.2  188.21  5448.8  186.66
  5485.8  187.45  5495.1  189.48    5520  191.45  5540.7  194.75  5604.9  210.69
#Mann= 4 ,-1 , 0
  4527.5      .1       0  4837.2     .15       0  4980.9    .045       0
  5019.1     .15       0
Bank Sta=4980.9,5019.1
XS Rating Curve= 0 ,0
Exp/Cntr=0.3,0.1

Type RM Length L Ch R = 1 ,49100   ,500,500,500
BEGIN DESCRIPTION:
CEDAR CREEK 124.0
END DESCRIPTION:
XS GIS Cut Line= 3
      2055116.33       763456.72      2054487.52       763272.26
      2054015.32       763147.12
#Sta/Elev= 30
  4344.7  192.83  4363.2  193.09  4428.4  189.25  4452.4  189.48  4471.3  188.38
  4511.7  189.44    4520  188.55  4560.7  188.19  4572.3  186.78  4589.7  187.32
  4626.7  185.97  4797.7  186.82  4867.5  185.64    4905   186.5  4977.1  185.98
  4980.2   183.8  4981.2   181.8  5018.8   181.8  5019.8   183.8  5029.3  186.84
  5075.2  185.97  5113.8  187.11  5150.5  186.11  5167.8   187.6  5179.6  186.52
  5220.9     187  5256.2  191.65  5294.2  199.15  5308.9  200.71  5488.5  212.01
#Mann= 3 ,-1 , 0
  4344.7     .15       0  4980.2    .045       0  5019.8     .15       0
Bank Sta=4980.2,5019.8
XS Rating Curve= 0 ,0
Exp/Cntr=0.3,0.1

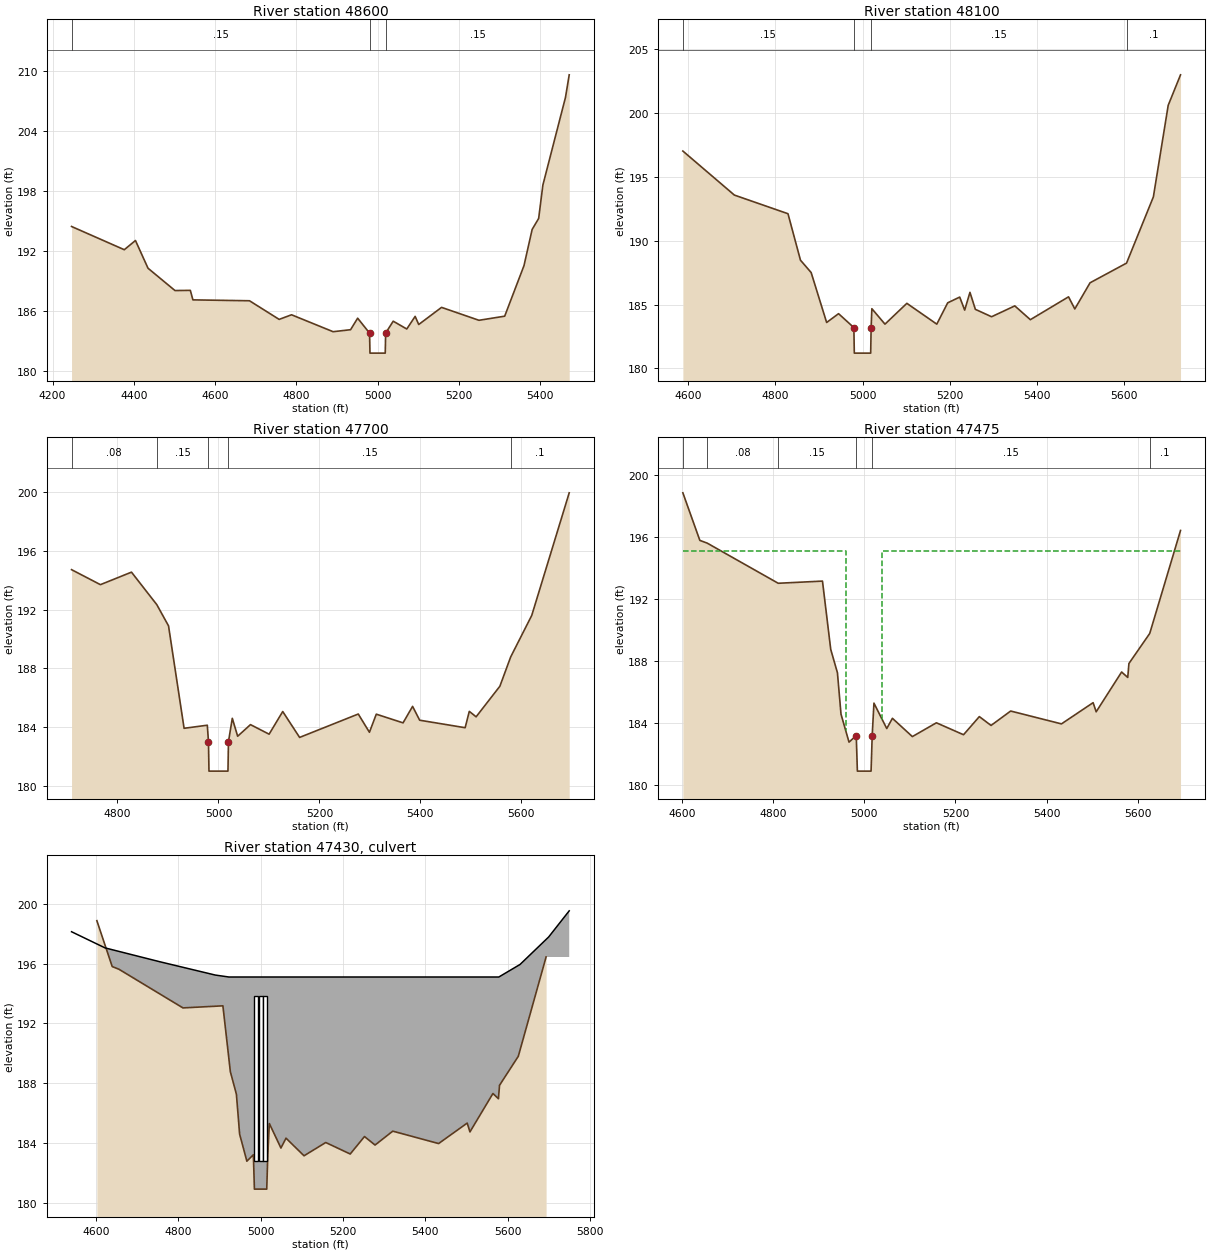
Type RM Length L Ch R = 1 ,48600   ,500,500,500
BEGIN DESCRIPTION:
CEDAR CREEK 123.0
END DESCRIPTION:
XS GIS Cut Line= 3
      2055391.14       762913.16       2054646.5       762799.25
      2054181.67       762719.65
#Sta/Elev= 30
  4246.7  194.43  4376.5  192.11    4404  193.03  4434.9  190.26  4501.3  188.03
  4539.1  188.05  4545.4   187.1  4684.7  187.01  4757.7  185.15  4788.2  185.61
  4890.5  183.92  4933.5  184.12  4950.9  185.27  4980.2  183.78  4981.2  181.78
  5018.8  181.78  5019.8  183.78  5038.4  184.97  5071.8  184.19  5092.4  185.45
  5101.2  184.64  5157.4  186.35  5249.5  185.06  5312.8  185.47  5360.3  190.52
  5380.4  194.14  5396.4  195.23  5406.8  198.57  5462.4  207.32  5471.6  209.58
#Mann= 3 ,-1 , 0
  4246.7     .15       0  4980.2    .045       0  5019.8     .15       0
Bank Sta=4980.2,5019.8
XS Rating Curve= 0 ,0
Exp/Cntr=0.3,0.1

Type RM Length L Ch R = 1 ,48100   ,400,400,400
BEGIN DESCRIPTION:
CEDAR CREEK 122.0
END DESCRIPTION:
XS GIS Cut Line= 3
      2055334.98       762418.75      2054922.78       762421.02
      2054195.27       762478.74
#Sta/Elev= 30
  4587.8  197.03    4706  193.58    4829  192.12  4857.7  188.48  4882.2  187.51
  4917.7   183.6  4945.1  184.29  4980.2   183.2  4981.2   181.2  5018.8   181.2
  5019.8   183.2  5021.5  184.68  5051.6  183.47  5101.8   185.1  5170.5  183.47
  5195.5  185.14  5223.1  185.59  5234.5  184.57  5246.6  185.96    5259  184.63
  5296.2  184.05  5349.5   184.9  5385.2  183.82  5472.8  185.61  5487.2  184.66
  5522.2  186.71  5605.9  188.25  5667.5  193.44  5701.5  200.61  5729.8     203
#Mann= 4 ,-1 , 0
  4587.8     .15       0  4980.2    .045       0  5019.8     .15       0
  5605.9      .1       0
Bank Sta=4980.2,5019.8
XS Rating Curve= 0 ,0
Exp/Cntr=0.3,0.1

Type RM Length L Ch R = 1 ,47700   ,225,225,225
BEGIN DESCRIPTION:
CEDAR CREEK 121.0
END DESCRIPTION:
XS GIS Cut Line= 3
      2055189.89       762066.57      2054899.53       762085.73
      2054222.34       762240.72
#Sta/Elev= 30
    4709  194.71  4766.2  193.69  4827.7  194.54  4877.9  192.33  4901.1  190.89
  4931.9  183.93  4977.9  184.14  4980.2  183.02  4981.2  181.02  5018.8  181.02
  5019.8  183.02  5027.4  184.61    5038  183.39  5063.4  184.18  5100.3  183.53
  5127.3  185.07  5160.7  183.31  5276.9   184.9    5299  183.66  5312.6  184.89
  5365.6   184.3  5384.5  185.42  5398.5  184.48  5488.6  183.97  5496.8  185.08
  5510.3  184.71  5557.4  186.79  5578.8  188.78  5620.5   191.6  5694.7  199.93
#Mann= 5 ,-1 , 0
    4709     .08       0  4877.9     .15       0  4980.2    .045       0
  5019.8     .15       0  5578.8      .1       0
Bank Sta=4980.2,5019.8
XS Rating Curve= 0 ,0
Exp/Cntr=0.5,0.3

Type RM Length L Ch R = 1 ,47475   ,105,105,105
BEGIN DESCRIPTION:
CDC_Beulah Church Rd-US
END DESCRIPTION:
XS GIS Cut Line= 4
      2055272.94       761800.76      2054881.03        761867.2
      2054693.33       761937.76       2054254.1       762161.14
#Sta/Elev= 30
  4602.5  198.87  4639.7   195.8    4656  195.62  4811.5  193.03  4908.5  193.17
  4926.6  188.76  4941.3  187.25  4949.1  184.58  4966.7  182.77  4982.5   183.2
    4985   180.9    5015   180.9  5017.5   183.2  5021.3  185.29  5049.4  183.65
  5061.8  184.31  5105.5  183.13  5158.2  184.02  5217.7  183.25  5252.3  184.42
    5278  183.85    5321  184.78  5432.3  183.95  5501.7  185.32  5508.4  184.73
  5564.2   187.3  5577.6  186.95  5580.2  187.85  5625.8  189.79  5693.3  196.44
#Mann= 6 ,-1 , 0
  4602.5     .15       0    4656     .08       0  4811.5     .15       0
  4982.5    .045       0  5017.5     .15       0  5625.8      .1       0
#XS Ineff= 2 , 0
       0    4960   195.1    5040       0   195.1
Permanent Ineff=
       F       F
Bank Sta=4982.5,5017.5
XS Rating Curve= 0 ,0
Exp/Cntr=0.5,0.3

Type RM Length L Ch R = 2 ,47430   ,,,
BEGIN DESCRIPTION:
CDC_Beulah Church Rd-TOR
Structure ID: LDS 273
Approximate Survey Structure
END DESCRIPTION:
Bridge Culvert--1,0,-1,-1, 0
Deck Dist Width WeirC Skew NumUp NumDn MinLoCord MaxHiCord MaxSubmerge Is_Ogee
24,42,3,0, 9, 9, , , 0.95, 0, 1,1,,
    4541  4622.2  4754.1  4890.1    4923  5578.5    5630  5699.5  5749.4
  198.13  197.05  196.13  195.23   195.1   195.1  195.94  197.78  199.53
   160.9   160.9   160.9   160.9   160.9   160.9   160.9   160.9   160.9
    4541  4622.2  4754.1  4890.1    4923  5578.5    5630  5699.5  5749.4
  198.13  197.05  196.13  195.23   195.1   195.1  195.94  197.78  199.53
  160.69  160.69  160.69  160.69  160.69  160.69  160.69  160.69  160.69
BR Coef= 1 , 1 , 0 ,1.25, 0 ,,,0.8,0,2,0,
WSPro=,,,, 1 ,,,, 0 ,,,, 0 ,,,,-1 ,-1 ,-1 , 0 , 0 , 0 , 0 , 0
Culvert=2,11,10,42,0.012,0.4,1,8,1,182.8,4989,182.59,4989,Culvert #1  , 0 ,24
Culvert Bottom n=0.012
Culvert=2,11,10,42,0.012,0.4,1,8,1,182.8,5000,182.59,5000,Culvert #2  , 0 ,24
Culvert Bottom n=0.012
Culvert=2,11,10,42,0.012,0.4,1,8,1,182.8,5011,182.59,5011,Culvert #3  , 0 ,24
Culvert Bottom n=0.012
BC Design=,, 0 ,, 0 ,,,,,,
BC HTab HWMax=198.87
BC Use User HTab Curves=0
BC User HTab FreeFlow(D)= 0