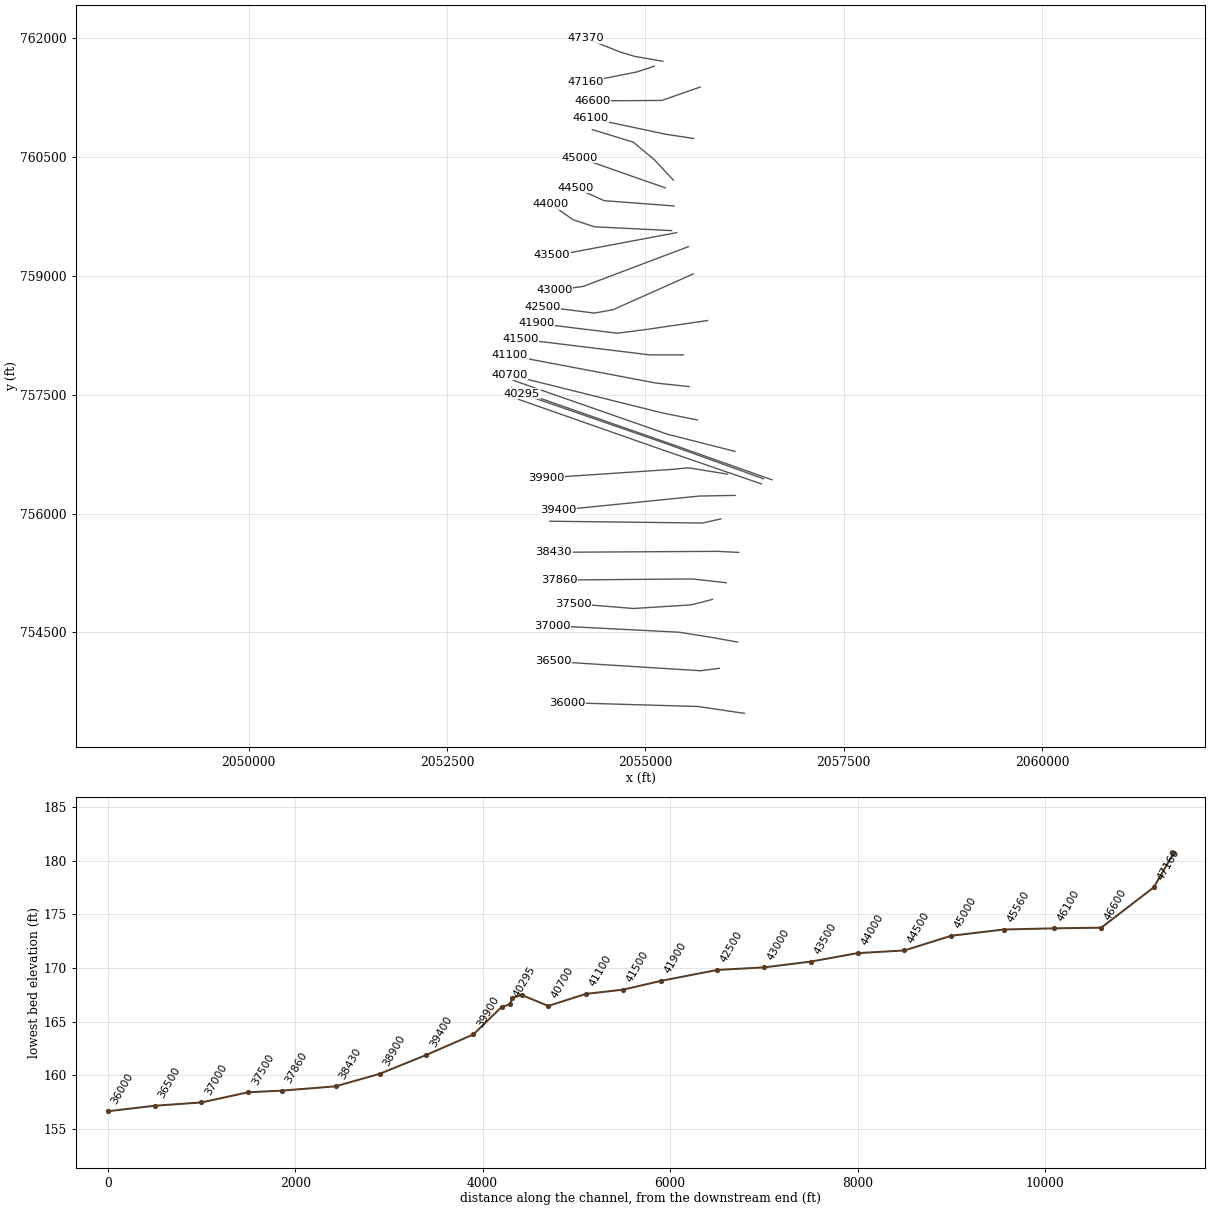
HEC-RAS study Cedar Creek.prj: Cedar Creek Limited Detail Study

--- Cedar Creek.g04 (geometry) --- (continued)

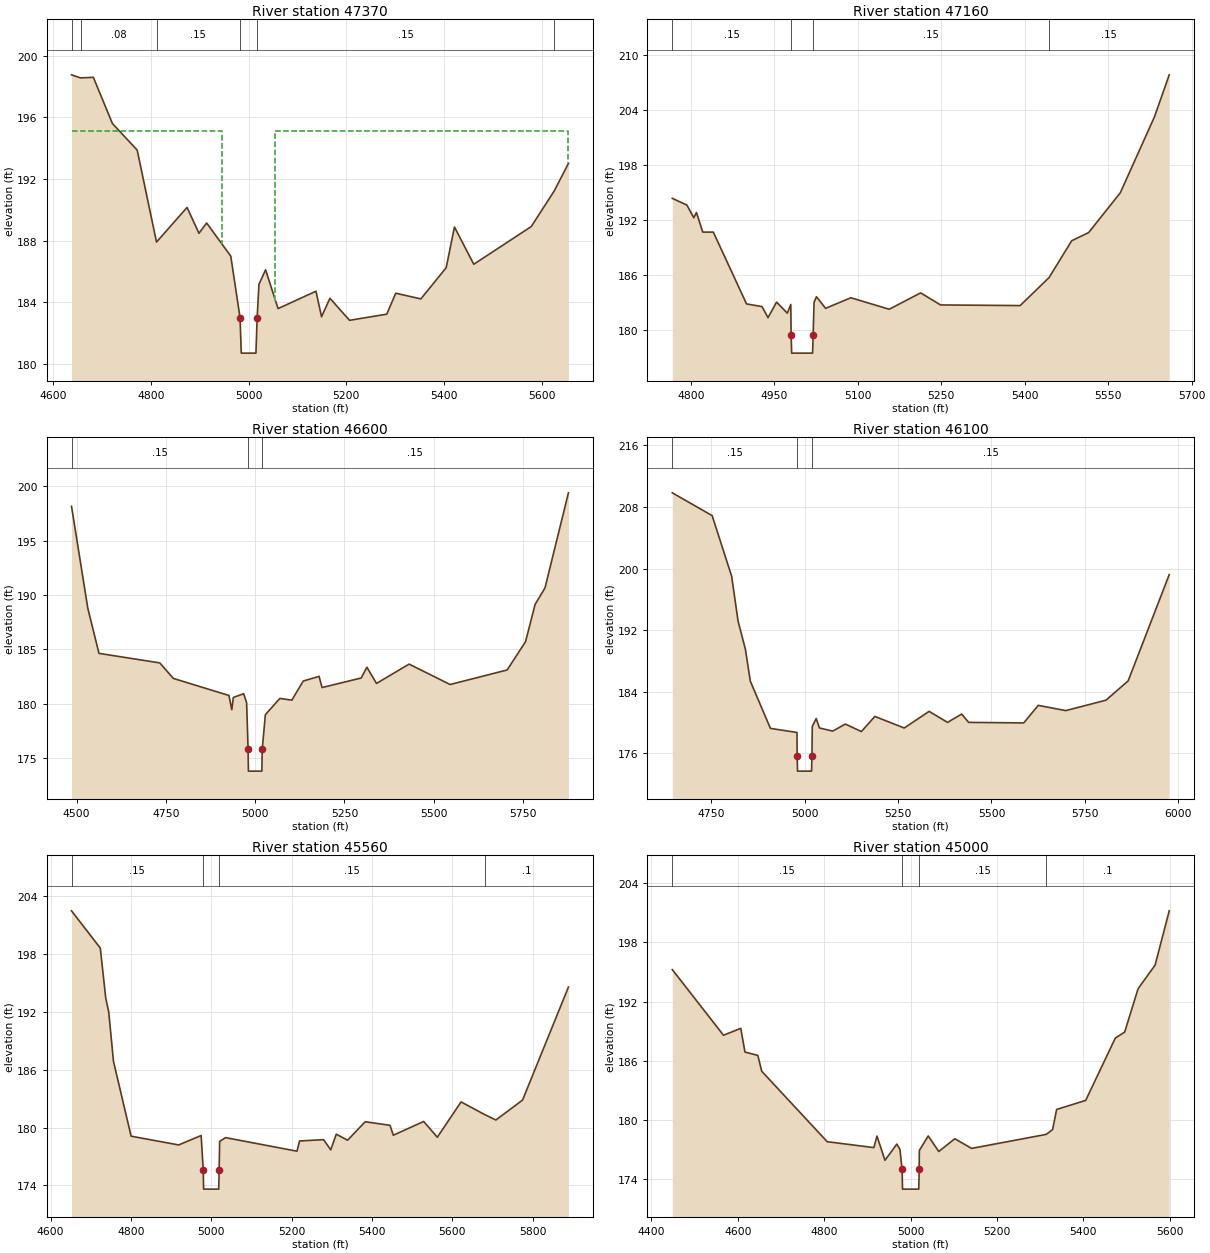
Type RM Length L Ch R = 1 ,47370   ,210,210,210
BEGIN DESCRIPTION:
CDC_Beulah Church Rd-DS
END DESCRIPTION:
XS GIS Cut Line= 4
      2055221.24       761702.07      2054864.07       761763.97
      2054677.04       761820.87      2054250.68       761991.42
#Sta/Elev= 30
  4637.5  198.76    4656  198.56  4682.2   198.6  4721.2   195.6    4772  193.87
  4811.5   187.9    4874  190.15  4898.4  188.47  4914.1  189.14  4963.5  186.99
  4982.5  182.99    4985  180.69    5015  180.69  5017.5  182.99  5021.2  185.16
  5034.8   186.1  5060.3  183.58  5137.9  184.71  5149.3  183.05  5166.5  184.25
  5206.6  182.82  5282.8  183.22  5301.2  184.58  5352.6  184.21  5404.5  186.24
  5421.4  188.88  5460.9  186.46  5578.7  188.91  5625.8  191.23  5654.7  193.01
#Mann= 6 ,-1 , 0
  4637.5     .15       0    4656     .08       0  4811.5     .15       0
  4982.5    .045       0  5017.5     .15       0  5625.8      .1       0
#XS Ineff= 2 , 0
       0    4945   195.1    5055       0   195.1
Permanent Ineff=
       F       F
Bank Sta=4982.5,5017.5
XS Rating Curve= 0 ,0
Exp/Cntr=0.5,0.3

Type RM Length L Ch R = 1 ,47160   ,560,560,560
BEGIN DESCRIPTION:
CEDAR CREEK 117.0
END DESCRIPTION:
XS GIS Cut Line= 3
      2055114.38       761639.88      2054892.54       761567.65
      2054245.58       761438.64
#Sta/Elev= 30
  4766.7  194.36  4792.9  193.63  4805.3  192.25  4810.1  192.82  4821.4  190.69
  4840.4  190.69  4900.1  182.88  4927.9  182.59  4938.7  181.39  4954.1  183.08
  4973.4  181.87  4979.6  182.82  4980.2  179.53  4981.2  177.53  5018.8  177.53
  5019.8  179.53  5021.4  183.05  5025.7  183.66  5042.2   182.4  5087.5  183.55
  5156.5   182.3    5213  184.08  5248.7  182.77  5391.8   182.7  5443.8  185.75
  5484.4  189.75  5514.9  190.64  5571.8  194.97    5633   203.2  5659.7  207.79
#Mann= 4 ,-1 , 0
  4766.7     .15       0  4980.2    .045       0  5019.8     .15       0
  5443.8     .15       0
Bank Sta=4980.2,5019.8
XS Rating Curve= 0 ,0
Exp/Cntr=0.3,0.1

Type RM Length L Ch R = 1 ,46600   ,500,500,500
BEGIN DESCRIPTION:
CEDAR CREEK 116.0
END DESCRIPTION:
XS GIS Cut Line= 3
      2055692.99       761377.29      2055207.62       761208.13
      2054330.74       761203.14
#Sta/Elev= 30
    4486  198.17  4531.7  188.76  4562.9  184.62  4733.2  183.74  4771.1  182.31
  4926.7  180.74  4934.6  179.43    4939  180.56    4968   180.9  4976.2  180.05
  4980.2  175.77  4981.2  173.77  5018.8  173.77  5019.8  175.77  5028.6  178.97
  5069.3  180.47  5102.6  180.31  5134.7  182.07  5178.9   182.5  5187.3  181.47
  5296.8  182.35  5312.8  183.34  5339.7  181.85    5431  183.63  5545.7  181.75
  5705.4  183.09  5756.9   185.7  5783.6  189.13  5811.3  190.65  5876.9  199.41
#Mann= 3 ,-1 , 0
    4486     .15       0  4980.2    .045       0  5019.8     .15       0
Bank Sta=4980.2,5019.8
XS Rating Curve= 0 ,0
Exp/Cntr=0.3,0.1

Type RM Length L Ch R = 1 ,46100   ,540,540,540
BEGIN DESCRIPTION:
CEDAR CREEK 115.0
END DESCRIPTION:
XS GIS Cut Line= 3
      2055607.82       760729.05        2055258.       760781.97
      2054303.63       760984.86
#Sta/Elev= 30
  4646.2  209.85  4752.8  206.89    4805  199.01  4822.1  193.21  4841.8  189.52
    4855  185.38  4908.7  179.26  4979.7  178.73  4980.2  175.71  4981.2  173.71
  5018.8  173.71  5019.8  175.71  5020.7  179.51  5031.1  180.54  5039.9  179.31
  5075.4  178.91  5109.2  179.82  5152.1  178.85  5188.1  180.81  5266.7  179.31
  5333.3  181.47  5382.6  180.04  5420.4  181.12  5439.1  180.04  5586.4  179.97
  5625.3  182.25  5698.9  181.57  5806.4  182.92  5865.8  185.43  5975.7  199.23
#Mann= 3 ,-1 , 0
  4646.2     .15       0  4980.2    .045       0  5019.8     .15       0
Bank Sta=4980.2,5019.8
XS Rating Curve= 0 ,0
Exp/Cntr=0.3,0.1

Type RM Length L Ch R = 1 ,45560   ,560,560,560
BEGIN DESCRIPTION:
CEDAR CREEK 114.0
END DESCRIPTION:
XS GIS Cut Line= 4
      2055352.39       760205.05      2055115.06       760459.16
      2054851.23       760681.06      2054330.58       760840.97
#Sta/Elev= 30
  4652.3  202.51    4724  198.64  4737.5  193.45  4744.9  192.02  4756.8  186.87
  4800.7   179.1  4919.1  178.19    4975  179.17  4980.2   175.6  4981.2   173.6
  5018.8   173.6  5019.8   175.6  5021.1  178.56  5035.9  178.95  5213.6  177.54
    5220   178.6  5279.9  178.74  5297.6  177.68  5311.5  179.31  5339.5  178.68
  5383.5   180.6  5445.2  180.23  5453.4   179.2  5529.1  180.63    5563  178.99
  5622.1  182.66  5680.7  181.35  5708.8  180.78  5775.2  182.85  5889.4  194.59
#Mann= 4 ,-1 , 0
  4652.3     .15       0  4980.2    .045       0  5019.8     .15       0
  5680.7      .1       0
Bank Sta=4980.2,5019.8
XS Rating Curve= 0 ,0
Exp/Cntr=0.3,0.1

Type RM Length L Ch R = 1 ,45000   ,500,500,500
BEGIN DESCRIPTION:
CEDAR CREEK 113.0
END DESCRIPTION:
XS GIS Cut Line= 3
      2055251.77       760106.35      2054730.68       760287.88
      2054166.25       760487.54
#Sta/Elev= 30
  4448.2  195.23  4566.7  188.59  4606.7  189.29  4616.4  186.89  4646.2  186.55
  4655.2  184.95  4806.8  177.82  4914.9  177.22    4922  178.39  4940.6  175.94
  4968.1  177.58  4975.3  177.02  4980.2  175.02  4981.2  173.02  5018.8  173.02
  5019.8  175.02  5020.1  176.93  5040.7   178.4  5065.1  176.83  5102.4  178.12
    5141  177.14    5314  178.56  5328.7  179.05    5338  181.08  5405.3     182
  5473.9  188.31  5495.5  188.91  5526.6   193.3    5566  195.69  5598.7  201.18
#Mann= 4 ,-1 , 0
  4448.2     .15       0  4980.2    .045       0  5019.8     .15       0
    5314      .1       0
Bank Sta=4980.2,5019.8
XS Rating Curve= 0 ,0
Exp/Cntr=0.3,0.1

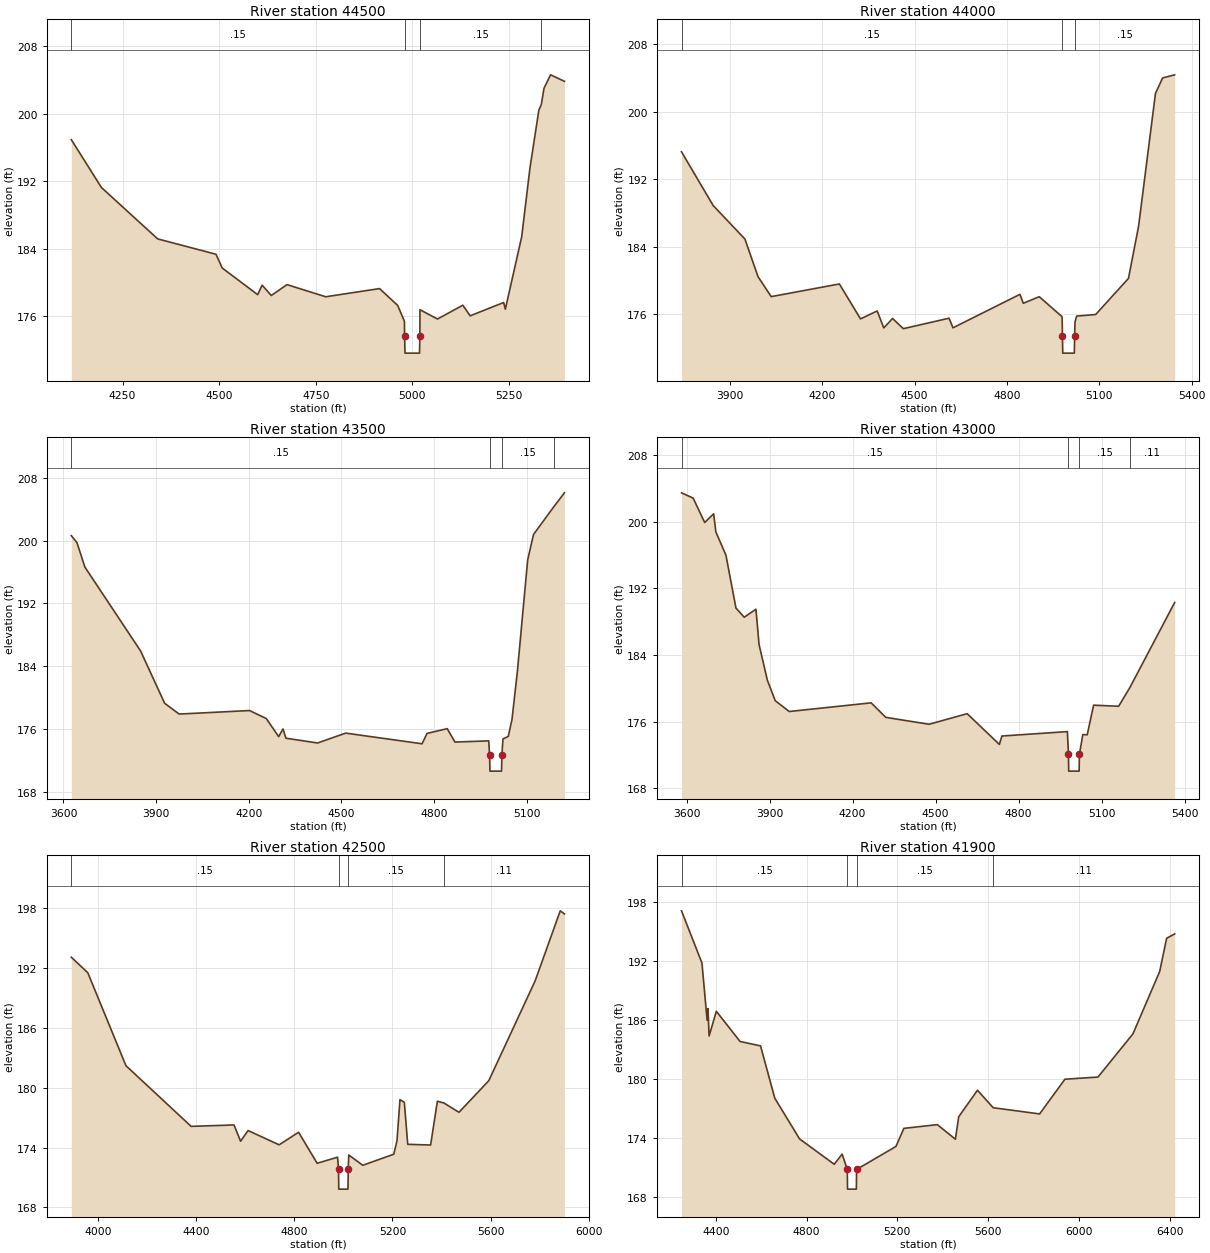
Type RM Length L Ch R = 1 ,44500   ,500,500,500
BEGIN DESCRIPTION:
CEDAR CREEK 112.0
END DESCRIPTION:
XS GIS Cut Line= 3
      2055360.84       759878.02      2054480.54       759944.42
      2054121.68       760107.32
#Sta/Elev= 30
  4117.2  196.95  4195.2  191.28  4340.9  185.19  4491.9  183.37  4507.9  181.74
  4599.8  178.58  4611.3  179.71  4634.9  178.48  4675.7  179.77  4775.9  178.33
  4915.3   179.3  4962.2  177.31  4979.7  175.43  4980.2  173.65  4981.2  171.65
  5018.8  171.65  5019.8  173.65    5020   176.8  5065.4  175.69    5131  177.33
  5149.9  176.07  5236.7  177.65  5241.1  176.86  5283.4  185.44  5304.8  193.59
  5327.8  200.44  5334.3  201.13  5341.2  203.05  5358.2  204.64  5394.1  203.87
#Mann= 4 ,-1 , 0
  4117.2     .15       0  4980.2    .045       0  5019.8     .15       0
  5334.3      .1       0
Bank Sta=4980.2,5019.8
XS Rating Curve= 0 ,0
Exp/Cntr=0.3,0.1

Type RM Length L Ch R = 1 ,44000   ,500,500,500
BEGIN DESCRIPTION:
CEDAR CREEK 111.0
END DESCRIPTION:
XS GIS Cut Line= 4
      2055330.92       759567.08       2054357.3       759615.46
      2054088.77       759704.09      2053807.03       759902.69
#Sta/Elev= 30
  3742.4  195.27  3845.3   188.9  3948.4  184.93  3991.1  180.46  4033.9   178.1
  4255.4   179.6    4324  175.46  4378.2   176.4  4399.7  174.39  4428.1  175.51
  4463.2   174.3  4611.7  175.54  4624.5   174.4  4842.1  178.37    4853  177.31
  4904.7  178.09  4978.1  175.75  4979.2   175.6  4980.2   173.4  4981.2   171.4
  5018.8   171.4  5019.8   173.4    5021   175.1  5026.3  175.79  5088.2  175.98
  5194.7  180.26  5227.6  186.45  5282.4  202.19  5305.6  204.03  5344.7   204.4
#Mann= 3 ,-1 , 0
  3742.4     .15       0  4980.2    .045       0  5019.8     .15       0
Bank Sta=4980.2,5019.8
XS Rating Curve= 0 ,0
Exp/Cntr=0.3,0.1

Type RM Length L Ch R = 1 ,43500   ,500,500,500
BEGIN DESCRIPTION:
CEDAR CREEK 110.0
END DESCRIPTION:
XS GIS Cut Line= 3
      2055393.77       759541.07       2054042.8       759287.29
      2053822.26        759257.8
#Sta/Elev= 30
  3625.4  200.65  3643.5  199.79  3669.3  196.65  3849.8  185.94  3927.6  179.27
  3974.7  177.89  4202.6  178.34  4256.8  177.32    4297  175.01    4311  175.99
  4320.5  174.81  4422.9   174.2  4514.2  175.46  4761.4   174.1  4777.5  175.42
  4842.8  176.03  4867.9  174.32  4977.2  174.47  4980.2  172.61  4981.2  170.61
  5018.8  170.61  5019.8  172.61  5023.5  174.72  5040.6  175.04  5052.6  177.19
    5070  183.29  5103.5  197.58  5122.4  200.81  5189.9  204.44  5222.5  206.12
#Mann= 4 ,-1 , 0
  3625.4     .15       0  4980.2    .045       0  5019.8     .15       0
  5189.9     .11       0
Bank Sta=4980.2,5019.8
XS Rating Curve= 0 ,0
Exp/Cntr=0.3,0.1

Type RM Length L Ch R = 1 ,43000   ,500,500,500
BEGIN DESCRIPTION:
CEDAR CREEK 109.0
END DESCRIPTION:
XS GIS Cut Line= 3
      2055542.52        759364.5      2054215.96       758863.24
      2053855.38       758814.22
#Sta/Elev= 30
  3581.9  203.45  3623.9  202.82  3665.6  199.89    3698  200.93    3706  198.76
  3742.6  195.96  3778.6  189.63  3808.5  188.53  3850.9  189.49  3862.1  185.26
  3892.1  180.98  3920.6  178.52  3971.1  177.22  4267.1  178.26  4320.1  176.52
  4476.5  175.69  4614.2  176.96  4730.6  173.27  4739.7  174.28  4976.3  174.81
  4980.2  172.07  4981.2  170.07  5018.8  170.07  5019.8  172.07  5032.1  174.45
    5048  174.43  5071.1  177.98  5161.6  177.85  5202.6  180.12  5363.9  190.29
#Mann= 4 ,-1 , 0
  3581.9     .15       0  4980.2    .045       0  5019.8     .15       0
  5202.6     .11       0
Bank Sta=4980.2,5019.8
XS Rating Curve= 0 ,0
Exp/Cntr=0.3,0.1

Type RM Length L Ch R = 1 ,42500   ,600,600,600
BEGIN DESCRIPTION:
CEDAR CREEK 108.0
END DESCRIPTION:
XS GIS Cut Line= 4
      2055604.58       759020.94      2054592.66       758569.62
      2054360.33       758527.28      2053701.22       758608.92
#Sta/Elev= 30
    3892  193.07    3959  191.52  4114.5   182.2  4379.9  176.12  4554.6  176.26
  4581.3  174.63    4612   175.7  4738.3  174.27  4817.6  175.53  4893.2  172.42
  4976.3  173.03  4980.2  171.83  4981.2  169.83  5018.8  169.83  5019.8  171.83
  5021.9  173.25    5079  172.22  5205.4  173.33  5218.5  174.71  5230.5   178.8
  5248.2  178.52  5262.1  174.32  5355.3  174.25  5382.8  178.64  5408.8  178.47
  5470.9  177.53  5592.3   180.7    5781   190.7  5883.2  197.72  5900.3  197.41
#Mann= 4 ,-1 , 0
    3892     .15       0  4980.2    .045       0  5019.8     .15       0
  5408.8     .11       0
Bank Sta=4980.2,5019.8
XS Rating Curve= 0 ,0
Exp/Cntr=0.3,0.1

Type RM Length L Ch R = 1 ,41900   ,400,400,400
BEGIN DESCRIPTION:
CEDAR CREEK 107.0
END DESCRIPTION:
XS GIS Cut Line= 4
       2055784.4       758433.55      2055041.35       758324.55
      2054644.54       758273.31      2053630.29       758398.05
#Sta/Elev= 30
    4249  197.12  4339.1  191.81  4361.9  185.98  4365.7  187.17  4370.5  184.39
  4402.5   186.9    4507  183.83  4597.3  183.38    4660  178.06  4769.2  173.92
  4921.9  171.34  4956.9  172.37  4979.5  170.81  4980.5  168.81  5019.5  168.81
  5020.5  170.81  5193.9  173.15  5228.9  174.99  5376.2  175.37  5455.9  173.89
  5470.5  176.17  5553.2  178.87  5622.5  177.09  5827.1  176.46  5938.6  179.99
  6084.2  180.21  6238.5  184.61    6356  190.94  6386.8  194.33    6422  194.77
#Mann= 4 ,-1 , 0
    4249     .15       0  4979.5    .045       0  5020.5     .15       0
  5622.5     .11       0
Bank Sta=4979.5,5020.5
XS Rating Curve= 0 ,0
Exp/Cntr=0.3,0.1

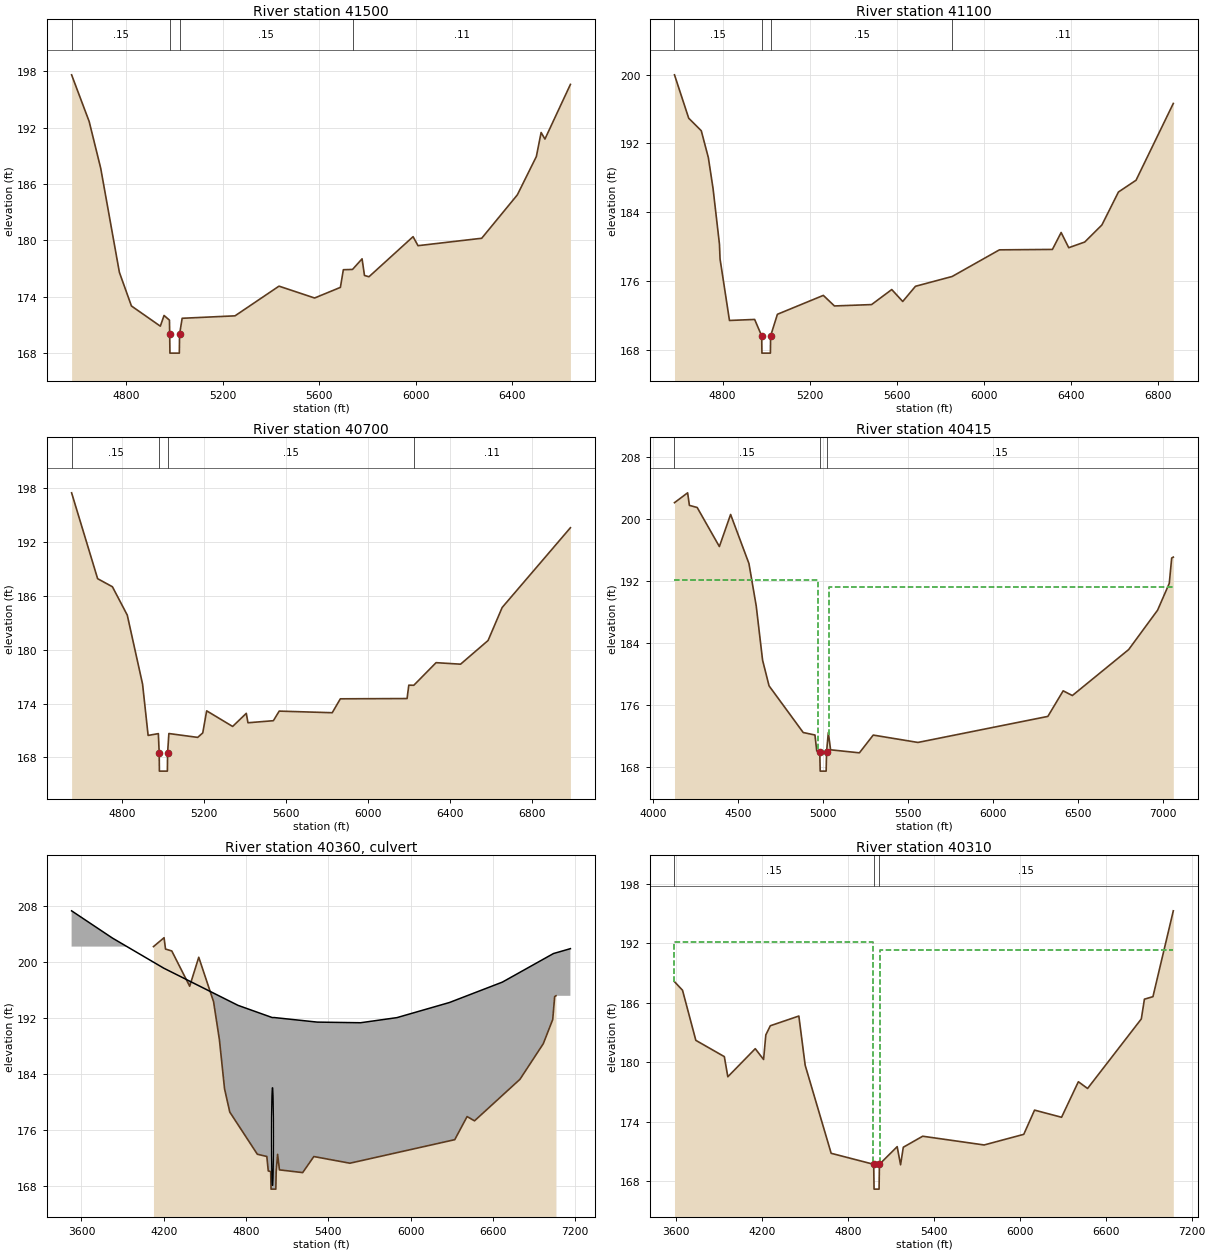
Type RM Length L Ch R = 1 ,41500   ,400,400,400
BEGIN DESCRIPTION:
CEDAR CREEK 106.0
END DESCRIPTION:
XS GIS Cut Line= 3
      2055480.28       758000.54      2055052.78        758000.5
      2053422.49       758199.53
#Sta/Elev= 30
  4572.5  197.63  4645.4  192.66  4693.3  187.68  4770.8   176.6  4820.8  173.02
  4940.7  170.87  4956.1  172.01  4978.6  171.51  4979.5     170  4980.5     168
  5019.5     168  5020.5     170  5031.2  171.71  5250.6  171.97  5433.1  175.13
  5580.9  173.87  5687.9     175  5700.1  176.88  5738.2  176.91  5777.8  178.04
  5787.8  176.27  5806.4  176.13  5989.5   180.4  6009.9  179.44  6274.3  180.23
  6422.1  184.85    6501  188.93  6520.8  191.49  6536.6  190.79  6642.4  196.61
#Mann= 4 ,-1 , 0
  4572.5     .15       0  4979.5    .045       0  5020.5     .15       0
  5738.2     .11       0
Bank Sta=4979.5,5020.5
XS Rating Curve= 0 ,0
Exp/Cntr=0.3,0.1

Type RM Length L Ch R = 1 ,41100   ,400,400,400
BEGIN DESCRIPTION:
CEDAR CREEK 105.0
END DESCRIPTION:
XS GIS Cut Line= 3
      2055551.57       757600.27      2055132.47       757645.13
      2053293.03       757993.32
#Sta/Elev= 30
  4578.5  199.99  4643.9  194.94  4701.7  193.48  4734.2  190.35  4755.7  186.78
  4785.2  180.29    4788  178.56  4831.3   171.4  4947.1  171.52  4979.5   169.6
  4980.5   167.6  5019.5   167.6  5020.5   169.6  5051.7  172.12  5262.9  174.32
  5313.9  173.09  5484.7  173.25  5577.5     175  5627.9  173.61  5686.6  175.38
  5855.2  176.52  6072.5  179.62  6316.3  179.67  6356.3  181.64  6391.3  179.87
  6464.8  180.53  6543.9  182.52  6619.7  186.35  6700.7  187.72  6872.1  196.66
#Mann= 4 ,-1 , 0
  4578.5     .15       0  4979.5    .045       0  5020.5     .15       0
  5855.2     .11       0
Bank Sta=4979.5,5020.5
XS Rating Curve= 0 ,0
Exp/Cntr=0.3,0.1

Type RM Length L Ch R = 1 ,40700   ,285,285,285
BEGIN DESCRIPTION:
CEDAR CREEK 104.0
END DESCRIPTION:
XS GIS Cut Line= 3
      2055654.36         757180.      2055214.54       757268.33
      2053283.94       757748.42
#Sta/Elev= 30
  4551.4   197.5  4678.6  187.93  4750.9  187.03  4823.5  183.87  4898.3  176.17
  4925.4  170.46  4975.4  170.66  4979.5  168.48  4980.5  166.48  5019.5  166.48
  5020.5  168.48  5026.8  170.67  5167.6  170.24  5192.4  170.74  5211.5   173.2
  5338.4  171.46  5405.2  172.92  5413.4  171.87  5537.5   172.1  5566.1  173.17
  5825.2  172.99  5864.9  174.54    6191  174.57  6199.5  176.06    6224  176.05
  6332.8  178.57  6452.4   178.4  6586.9  181.04  6655.8  184.72  6989.4  193.61
#Mann= 4 ,-1 , 0
  4551.4     .15       0  4979.5    .045       0  5020.5     .15       0
    6224     .11       0
Bank Sta=4979.5,5020.5
XS Rating Curve= 0 ,0
Exp/Cntr=0.5,0.3

Type RM Length L Ch R = 1 ,40415   ,105,105,105
BEGIN DESCRIPTION:
CDC_Railroad (2)-US
END DESCRIPTION:
XS GIS Cut Line= 3
      2056129.46       756783.34      2055281.58       756999.07
      2053336.44       757678.55
#Sta/Elev= 30
  4125.1  202.13  4202.4   203.4  4212.9  201.78  4258.6  201.51  4389.2  196.47
  4455.3  200.61  4563.2  194.28    4606  188.82  4643.5  181.81  4681.6   178.5
  4882.6  172.48  4951.7  172.16  4962.2   170.1    4980     170  4982.5   167.5
  5017.5   167.5    5020     170  5030.4  172.47  5043.6  170.25  5213.2  169.86
  5294.6  172.15  5557.8   171.2  6322.2  174.56  6412.3  177.86  6466.3  177.25
  6797.7  183.18  6967.8  188.26  7036.7  191.72  7050.8  194.99  7060.4  195.11
#Mann= 3 ,-1 , 0
  4125.1     .15       0    4980    .045       0    5020     .15       0
#XS Ineff= 2 , 0
       0    4968  192.16    5032       0  191.26
Permanent Ineff=
       F       F
Bank Sta=4980,5020
XS Rating Curve= 0 ,0
Exp/Cntr=0.5,0.3

Type RM Length L Ch R = 2 ,40360   ,,,
BEGIN DESCRIPTION:
CDC_Railroad (2)-TOR
Structure ID: lds 274
Approximate Survey Structure
END DESCRIPTION:
Bridge Culvert--1,0,-1,-1, 0
Deck Dist Width WeirC Skew NumUp NumDn MinLoCord MaxHiCord MaxSubmerge Is_Ogee
12,81,3,0, 13, 13, , , 0.95, 0, 0,0,,
  3528.1  3825.8  4200.2  4741.9  4991.2  5006.2  5319.8  5635.5  5900.3  6283.4
  6669.2  7041.8  7165.7
  207.24  203.35  199.05  193.74     192     192  191.35  191.26  191.99  194.15
  197.06  201.14  201.84
   147.5   147.5   147.5   147.5   147.5   147.5   147.5   147.5   147.5   147.5
   147.5   147.5   147.5
  3528.1  3825.8  4200.2  4741.9  4991.2  5006.2  5319.8  5635.5  5900.3  6283.4
  6669.2  7041.8  7165.7
  207.24  203.35  199.05  193.74     192     192  191.35  191.26  191.99  194.15
  197.06  201.14  201.84
  147.21  147.21  147.21  147.21  147.21  147.21  147.21  147.21  147.21  147.21
  147.21  147.21  147.21
BR Coef= 1 , 1 , 0 ,1.25, 0 ,,,0.8,0,2,0,
WSPro=,,,, 1 ,,,, 0 ,,,, 0 ,,,,-1 ,-1 ,-1 , 0 , 0 , 0 , 0 , 0
Culvert=1,14,,81,0.024,0.9,1,2,3,168,4993,167.71,4993,Culvert #1  , 0 ,12
Culvert Bottom n=0.024
BC Design=,, 0 ,, 0 ,,,,,,
BC HTab HWMax=203.4
BC Use User HTab Curves=0
BC User HTab FreeFlow(D)= 0

Type RM Length L Ch R = 1 ,40310   ,15,15,15
BEGIN DESCRIPTION:
CDC_Railroad (2)-DS
END DESCRIPTION:
XS GIS Cut Line= 3
      2056596.85       756425.09      2055266.98       756895.43
      2053311.73       757579.62
#Sta/Elev= 30
  3589.4  188.11  3645.4  187.25  3738.5   182.2  3937.3  180.56  3961.7  178.53
  4153.2  181.36  4211.3  180.27    4227  182.75  4258.4  183.67  4457.5  184.65
  4501.7  179.69  4683.1  170.82    4980  169.71  4982.5  167.21  5017.5  167.21
    5020  169.71  5143.9  171.49  5167.6  169.66  5186.6  171.43    5322  172.54
  5750.9  171.66  6027.6  172.73  6102.9  175.17  6291.4  174.45  6408.7  178.03
    6473  177.35  6848.2  184.36  6869.8  186.35  6929.3   186.6  7071.5  195.25
#Mann= 3 ,-1 , 0
  3589.4     .15       0    4980    .045       0    5020     .15       0
#XS Ineff= 2 , 0
       0    4973  192.12    5027       0  191.26
Permanent Ineff=
       F       F
Bank Sta=4980,5020
XS Rating Curve= 0 ,0
Exp/Cntr=0.5,0.3

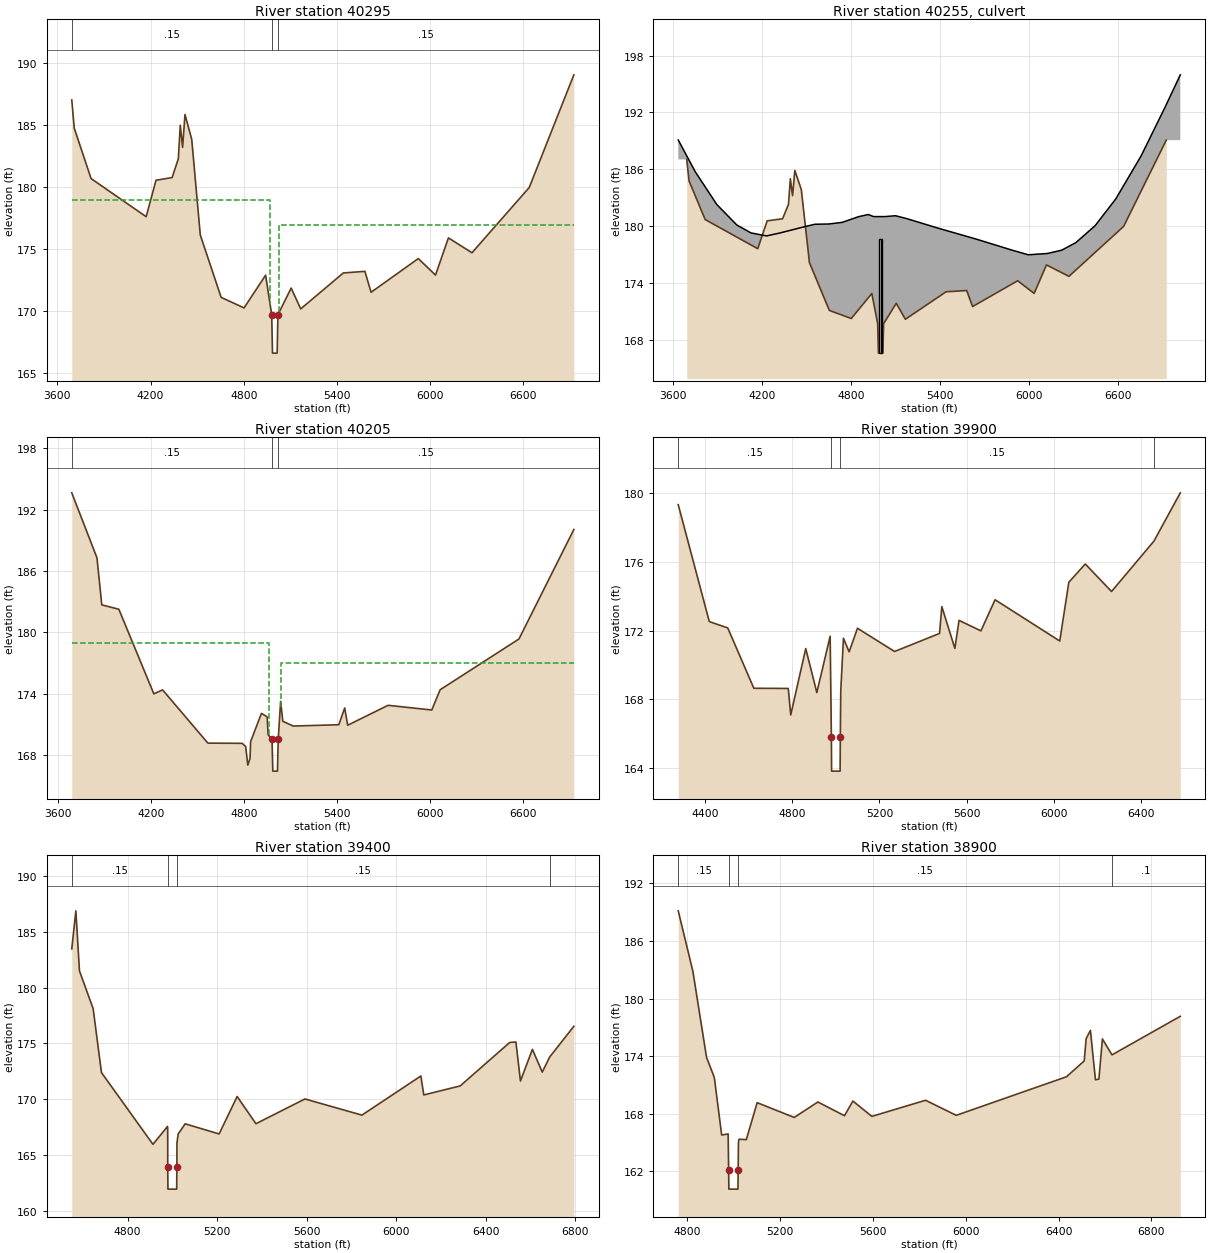
Type RM Length L Ch R = 1 ,40295   ,90,90,90
BEGIN DESCRIPTION:
CDC_Congaree Rd-US
END DESCRIPTION:
XS GIS Cut Line= 3
      2056489.36       756438.02      2055260.39       756881.96
      2053441.72       757511.06
#Sta/Elev= 30
  3693.3  187.05  3709.2  184.78  3817.5  180.71  4172.1  177.63  4235.4  180.57
  4339.2  180.79  4379.1  182.31  4391.6  185.01  4406.5  183.23  4421.9  185.88
  4465.3  183.88  4520.3  176.16  4654.6  171.12  4802.2  170.27  4940.7  172.91
    4980  169.72    4985  166.62    5015  166.62    5020  169.72  5105.1  171.87
  5166.7  170.19    5441  173.09  5579.8  173.22  5619.5  171.53  5923.3  174.25
  6034.3  172.92  6117.3  175.92  6268.9  174.72  6637.6  179.99  6924.4  189.08
#Mann= 3 ,-1 , 0
  3693.3     .15       0    4980    .045       0    5020     .15       0
#XS Ineff= 2 , 0
       0  4970.5  178.98  5029.5       0  176.99
Permanent Ineff=
       F       F
Bank Sta=4980,5020
XS Rating Curve= 0 ,0
Exp/Cntr=0.5,0.3

Type RM Length L Ch R = 2 ,40255   ,,,
BEGIN DESCRIPTION:
CDC_Congaree Rd-TOR
Structure ID: lds 275
Approximate Survey Structure
END DESCRIPTION:
Bridge Culvert--1,0,-1,-1, 0
Deck Dist Width WeirC Skew NumUp NumDn MinLoCord MaxHiCord MaxSubmerge Is_Ogee
19,42,3,0, 29, 29, , , 0.95, 0, 1,1,,
  3636.2  3751.2  3896.2  4031.2  4126.2  4231.2  4321.2  4491.2  4556.2  4651.2
  4741.2  4851.2  4916.2  4952.6  5029.2    5100    5175    5385    5645    5890
    5995    6125    6220    6315    6445    6585    6755    6915  7019.1
   189.1  185.74  182.29  180.13   179.3  178.98  179.29  179.97  180.21  180.24
  180.41  181.01  181.24  181.02  181.02  181.11  180.81  179.81  178.64  177.46
  176.99  177.13  177.48  178.27  180.06   182.9  187.42  192.51  195.97
  146.62  146.62  146.62  146.62  146.62  146.62  146.62  146.62  146.62  146.62
  146.62  146.62  146.62  146.62  146.62  146.62  146.62  146.62  146.62  146.62
  146.62  146.62  146.62  146.62  146.62  146.62  146.62  146.62  146.62
  3636.2  3751.2  3896.2  4031.2  4126.2  4231.2  4321.2  4491.2  4556.2  4651.2
  4741.2  4851.2  4916.2  4952.6  5029.2    5100    5175    5385    5645    5890
    5995    6125    6220    6315    6445    6585    6755    6915  7019.1
   189.1  185.74  182.29  180.13   179.3  178.98  179.29  179.97  180.21  180.24
  180.41  181.01  181.24  181.02  181.02  181.11  180.81  179.81  178.64  177.46
  176.99  177.13  177.48  178.27  180.06   182.9  187.42  192.51  195.97
  146.41  146.41  146.41  146.41  146.41  146.41  146.41  146.41  146.41  146.41
  146.41  146.41  146.41  146.41  146.41  146.41  146.41  146.41  146.41  146.41
  146.41  146.41  146.41  146.41  146.41  146.41  146.41  146.41  146.41
BR Coef= 1 , 1 , 0 ,1.25, 0 ,,,0.8,0,2,0,
WSPro=,,,, 1 ,,,, 0 ,,,, 0 ,,,,-1 ,-1 ,-1 , 0 , 0 , 0 , 0 , 0
Culvert=2,12,10,42,0.012,0.4,1,8,1,166.62,4994.5,166.41,4994.5,Culvert #1  , 0 ,19
Culvert Bottom n=0.012
Culvert=2,12,10,42,0.012,0.4,1,8,1,166.62,5005.5,166.41,5005.5,Culvert #2  , 0 ,19
Culvert Bottom n=0.012
BC Design=,, 0 ,, 0 ,,,,,,
BC HTab HWMax=189.08
BC Use User HTab Curves=0
BC User HTab FreeFlow(D)= 0

Type RM Length L Ch R = 1 ,40205   ,305,305,305
BEGIN DESCRIPTION:
CDC_Congaree Rd-DS
END DESCRIPTION:
XS GIS Cut Line= 3
       2056463.3       756373.77      2055221.02       756801.02
      2053400.13       757439.55
#Sta/Elev= 30
  3686.3  193.64  3849.1  187.28  3880.2  182.68  3990.4  182.25  4216.5  173.97
  4272.9  174.36  4565.6  169.15    4787  169.13  4809.8  168.81  4823.4     167
  4837.9  167.66  4841.5  169.29  4911.5  172.06  4948.4  171.72  4954.8  169.97
    4980  169.51    4985  166.41    5015  166.41    5020  169.51  5035.4  173.24
  5049.5  171.29  5116.9  170.82  5411.4  170.95  5449.4  172.59  5468.6   170.9
  5729.6  172.85  6011.8  172.39  6065.8  174.37  6575.1  179.34  6929.6  190.05
#Mann= 3 ,-1 , 0
  3686.3     .15       0    4980    .045       0    5020     .15       0
#XS Ineff= 2 , 0
       0  4960.5  178.98  5039.5       0  176.99
Permanent Ineff=
       F       F
Bank Sta=4980,5020
XS Rating Curve= 0 ,0
Exp/Cntr=0.5,0.3

Type RM Length L Ch R = 1 ,39900   ,500,500,500
BEGIN DESCRIPTION:
CEDAR CREEK 97.0
END DESCRIPTION:
XS GIS Cut Line= 4
      2056035.39       756496.67      2055545.28        756575.9
      2055320.22       756555.05      2053744.84       756449.72
#Sta/Elev= 30
  4277.5  179.32  4419.9  172.52  4504.5  172.15  4624.1  168.64  4781.8  168.63
  4793.2  167.09    4862  170.95  4912.8  168.39  4973.9  171.67  4979.5  165.82
  4980.5  163.82  5019.5  163.82  5020.5  165.82  5022.5  168.49  5034.8  171.55
  5060.8  170.76  5099.1  172.13  5269.2  170.78  5475.2  171.83  5485.8  173.39
  5545.5  170.96  5564.7  172.59    5665  171.98  5729.8  173.79  6026.3  171.39
    6068  174.81  6143.3  175.87  6263.7  174.27    6458   177.2  6578.9  180.01
#Mann= 4 ,-1 , 0
  4277.5     .15       0  4979.5    .045       0  5020.5     .15       0
    6458      .1       0
Bank Sta=4979.5,5020.5
XS Rating Curve= 0 ,0
Exp/Cntr=0.3,0.1

Type RM Length L Ch R = 1 ,39400   ,500,500,500
BEGIN DESCRIPTION:
CEDAR CREEK 96.0
END DESCRIPTION:
XS GIS Cut Line= 3
      2056131.58       756228.45      2055682.26       756220.19
      2053896.46       756040.68
#Sta/Elev= 30
  4550.6  183.48  4568.9  186.89    4585   181.5  4646.1  178.12  4683.3  172.38
  4913.5  165.94  4978.5  167.54  4979.4  167.42  4979.5  163.92  4980.5  161.92
  5019.5  161.92  5020.5  163.92  5020.7  166.05  5026.1  166.86  5057.5  167.78
  5209.2  166.87  5289.8  170.23  5373.8  167.79  5592.9  170.01  5847.5  168.56
    6111  172.07  6124.1  170.37  6286.7  171.18  6508.2  175.08  6535.9  175.12
  6556.2  171.62  6609.6  174.46  6653.7  172.42    6687  173.78  6794.8  176.53
#Mann= 4 ,-1 , 0
  4550.6     .15       0  4979.5    .045       0  5020.5     .15       0
    6687      .1       0
Bank Sta=4979.5,5020.5
XS Rating Curve= 0 ,0
Exp/Cntr=0.3,0.1

Type RM Length L Ch R = 1 ,38900   ,470,470,470
BEGIN DESCRIPTION:
CEDAR CREEK 95.0
END DESCRIPTION:
XS GIS Cut Line= 3
      2055952.45       755931.99      2055720.75       755879.82
      2053796.79       755902.78
#Sta/Elev= 30
  4762.5  189.15  4825.7  182.83  4884.4  173.88  4917.9  171.78  4949.5  165.79
  4977.4   165.9  4979.5  162.15  4980.5  160.15  5019.5  160.15  5020.5  162.15
  5021.7  164.99  5024.2  165.35  5055.6  165.31  5102.3  169.16  5261.8  167.62
  5363.8  169.23  5478.3   167.8  5514.5  169.33  5596.1  167.73  5827.3  169.41
  5959.4  167.84  6434.2  171.86  6510.4  173.51  6518.7  175.83  6537.1  176.69
  6558.8  171.54  6573.6  171.62  6588.7   175.8    6630  174.14  6924.1  178.16
#Mann= 4 ,-1 , 0
  4762.5     .15       0  4979.5    .045       0  5020.5     .15       0
    6630      .1       0
Bank Sta=4979.5,5020.5
XS Rating Curve= 0 ,0
Exp/Cntr=0.3,0.1

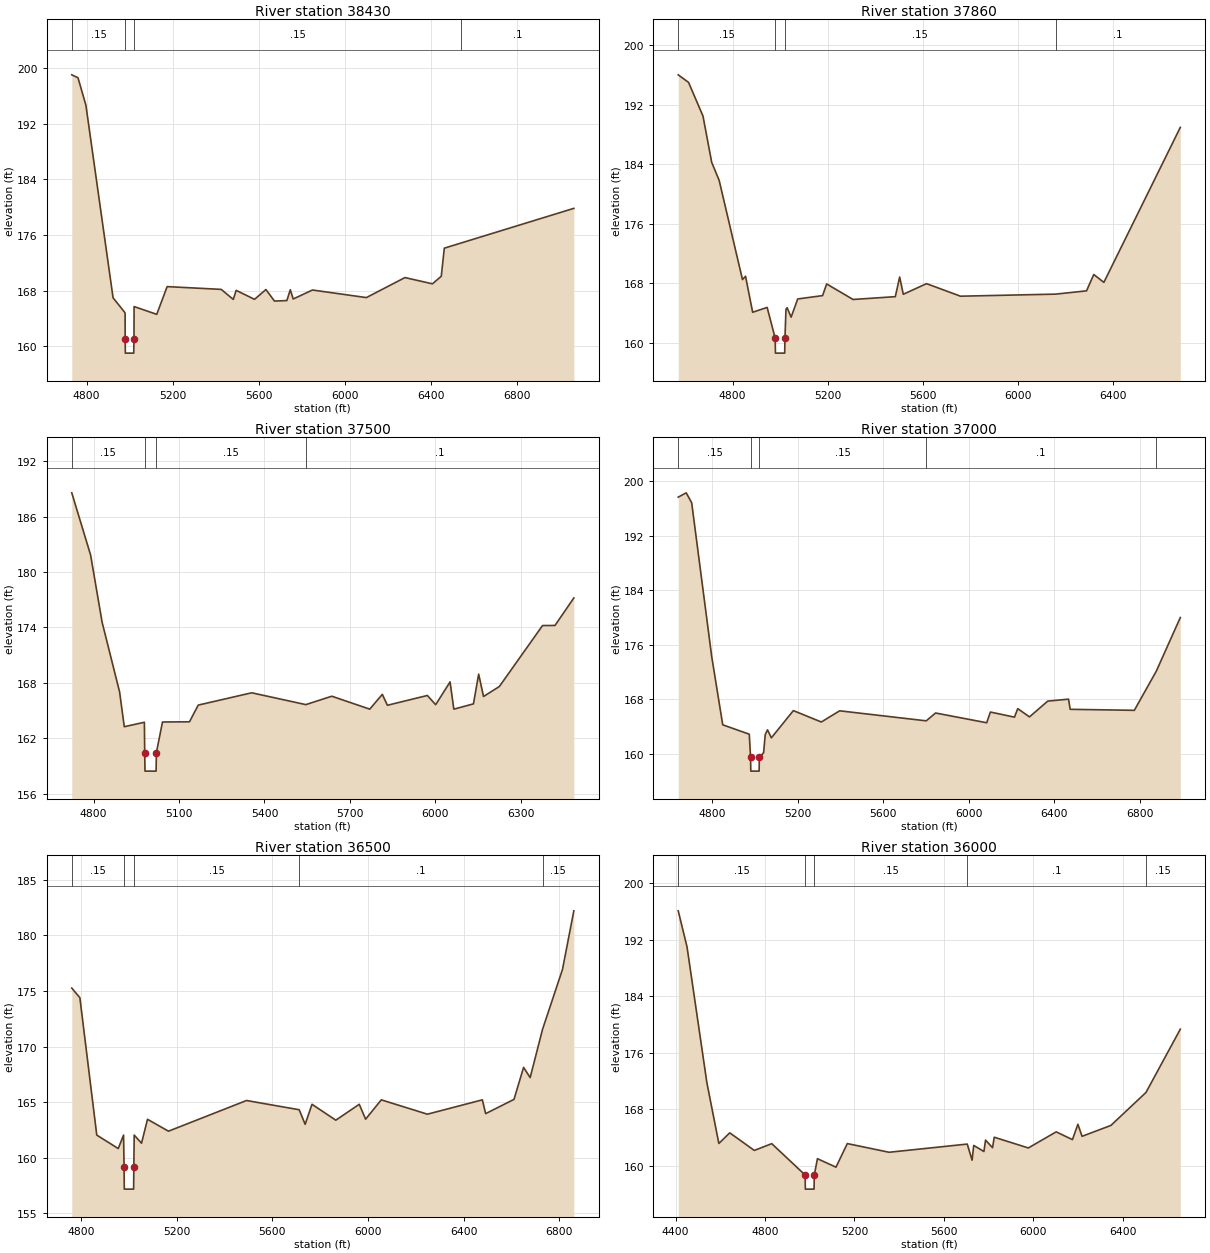
Type RM Length L Ch R = 1 ,38430   ,570,570,570
BEGIN DESCRIPTION:
CEDAR CREEK 94.0
END DESCRIPTION:
XS GIS Cut Line= 3
      2056176.81       755509.53      2055908.63       755522.76
      2053844.37       755511.05
#Sta/Elev= 30
  4731.5  199.03  4760.4  198.61  4797.1  194.67  4923.4  166.95  4978.2  164.83
  4979.4  164.65  4979.5  160.99  4980.5  158.99  5019.5  158.99  5020.5  160.99
  5021.1  165.69  5126.3  164.57  5174.7  168.56  5425.9  168.16  5481.9  166.72
  5495.5  168.02  5580.6  166.73  5633.6  168.14  5673.4  166.48  5730.9  166.55
  5746.9  168.11  5760.4  166.78  5849.9  168.07  6100.4  166.98  6279.6  169.86
  6407.3  168.96  6448.3  170.05  6462.5  174.09  6539.1  174.82  7064.3  179.82
#Mann= 4 ,-1 , 0
  4731.5     .15       0  4979.5    .045       0  5020.5     .15       0
  6539.1      .1       0
Bank Sta=4979.5,5020.5
XS Rating Curve= 0 ,0
Exp/Cntr=0.3,0.1

Type RM Length L Ch R = 1 ,37860   ,360,360,360
BEGIN DESCRIPTION:
CEDAR CREEK 93.0
END DESCRIPTION:
XS GIS Cut Line= 3
       2056020.4       755127.24      2055594.45       755174.84
        2053910.       755161.21
#Sta/Elev= 30
  4571.4  196.04  4614.9  195.02  4675.6  190.49  4712.2  184.27  4743.6  181.84
  4841.8  168.49  4854.7  168.93  4884.6  164.09  4945.6  164.74  4979.5  160.59
  4980.5  158.59  5019.5  158.59  5020.5  160.59  5024.9  164.49  5029.7   164.7
  5046.5  163.43  5074.3  165.88    5179  166.33    5196   167.9  5307.2  165.81
  5485.1  166.19  5503.3  168.83  5518.6  166.51  5616.4  167.94  5759.4  166.25
  6159.6  166.53  6289.8  166.97  6320.3  169.17  6362.8  168.11  6684.5  188.97
#Mann= 4 ,-1 , 0
  4571.4     .15       0  4979.5    .045       0  5020.5     .15       0
  6159.6      .1       0
Bank Sta=4979.5,5020.5
XS Rating Curve= 0 ,0
Exp/Cntr=0.3,0.1

Type RM Length L Ch R = 1 ,37500   ,500,500,500
BEGIN DESCRIPTION:
CEDAR CREEK 92.0
END DESCRIPTION:
XS GIS Cut Line= 4
      2055846.08       754916.67      2055578.13       754848.03
      2054851.98       754802.31      2054095.73       754863.44
#Sta/Elev= 30
  4723.4  188.57  4789.6  181.83    4830  174.55  4891.3  167.02  4907.8  163.25
  4978.4  163.73  4979.5  160.44  4980.5  158.44  5019.5  158.44  5020.5  160.44
    5042  163.76  5136.7  163.78  5167.6  165.59  5355.2  166.92  5545.3  165.64
  5636.4  166.55  5769.7  165.15  5813.8  166.75  5831.7  165.57    5972  166.63
  6001.1  165.63  6051.7   168.1  6064.9  165.15  6133.8  165.72  6152.1  168.94
  6169.2  166.52  6224.7   167.6  6376.4   174.2  6420.1  174.21  6486.3  177.19
#Mann= 4 ,-1 , 0
  4723.4     .15       0  4979.5    .045       0  5020.5     .15       0
  5545.3      .1       0
Bank Sta=4979.5,5020.5
XS Rating Curve= 0 ,0
Exp/Cntr=0.3,0.1

Type RM Length L Ch R = 1 ,37000   ,500,500,500
BEGIN DESCRIPTION:
CEDAR CREEK 91.0
END DESCRIPTION:
XS GIS Cut Line= 4
      2056165.31       754378.87      2055811.95       754442.27
       2055422.6       754503.41       2053828.5       754584.93
#Sta/Elev= 30
    4641  197.65  4678.3  198.28  4703.9  196.83  4797.7  174.27  4849.2  164.28
  4973.4   162.9  4979.5  159.49  4980.5  157.49  5019.5  157.49  5020.5  159.49
  5040.5  160.19  5048.1  162.84  5058.8  163.54  5076.8  162.37  5179.7  166.36
  5310.5  164.69  5396.3  166.33  5801.4  164.86  5845.1  166.01  6084.3  164.58
  6101.7  166.15  6214.4   165.4  6229.6  166.65  6284.6  165.44  6369.9  167.75
  6467.2  168.04  6475.1  166.55  6775.1   166.4  6877.8  172.13  6990.3     180
#Mann= 5 ,-1 , 0
    4641     .15       0  4979.5    .045       0  5020.5     .15       0
  5801.4      .1       0  6877.8     .15       0
Bank Sta=4979.5,5020.5
XS Rating Curve= 0 ,0
Exp/Cntr=0.3,0.1

Type RM Length L Ch R = 1 ,36500   ,500,500,500
BEGIN DESCRIPTION:
CEDAR CREEK 90.0
END DESCRIPTION:
XS GIS Cut Line= 3
       2055932.1       754048.28      2055694.88       754017.54
      2053837.55       754134.33
#Sta/Elev= 30
  4760.8  175.26  4794.7   174.4  4865.4  162.04  4955.2  160.83  4977.5  162.04
  4979.5  159.18  4980.5  157.18  5019.5  157.18  5020.5  159.18  5021.9  162.04
  5052.6  161.31  5077.6  163.46  5165.3  162.39  5491.7  165.15  5712.2  164.32
  5737.1  163.01  5765.7  164.81  5865.3  163.38  5963.4  164.81    5990  163.47
  6055.5  165.21  6248.4  163.92  6478.3  165.21  6492.1  163.97  6610.6  165.25
  6650.8  168.13  6678.3  167.21  6729.9  171.54  6813.5  176.94    6861  182.21
#Mann= 5 ,-1 , 0
  4760.8     .15       0  4979.5    .045       0  5020.5     .15       0
  5712.2      .1       0  6729.9     .15       0
Bank Sta=4979.5,5020.5
XS Rating Curve= 0 ,0
Exp/Cntr=0.3,0.1

Type RM Length L Ch R = 1 ,36000   ,500,500,500
BEGIN DESCRIPTION:
CEDAR CREEK 89.0
END DESCRIPTION:
XS GIS Cut Line= 3
      2056249.11       753479.93      2055667.22       753566.57
      2054009.62       753614.66
#Sta/Elev= 30
  4411.7  196.08  4451.2  190.95  4539.9  171.74  4593.4  163.14  4642.3  164.64
  4752.2  162.15  4830.1  163.11  4979.5  158.67  4980.5  156.67  5019.5  156.67
  5020.5  158.67  5034.6  160.98  5117.6  159.78  5168.2  163.12  5355.3  161.89
    5705  163.05  5726.6  160.77  5733.9  162.86  5779.5     162  5786.8  163.61
  5818.1  162.54  5825.8  164.02  5978.3   162.5  6102.9  164.78  6175.7  163.68
    6200  165.85  6218.7  164.15  6347.7  165.69  6504.7  170.36  6658.3  179.32
#Mann= 5 ,-1 , 0
  4411.7     .15       0  4979.5    .045       0  5020.5     .15       0
    5705      .1       0  6504.7     .15       0
Bank Sta=4979.5,5020.5
XS Rating Curve= 0 ,0
Exp/Cntr=0.3,0.1