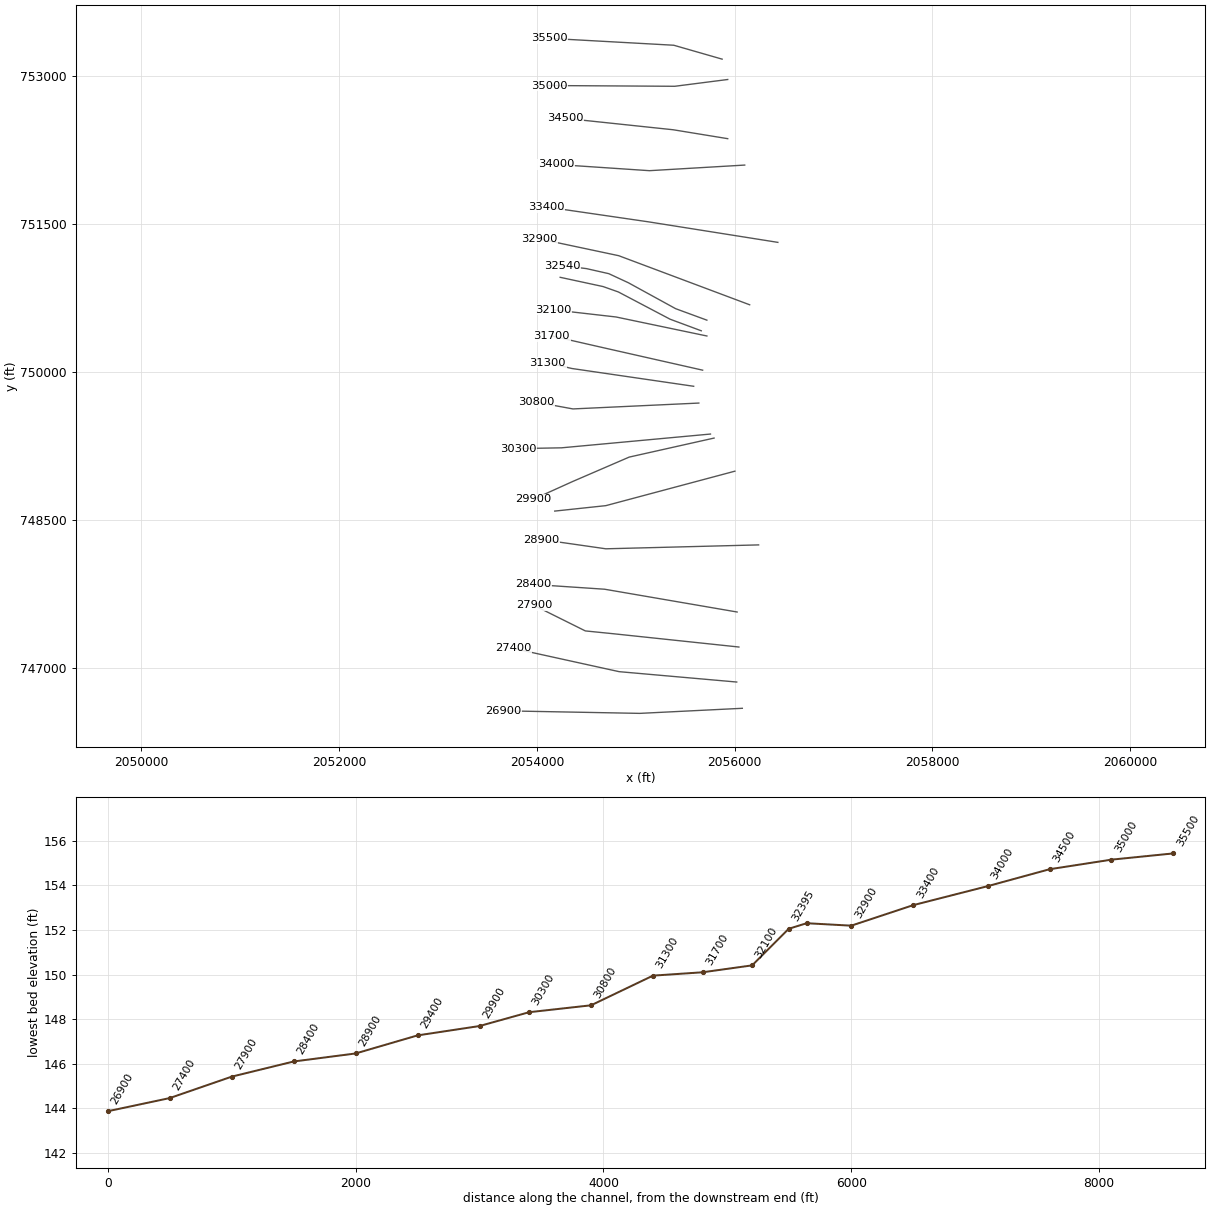
HEC-RAS study Cedar Creek.prj: Cedar Creek Limited Detail Study

--- Cedar Creek.g04 (geometry) --- (continued)

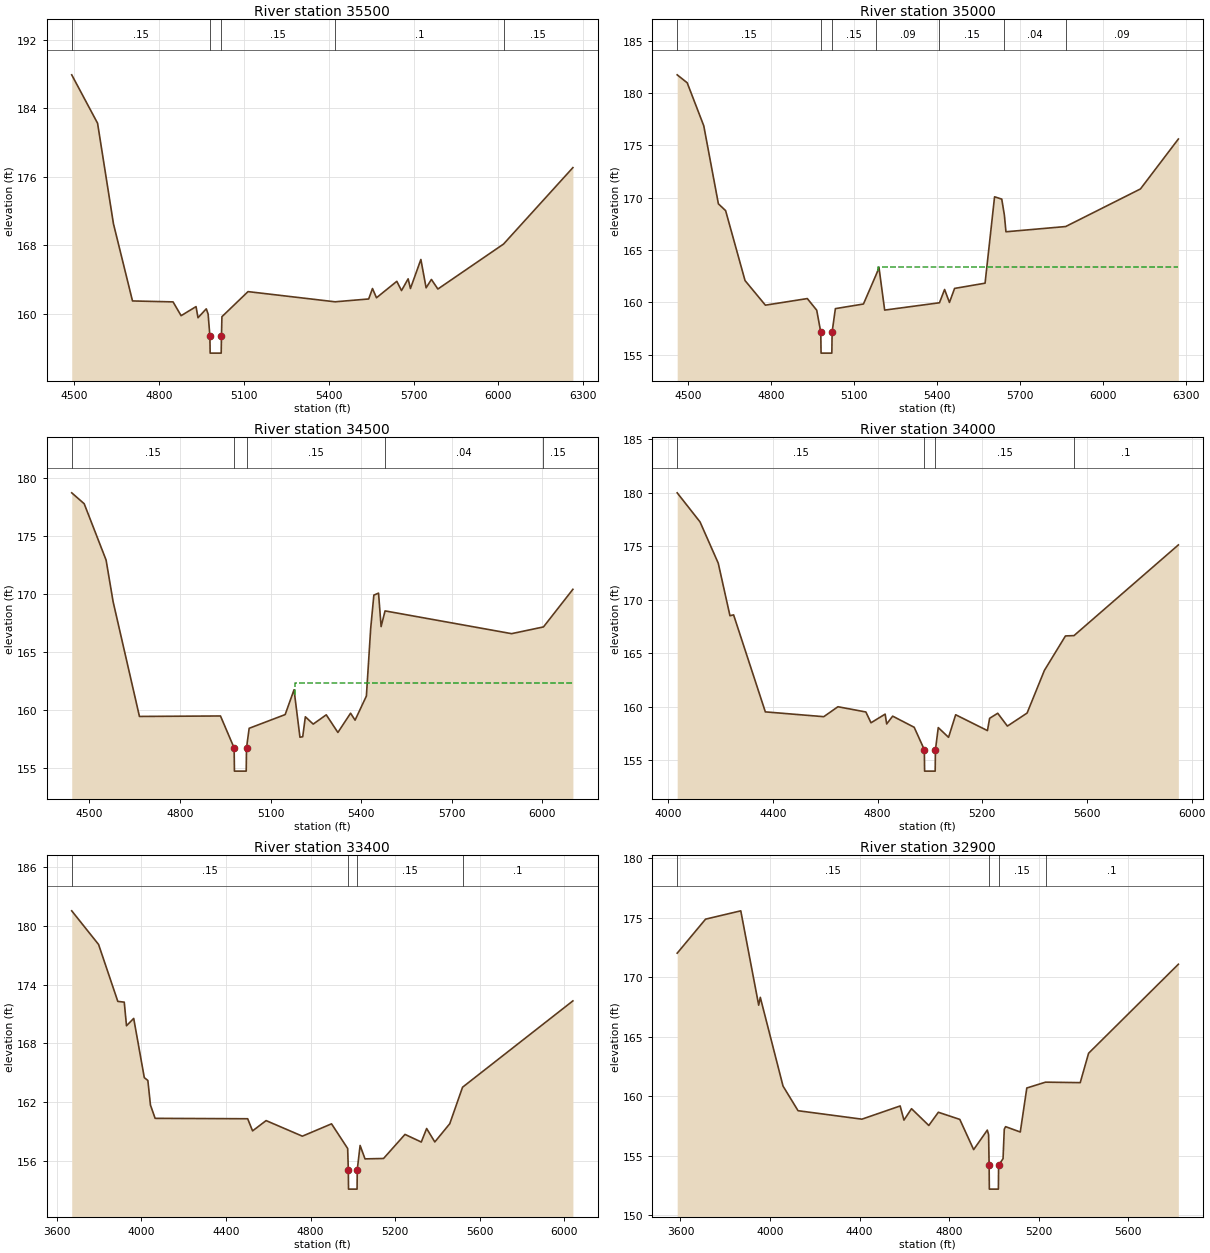
Type RM Length L Ch R = 1 ,35500   ,500,500,500
BEGIN DESCRIPTION:
CEDAR CREEK 88.0
END DESCRIPTION:
XS GIS Cut Line= 3
      2055873.24       753166.31      2055384.08       753307.03
      2054122.91        753376.9
#Sta/Elev= 30
    4491  187.91  4582.4  182.26  4638.6  170.52  4705.9  161.52  4849.3  161.41
  4877.8   159.8  4930.6  160.86  4937.5  159.56  4966.8   160.6  4973.3  159.99
  4979.5  157.43  4980.5  155.43  5019.5  155.43  5020.5  157.43  5022.1  159.68
  5114.4  162.61  5422.2  161.42    5541  161.75  5554.5  162.97  5568.6  161.89
  5640.5  163.81  5657.1  162.73  5680.5   164.1  5688.7  162.97  5725.6  166.36
  5744.1  163.05  5762.8  164.03  5785.7  162.91  6017.9  168.16  6263.1  177.08
#Mann= 5 ,-1 , 0
    4491     .15       0  4979.5    .045       0  5020.5     .15       0
  5422.2      .1       0  6017.9     .15       0
Bank Sta=4979.5,5020.5
XS Rating Curve= 0 ,0
Exp/Cntr=0.3,0.1

Type RM Length L Ch R = 1 ,35000   ,500,500,500
BEGIN DESCRIPTION:
CEDAR CREEK 87.0
END DESCRIPTION:
XS GIS Cut Line= 3
      2055929.78       752960.26      2055394.07       752891.57
      2054120.59       752899.13
#Sta/Elev= 30
  4459.9  181.73  4496.1  180.97  4556.1  176.86    4609  169.41  4635.1  168.76
  4705.4  162.08  4779.1  159.73  4930.8  160.36  4964.8  159.25  4979.5  157.15
  4980.5  155.15  5019.5  155.15  5020.5  157.15  5032.3   159.4  5133.9  159.84
  5179.5  162.62  5190.2  163.31  5210.7  159.26    5409  159.96  5427.5  161.23
  5445.1  159.99  5463.7  161.33    5574  161.83  5608.4  170.08  5634.4  169.86
  5643.9  168.33  5649.6  166.74  5865.7  167.24  6136.3  170.83  6273.5   175.6
#Mann= 7 ,-1 , 0
  4459.9     .15       0  4979.5    .045       0  5020.5     .15       0
  5179.5     .09       0    5409     .15       0  5643.9     .04       0
  5865.7     .09       0
#XS Ineff= 2 , 0
       0                    5185       0   163.4
Permanent Ineff=
       F       F
Bank Sta=4979.5,5020.5
XS Rating Curve= 0 ,0
Exp/Cntr=0.3,0.1

Type RM Length L Ch R = 1 ,34500   ,500,500,500
BEGIN DESCRIPTION:
CEDAR CREEK 86.0
END DESCRIPTION:
XS GIS Cut Line= 3
      2055929.81       752361.35      2055378.83       752451.49
      2054283.65        752567.4
#Sta/Elev= 30
  4441.7  178.69    4483  177.75  4555.5   172.9  4578.8  169.31    4666  159.43
  4934.3  159.47  4979.5  156.72  4980.5  154.72  5019.5  154.72  5020.5  156.72
  5029.3  158.41  5148.5  159.59  5177.9  161.73  5197.5  157.64  5206.6  157.68
  5215.4   159.4  5241.3  158.77  5284.6  159.57  5323.1  158.05  5365.1  159.71
    5380  159.11  5417.5  161.19  5431.7  167.01  5442.2  169.88  5457.7  170.05
  5466.2  167.17  5479.3  168.52  5898.3  166.56  6003.9  167.14  6101.3  170.38
#Mann= 5 ,-1 , 0
  4441.7     .15       0  4979.5    .045       0  5020.5     .15       0
  5479.3     .04       0  6003.9     .15       0
#XS Ineff= 2 , 0
       0                    5180       0   162.3
Permanent Ineff=
       F       F
Bank Sta=4979.5,5020.5
XS Rating Curve= 0 ,0
Exp/Cntr=0.3,0.1

Type RM Length L Ch R = 1 ,34000   ,600,600,600
BEGIN DESCRIPTION:
CEDAR CREEK 85.0
END DESCRIPTION:
XS GIS Cut Line= 3
      2056101.93       752094.16       2055138.1       752037.39
      2054190.83       752100.94
#Sta/Elev= 30
  4034.5  179.98  4121.8  177.26  4191.4   173.4  4236.1  168.49    4250  168.57
  4371.3   159.5  4594.5  159.05  4648.7  159.98  4755.4  159.49    4775  158.48
  4829.1  159.29  4834.9  158.37  4857.8   159.1    4940  158.06  4978.8  155.96
  4979.8  153.96  5020.2  153.96  5021.2  155.96    5032  158.03  5071.3  157.12
  5098.5  159.23  5219.9  157.75  5228.3   158.9  5259.2  159.37  5296.1  158.17
  5371.4  159.39  5437.6  163.38    5518   166.6  5550.6  166.63  5949.4  175.11
#Mann= 4 ,-1 , 0
  4034.5     .15       0  4978.8    .045       0  5021.2     .15       0
  5550.6      .1       0
Bank Sta=4978.8,5021.2
XS Rating Curve= 0 ,0
Exp/Cntr=0.3,0.1

Type RM Length L Ch R = 1 ,33400   ,500,500,500
BEGIN DESCRIPTION:
CEDAR CREEK 84.0
END DESCRIPTION:
XS GIS Cut Line= 3
      2056437.06       751311.82      2055124.39       751520.15
      2054094.48       751670.29
#Sta/Elev= 30
  3670.9  181.54    3798   178.1  3888.8  172.29  3919.3  172.21  3929.9   169.8
    3964  170.55  4014.1   164.5  4030.9  164.21  4043.2   161.7  4065.3  160.34
  4502.9   160.3  4526.1  159.06    4590  160.11  4761.6  158.52  4899.5  159.78
  4975.8  157.26  4978.8  155.11  4979.8  153.11  5020.2  153.11  5021.2  155.11
  5034.6  157.57  5057.8   156.2  5145.4  156.24  5246.9   158.7  5323.9  157.92
  5349.2   159.3  5387.9  157.93  5458.5  159.79    5519  163.52  6040.8  172.34
#Mann= 4 ,-1 , 0
  3670.9     .15       0  4978.8    .045       0  5021.2     .15       0
    5519      .1       0
Bank Sta=4978.8,5021.2
XS Rating Curve= 0 ,0
Exp/Cntr=0.3,0.1

Type RM Length L Ch R = 1 ,32900   ,360,360,360
BEGIN DESCRIPTION:
CEDAR CREEK 83.0
END DESCRIPTION:
XS GIS Cut Line= 3
      2056151.72       750680.07      2054827.26       751176.93
      2054021.01       751348.04
#Sta/Elev= 30
  3585.4  172.02  3712.1  174.88  3869.4  175.58  3949.5  167.65  3956.6  168.31
  4058.2  160.85  4125.3  158.78  4410.6  158.07  4581.4  159.18  4598.3  157.99
  4632.2  158.95  4709.4  157.54    4752  158.65  4847.8  158.05  4909.7  155.51
  4970.7  157.15  4976.5  156.77  4978.8  154.19  4979.8  152.19  5020.2  152.19
  5021.2  154.19    5041  154.75  5046.5  157.22  5052.4  157.44    5118  156.99
  5147.2  160.69  5230.9  161.18  5385.8  161.14  5423.2  163.61  5824.2  171.09
#Mann= 4 ,-1 , 0
  3585.4     .15       0  4978.8    .045       0  5021.2     .15       0
  5230.9      .1       0
Bank Sta=4978.8,5021.2
XS Rating Curve= 0 ,0
Exp/Cntr=0.5,0.3

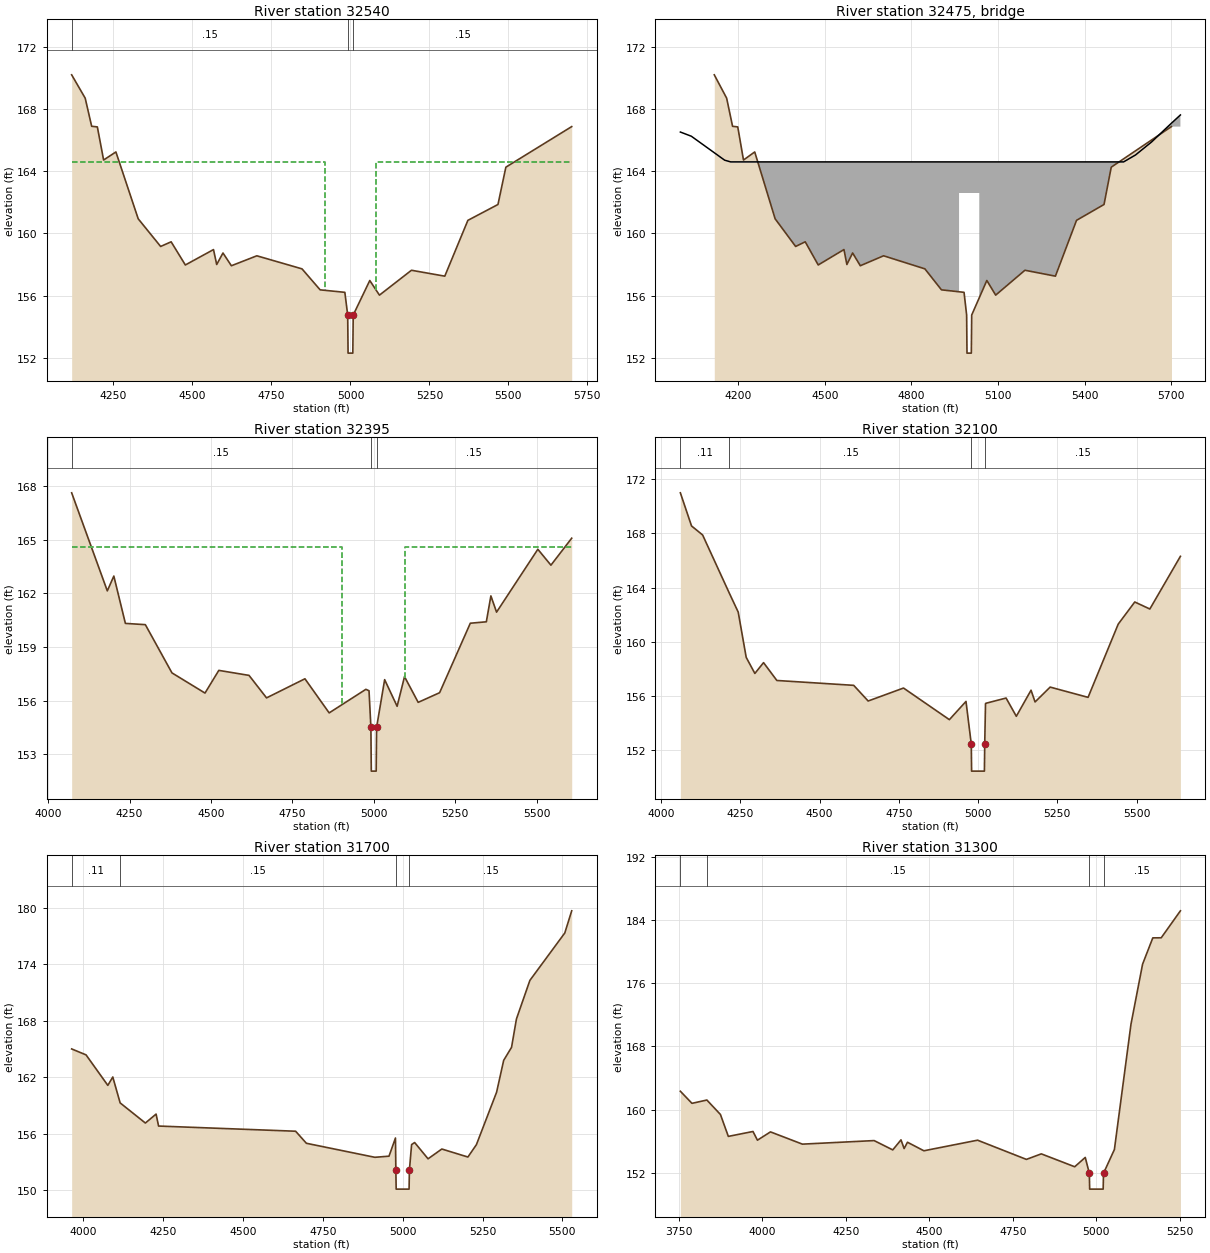
Type RM Length L Ch R = 1 ,32540   ,145,145,145
BEGIN DESCRIPTION:
CDC_Cabin Creek Rd-US
END DESCRIPTION:
XS GIS Cut Line= 6
      2055718.97       750524.51      2055402.95       750640.72
      2054924.62       750903.17      2054726.98         750995.
      2054501.66       751046.02      2054252.26       751077.19
#Sta/Elev= 30
  4117.7   170.2  4160.5   168.7    4181  166.89    4199  166.85  4218.8  164.72
  4257.7  165.24  4328.3  160.94  4399.3  159.16  4432.5  159.46  4477.5  157.97
  4566.6  158.96  4576.7     158  4596.6  158.74  4623.2  157.92  4703.8  158.56
  4846.7  157.72  4904.1  156.37  4982.3  156.21  4991.3  154.75  4992.5   152.3
  5007.5   152.3  5008.8  154.75  5061.2  156.97  5091.8  156.03  5193.1  157.63
  5298.6  157.25  5371.7  160.84  5466.9  161.86  5491.9  164.26  5700.3  166.87
#Mann= 3 ,-1 , 0
  4117.7     .15       0  4991.3    .045       0  5008.8     .15       0
#XS Ineff= 2 , 0
       0    4918   164.6    5082       0   164.6
Permanent Ineff=
       F       F
Bank Sta=4991.3,5008.8
XS Rating Curve= 0 ,0
Exp/Cntr=0.5,0.3

Type RM Length L Ch R = 3 ,32475   ,,,
BEGIN DESCRIPTION:
CDC_Cabin Creek Rd-TOR
Structure ID: lds 276
Approximate Survey Structure
END DESCRIPTION:
Bridge Culvert--1,0,-1,-1, 0
Deck Dist Width WeirC Skew NumUp NumDn MinLoCord MaxHiCord MaxSubmerge Is_Ogee
47,36,3,0, 13, 13, , , 0.95, 0, 1,1,,
  4000.3  4038.3  4153.6  4174.4    4965    4965    5035    5035  5534.7  5576.2
  5631.4  5698.6  5731.3
  166.52  166.25  164.71   164.6   164.6   164.6   164.6   164.6   164.6  165.05
  165.88  167.06  167.62
   132.3   132.3   132.3   132.3   132.3   162.6   162.6   132.3   132.3   132.3
   132.3   132.3   132.3
  4000.3  4038.3  4153.6  4174.4    4965    4965    5035    5035  5534.7  5576.2
  5631.4  5698.6  5731.3
  166.52  166.25  164.71   164.6   164.6   164.6   164.6   164.6   164.6  165.05
  165.88  167.06  167.62
   132.3   132.3   132.3   132.3   132.3   162.6   162.6   132.3   132.3   132.3
   132.3   132.3   132.3
Abutment Skew #Up #Dn= , 2 , 2
    4965    4985
   162.6  156.09
    4965    4985
   162.6  156.54
Abutment Skew #Up #Dn= , 2 , 2
    5015    5035
  154.62   162.6
    5015    5035
  154.66   162.6
BR Coef= 1 , 1 , 0 ,1.25, 0 ,,,0.8,0,2,0,
WSPro=,,,, 1 ,,,, 0 ,,,, 0 ,,,,-1 ,-1 ,-1 , 0 , 0 , 0 , 0 , 0
BC Design=,, 0 ,, 0 ,,,,,,
BC HTab HWMax=170.2
BC Use User HTab Curves=0
BC User HTab FreeFlow(D)= 0

Type RM Length L Ch R = 1 ,32395   ,295,295,295
BEGIN DESCRIPTION:
CDC_Cabin Creek Rd-DS
END DESCRIPTION:
XS GIS Cut Line= 5
      2055662.28       750416.81      2055346.26       750534.43
      2054823.89       750809.78      2054668.88       750864.62
      2054235.28       750958.15
#Sta/Elev= 30
  4072.3  167.63  4181.8  162.14  4201.8  162.97  4237.3  160.32  4298.6  160.25
  4380.3  157.55  4481.8  156.42  4524.2  157.69    4617  157.41  4670.8  156.15
  4788.7  157.22  4863.1  155.31  4975.9  156.63  4985.5  156.55  4991.3   154.5
  4992.5  152.05  5007.5  152.05  5008.8   154.5  5033.5  157.17  5071.8  155.68
  5094.5  157.34  5136.5   155.9  5202.3  156.44  5296.6  160.33  5345.8  160.41
  5359.8  161.86  5377.2  160.95    5504  164.47  5544.2  163.58    5608  165.09
#Mann= 3 ,-1 , 0
  4072.3     .15       0  4991.3    .045       0  5008.8     .15       0
#XS Ineff= 2 , 0
       0    4903   164.6    5097       0   164.6
Permanent Ineff=
       F       F
Bank Sta=4991.3,5008.8
XS Rating Curve= 0 ,0
Exp/Cntr=0.5,0.3

Type RM Length L Ch R = 1 ,32100   ,400,400,400
BEGIN DESCRIPTION:
CEDAR CREEK 79.0
END DESCRIPTION:
XS GIS Cut Line= 3
      2055719.23        750364.2      2054800.26       750556.62
      2054165.89       750629.12
#Sta/Elev= 30
  4061.1  171.01  4096.3  168.56  4131.3  167.89    4216  163.56  4243.6  162.18
  4268.8  158.83  4296.1  157.64  4323.5  158.44  4365.5  157.12  4607.9  156.76
  4653.5   155.6    4765  156.56  4909.7  154.22  4962.1  155.57  4978.8  152.41
  4979.8  150.41  5020.2  150.41  5021.2  152.41  5023.7  155.41  5024.6  155.43
  5088.6  155.82  5120.9  154.47  5167.3   156.4    5180  155.53  5227.6  156.63
  5347.2  155.87  5442.3  161.29  5494.5  162.93  5542.1  162.41  5638.5  166.31
#Mann= 4 ,-1 , 0
  4061.1     .11       0    4216     .15       0  4978.8    .045       0
  5021.2     .15       0
Bank Sta=4978.8,5021.2
XS Rating Curve= 0 ,0
Exp/Cntr=0.3,0.1

Type RM Length L Ch R = 1 ,31700   ,400,400,400
BEGIN DESCRIPTION:
CEDAR CREEK 78.0
END DESCRIPTION:
XS GIS Cut Line= 3
       2055676.2       750018.21      2054665.94       750246.83
      2054150.02       750364.65
#Sta/Elev= 30
  3964.2  164.99  4009.2  164.36  4077.4  161.12  4092.9  162.01  4115.9  159.26
  4194.9  157.12  4228.4  158.07  4236.2   156.8  4665.1  156.25  4698.8  154.97
  4913.1  153.48  4957.4   153.6  4977.6  155.53  4978.8   152.1  4979.8   150.1
  5020.2   150.1  5021.2   152.1  5028.1  154.83  5037.6  155.05  5079.6  153.32
  5122.7  154.36  5204.3  153.51  5230.9  154.82  5294.1  160.39  5316.3  163.78
  5340.9  165.16  5356.2  168.17  5398.3  172.27  5507.6  177.31  5529.2  179.66
#Mann= 4 ,-1 , 0
  3964.2     .11       0  4115.9     .15       0  4978.8    .045       0
  5021.2     .15       0
Bank Sta=4978.8,5021.2
XS Rating Curve= 0 ,0
Exp/Cntr=0.3,0.1

Type RM Length L Ch R = 1 ,31300   ,500,500,500
BEGIN DESCRIPTION:
CEDAR CREEK 77.0
END DESCRIPTION:
XS GIS Cut Line= 3
      2055585.58       749855.18      2054353.86       750035.14
      2054109.29       750092.92
#Sta/Elev= 30
  3755.2  162.33  3789.9   160.8  3834.5  161.22  3875.1  159.39  3898.7  156.62
  3972.5  157.24  3985.8  156.14  4024.8  157.19  4120.3  155.64  4334.9  156.09
  4390.7  154.91  4415.3  156.18  4424.7  155.08  4434.7  155.88  4483.8   154.8
  4644.4  156.14  4790.5  153.71  4835.1  154.41  4935.1  152.78  4966.6  153.96
  4978.8  151.95  4979.8  149.95  5020.2  149.95  5021.2  151.95  5053.8  154.96
  5103.4  170.81  5138.1   178.4  5168.7  181.73  5193.9  181.74  5251.3  185.15
#Mann= 4 ,-1 , 0
  3755.2     .11       0  3834.5     .15       0  4978.8    .045       0
  5021.2     .15       0
Bank Sta=4978.8,5021.2
XS Rating Curve= 0 ,0
Exp/Cntr=0.3,0.1

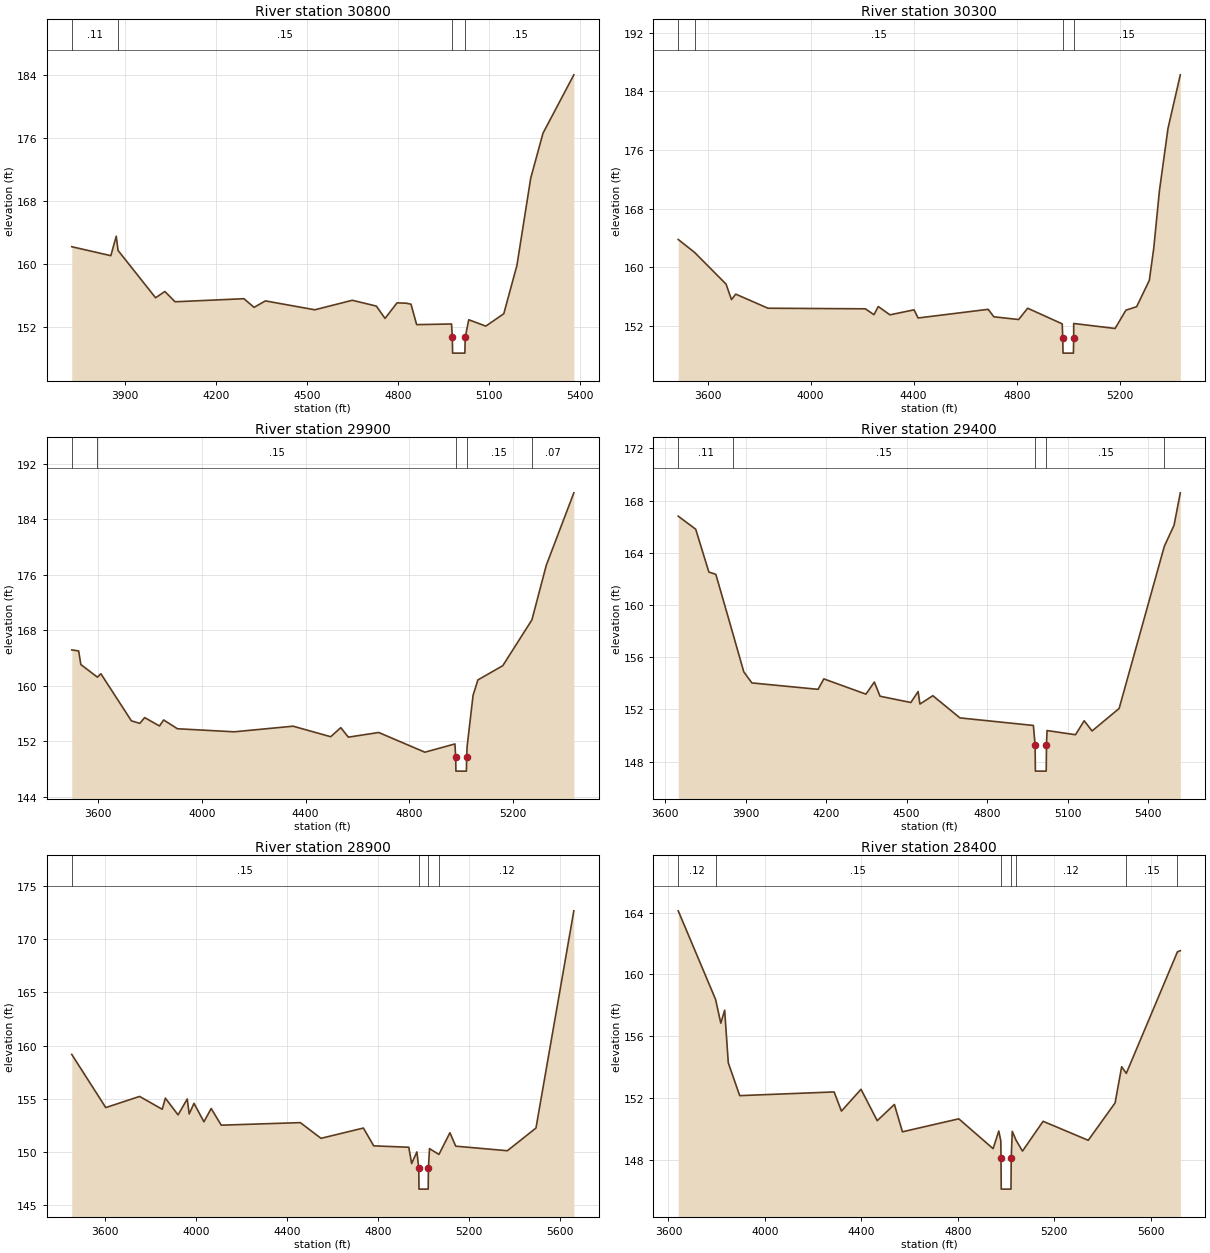
Type RM Length L Ch R = 1 ,30800   ,500,500,500
BEGIN DESCRIPTION:
CEDAR CREEK 76.0
END DESCRIPTION:
XS GIS Cut Line= 3
      2055637.74       749685.35      2054364.52       749625.97
      2053991.64       749694.38
#Sta/Elev= 30
  3725.4  162.17  3854.1  161.03  3871.9  163.51  3877.8   161.7  4001.5  155.67
    4032  156.47  4065.6  155.16  4292.5  155.55  4325.8  154.45  4363.3  155.27
    4526  154.14  4649.4  155.35  4728.6  154.61  4757.2  153.04  4796.7  155.02
  4826.5  154.98  4842.8  154.85  4861.3  152.25  4976.2  152.33  4978.8  150.62
  4979.8  148.62  5020.2  148.62  5021.2  150.62    5033  152.87  5089.1  152.06
  5148.4  153.64  5191.6  159.79  5237.1  170.91  5277.6  176.63  5379.1  184.06
#Mann= 4 ,-1 , 0
  3725.4     .11       0  3877.8     .15       0  4978.8    .045       0
  5021.2     .15       0
Bank Sta=4978.8,5021.2
XS Rating Curve= 0 ,0
Exp/Cntr=0.3,0.1

Type RM Length L Ch R = 1 ,30300   ,400,400,400
BEGIN DESCRIPTION:
CEDAR CREEK 75.0
END DESCRIPTION:
XS GIS Cut Line= 3
      2055755.42       749371.73      2054247.76       749232.27
      2053812.63       749224.55
#Sta/Elev= 30
  3485.9   163.8  3549.6  162.03  3671.7  157.71  3692.6  155.61  3709.2  156.35
  3834.3  154.43  4212.3  154.35  4245.8  153.55  4262.5  154.66  4307.9  153.53
  4401.5  154.21  4417.2   153.1  4689.2  154.28  4711.3  153.26  4807.4  152.89
  4842.6  154.43  4976.7   152.3  4978.8  150.31  4979.8  148.31  5020.2  148.31
  5021.2  150.31  5021.3  152.35    5182  151.67  5223.9  154.16  5265.7  154.64
  5314.9  158.23    5332  162.58  5354.2  170.46  5387.4  178.94  5435.2  186.24
#Mann= 4 ,-1 , 0
  3485.9     .11       0  3549.6     .15       0  4978.8    .045       0
  5021.2     .15       0
Bank Sta=4978.8,5021.2
XS Rating Curve= 0 ,0
Exp/Cntr=0.3,0.1

Type RM Length L Ch R = 1 ,29900   ,500,500,500
BEGIN DESCRIPTION:
CEDAR CREEK 74.0
END DESCRIPTION:
XS GIS Cut Line= 4
      2055791.69       749330.98       2054933.5       749138.51
      2054362.51       748891.83      2053966.61       748712.81
#Sta/Elev= 30
  3498.5  165.17    3525  165.02  3533.5  163.06  3597.5  161.24  3610.8  161.73
  3728.5  154.94  3760.9  154.58  3779.6  155.41  3836.8   154.2  3852.6  155.07
    3906   153.8  4124.9  153.36    4352  154.17  4496.9  152.65  4535.8  153.96
    4565  152.59  4682.1  153.26  4860.1  150.42    4976  151.61  4978.8  149.69
  4979.8  147.69  5020.2  147.69  5021.2  149.69    5023  151.25  5045.9  158.62
  5064.5  160.84  5160.4  162.89  5272.8   169.5  5328.1  177.36  5434.5  187.82
#Mann= 5 ,-1 , 0
  3498.5     .11       0  3597.5     .15       0  4978.8    .045       0
  5021.2     .15       0  5272.8     .07       0
Bank Sta=4978.8,5021.2
XS Rating Curve= 0 ,0
Exp/Cntr=0.3,0.1

Type RM Length L Ch R = 1 ,29400   ,500,500,500
BEGIN DESCRIPTION:
CEDAR CREEK 73.0
END DESCRIPTION:
XS GIS Cut Line= 3
      2056002.31       748995.87      2054697.21       748647.11
      2054180.34       748591.94
#Sta/Elev= 30
  3649.1  166.81  3714.2  165.81  3763.2  162.53  3789.3  162.35  3852.6  157.82
  3893.3  154.88  3923.6  154.03  4170.2  153.54  4191.5  154.34  4348.5  153.17
  4379.9   154.1    4401  153.01  4515.7  152.53    4543  153.37  4549.6  152.41
  4597.8  153.05  4698.7  151.35  4972.4  150.77  4978.8  149.27  4979.8  147.27
  5020.2  147.27  5021.2  149.27  5023.2  150.38  5129.3  150.06  5161.6  151.13
    5191  150.35  5291.8  152.07  5460.2   164.5  5496.4  166.11  5519.8   168.6
#Mann= 5 ,-1 , 0
  3649.1     .11       0  3852.6     .15       0  4978.8    .045       0
  5021.2     .15       0  5460.2     .07       0
Bank Sta=4978.8,5021.2
XS Rating Curve= 0 ,0
Exp/Cntr=0.3,0.1

Type RM Length L Ch R = 1 ,28900   ,500,500,500
BEGIN DESCRIPTION:
CEDAR CREEK 72.0
END DESCRIPTION:
XS GIS Cut Line= 3
      2056242.24       748249.75      2054697.04        748210.3
      2054043.64       748304.09
#Sta/Elev= 30
  3454.3  159.16  3603.6  154.15  3752.4   155.2  3851.7  153.99  3865.5  155.04
  3921.3  153.46  3961.6  154.96  3970.1  153.55  3991.4  154.55  4034.9  152.81
  4066.8  154.06    4111  152.49  4458.5  152.73  4549.3  151.25  4735.5  152.22
  4780.9  150.54    4935  150.41  4947.5  148.87  4970.6  149.97  4978.8  148.46
  4979.8  146.46  5020.2  146.46  5021.2  148.46    5026  150.28  5067.4  149.73
  5115.7  151.78  5141.2  150.51  5368.1  150.08  5493.7  152.22  5660.1   172.7
#Mann= 4 ,-1 , 0
  3454.3     .15       0  4978.8    .045       0  5021.2     .15       0
  5067.4     .12       0
Bank Sta=4978.8,5021.2
XS Rating Curve= 0 ,0
Exp/Cntr=0.3,0.1

Type RM Length L Ch R = 1 ,28400   ,500,500,500
BEGIN DESCRIPTION:
CEDAR CREEK 71.0
END DESCRIPTION:
XS GIS Cut Line= 3
       2056024.9       747570.45       2054685.1       747801.08
      2053964.42       747849.43
#Sta/Elev= 30
  3640.5  164.11  3795.3  158.38    3817  156.84    3833  157.68  3848.1  154.27
  3895.4  152.15  4286.9  152.39  4317.2  151.15  4398.4  152.56  4465.6  150.53
  4536.8  151.58  4570.2  149.81  4803.8  150.65    4946  148.72  4969.6  149.86
  4978.1  149.22  4978.8   148.1  4979.8   146.1  5020.2   146.1  5021.2   148.1
  5025.5  149.84  5041.5  149.26  5067.9  148.56  5153.4  150.49  5340.5  149.26
  5451.9  151.68  5479.1  154.02  5498.3  153.59  5710.5  161.46  5722.3  161.53
#Mann= 7 ,-1 , 0
  3640.5     .12       0  3795.3     .15       0  4978.8    .045       0
  5021.2     .15       0  5041.5     .12       0  5498.3     .15       0
  5710.5     .12       0
Bank Sta=4978.8,5021.2
XS Rating Curve= 0 ,0
Exp/Cntr=0.3,0.1

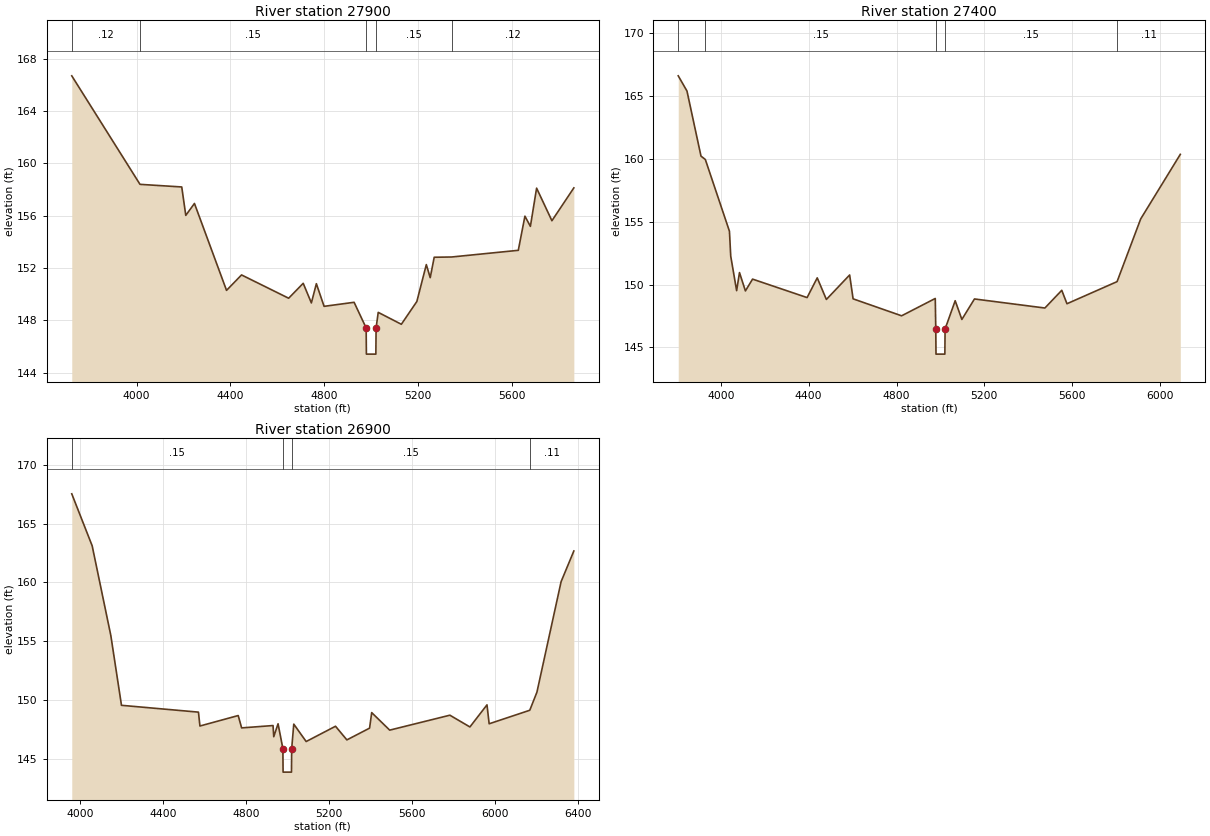
Type RM Length L Ch R = 1 ,27900   ,500,500,500
BEGIN DESCRIPTION:
CEDAR CREEK 70.0
END DESCRIPTION:
XS GIS Cut Line= 4
      2056043.02       747216.08      2054773.51       747350.47
      2054489.69       747379.11      2053971.15       747637.25
#Sta/Elev= 30
  3723.4  166.68  4014.4  158.39  4192.4  158.19  4209.6  156.02  4246.6  156.93
  4383.4  150.29  4447.4  151.47  4648.3  149.69  4710.4  150.83  4745.2  149.33
  4766.5   150.8  4799.4  149.07  4927.4  149.38  4978.8  147.42  4979.8  145.42
  5020.2  145.42  5021.2  147.42  5030.3  148.61  5128.9   147.7    5195  149.44
  5235.4  152.26    5252  151.26    5269  152.82  5343.5  152.84  5627.6  153.35
  5655.9  155.96  5679.2  155.18  5705.7   158.1    5771  155.61  5864.5  158.12
#Mann= 5 ,-1 , 0
  3723.4     .12       0  4014.4     .15       0  4978.8    .045       0
  5021.2     .15       0  5343.5     .12       0
Bank Sta=4978.8,5021.2
XS Rating Curve= 0 ,0
Exp/Cntr=0.3,0.1

Type RM Length L Ch R = 1 ,27400   ,500,500,500
BEGIN DESCRIPTION:
CEDAR CREEK 69.0
END DESCRIPTION:
XS GIS Cut Line= 3
      2056020.97       746861.71      2054831.79       746966.67
       2053765.1       747201.36
#Sta/Elev= 30
  3806.2  166.61    3846   165.4  3909.8  160.22  3929.6  159.95  4039.4  154.24
  4045.2  152.26  4072.1  149.51  4085.1  150.95  4112.1  149.49  4144.6  150.43
  4392.9  148.96  4439.1  150.53  4480.7  148.81  4586.6  150.76  4602.4  148.86
  4823.2  147.51  4976.5  148.89  4978.8  146.46  4979.8  144.46  5020.2  144.46
  5021.2  146.46  5067.2  148.71  5097.6  147.22    5155  148.85  5475.6  148.13
  5552.5  149.54  5576.1  148.47  5804.3  150.23  5911.8  155.22  6092.2  160.36
#Mann= 5 ,-1 , 0
  3806.2     .12       0  3929.6     .15       0  4978.8    .045       0
  5021.2     .15       0  5804.3     .11       0
Bank Sta=4978.8,5021.2
XS Rating Curve= 0 ,0
Exp/Cntr=0.3,0.1

Type RM Length L Ch R = 1 ,26900   ,500,500,500
BEGIN DESCRIPTION:
CEDAR CREEK 68.0
END DESCRIPTION:
XS GIS Cut Line= 3
      2056077.55       746595.93      2055040.63       746544.52
      2053660.37       746570.46
#Sta/Elev= 30
  3961.8  167.53  4060.1  163.11  4149.9  155.49  4201.3  149.55  4572.1  148.97
  4579.2  147.79  4763.6  148.68  4780.1  147.63  4931.4  147.83  4934.8  146.88
  4955.6  147.98  4978.8  145.87  4979.8  143.87  5020.2  143.87  5021.2  145.87
  5031.3  147.95    5091  146.47  5232.4  147.77  5287.1  146.61  5396.5  147.61
  5406.7  148.93  5493.4  147.44  5783.3  148.71  5879.8  147.71  5962.1  149.59
  5972.5  147.98  6168.2  149.13  6202.7  150.67  6319.1  160.06  6380.5  162.67
#Mann= 4 ,-1 , 0
  3961.8     .15       0  4978.8    .045       0  5021.2     .15       0
  6168.2     .11       0
Bank Sta=4978.8,5021.2
XS Rating Curve= 0 ,0
Exp/Cntr=0.3,0.1