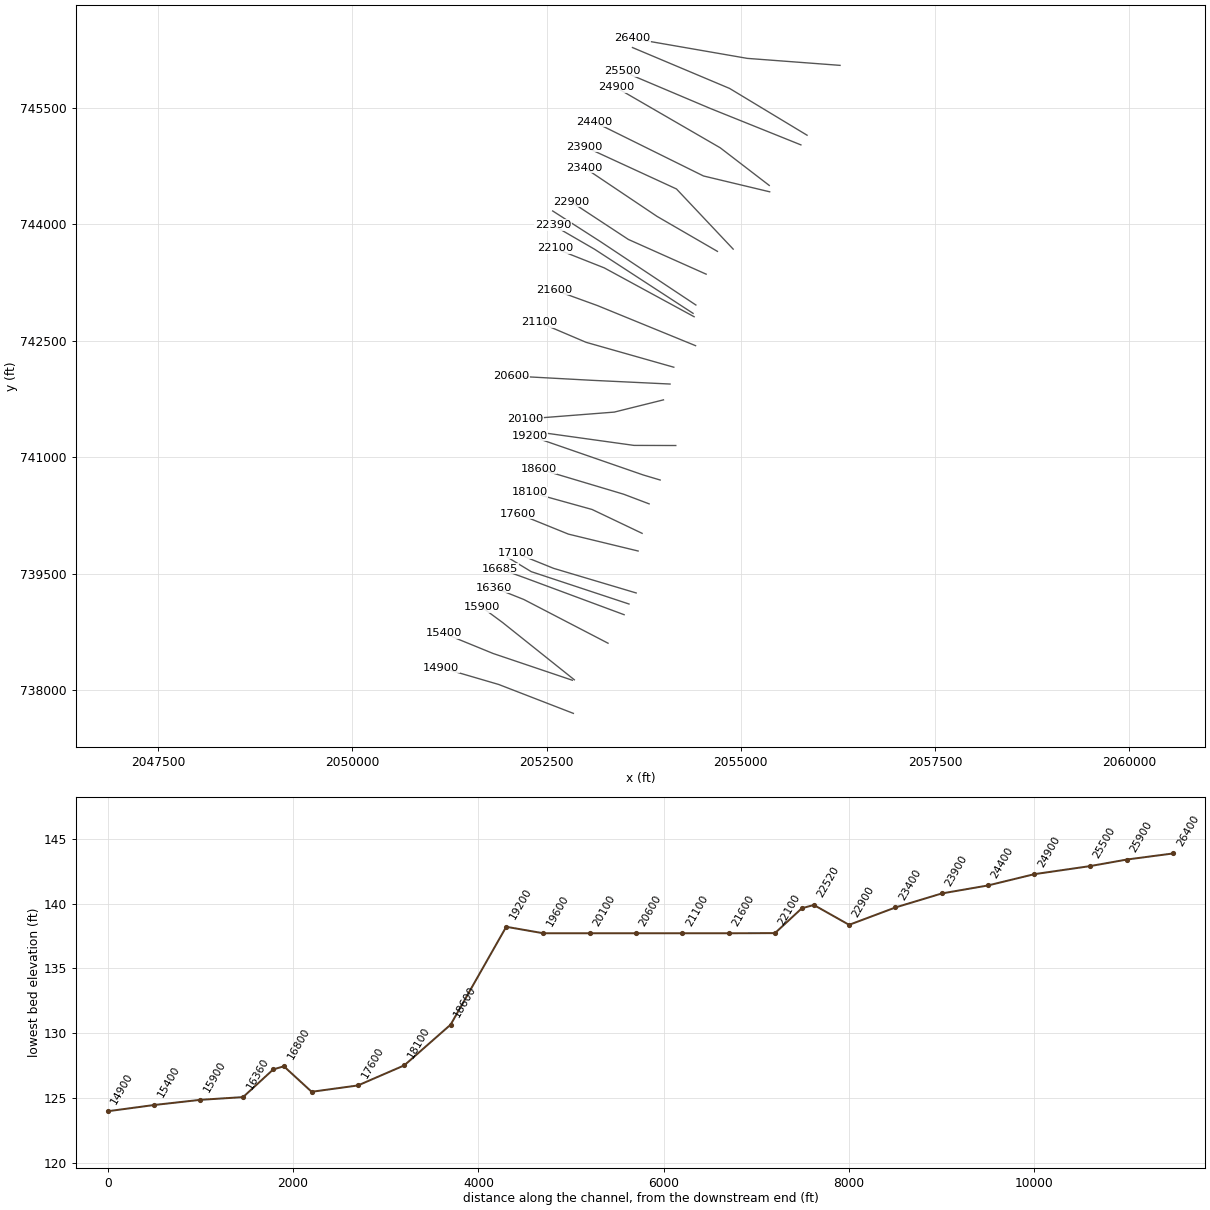
HEC-RAS study Cedar Creek.prj: Cedar Creek Limited Detail Study

--- Cedar Creek.g04 (geometry) --- (continued)

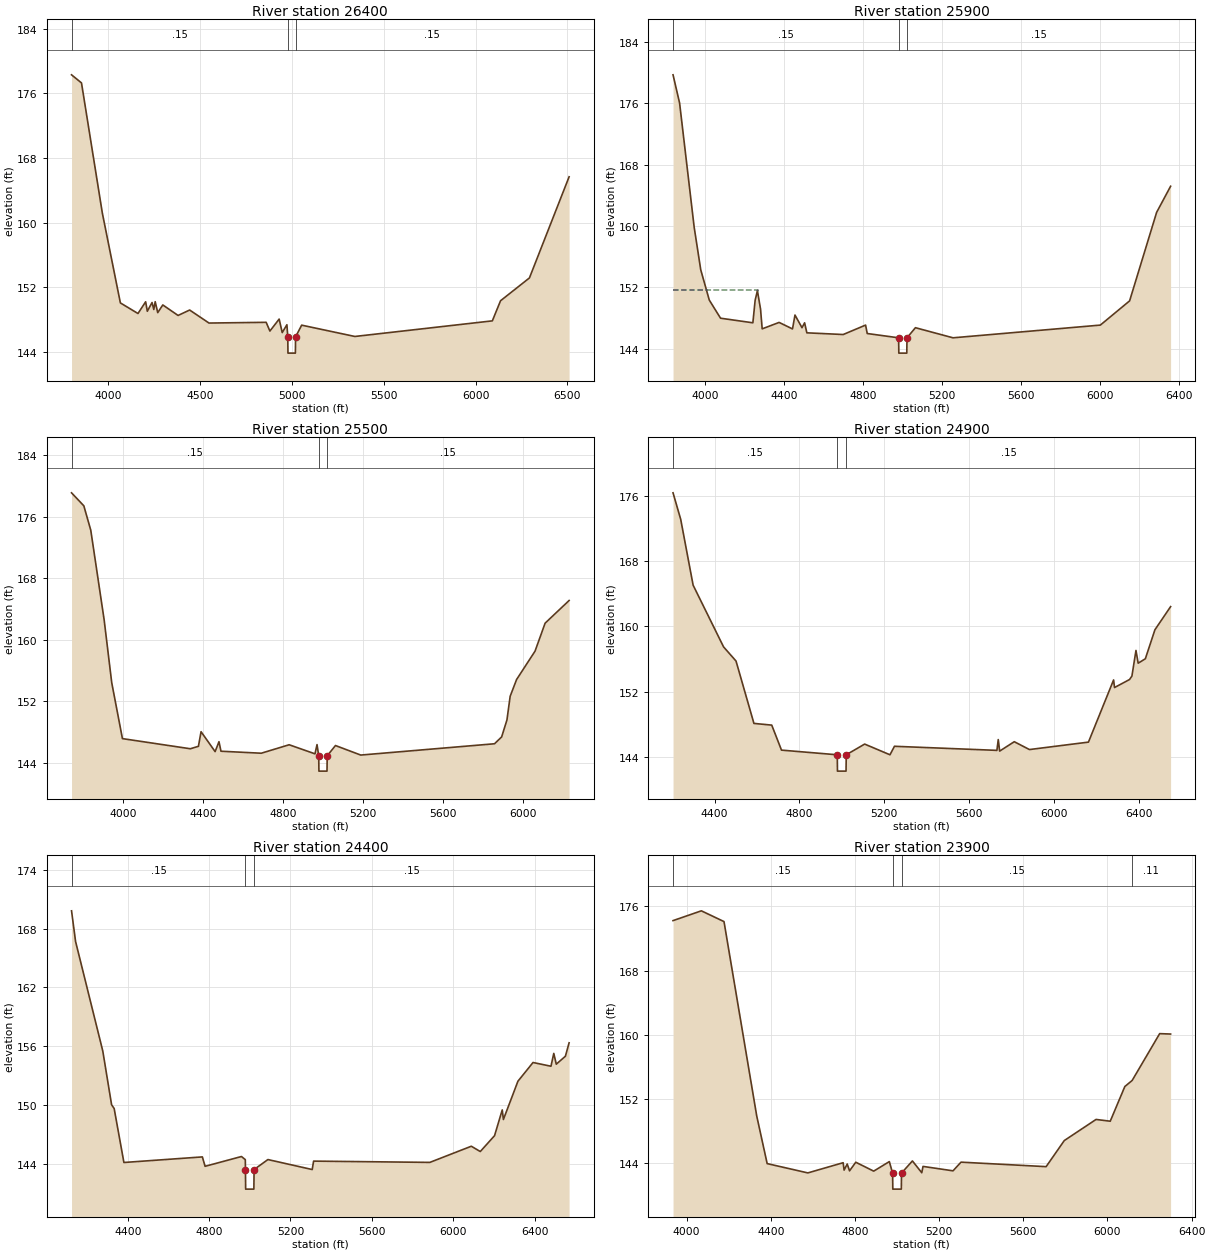
Type RM Length L Ch R = 1 ,26400   ,500,500,500
BEGIN DESCRIPTION:
CEDAR CREEK 67.0
END DESCRIPTION:
XS GIS Cut Line= 3
      2056278.48       746046.83      2055084.67       746136.83
      2053598.11       746394.97
#Sta/Elev= 30
  3802.8  178.29  3856.9  177.29  3970.3  161.19  4068.4  150.08  4164.1  148.77
  4205.8  150.22  4214.9  149.05  4240.7  150.13  4250.1  149.27  4257.8  150.23
  4271.6  148.88  4299.1  149.83  4382.1  148.53  4445.2   149.2  4550.3  147.59
  4861.3  147.68  4881.6   146.6  4931.9  148.08  4948.6  146.41  4974.1  147.38
  4978.8  145.87  4979.8  143.87  5020.2  143.87  5021.2  145.87  5054.3  147.33
  5343.6  145.93  6091.3  147.86  6136.1  150.35  6293.1  153.17  6508.8  165.68
#Mann= 3 ,-1 , 0
  3802.8     .15       0  4978.8    .045       0  5021.2     .15       0
Bank Sta=4978.8,5021.2
XS Rating Curve= 0 ,0
Exp/Cntr=0.3,0.1

Type RM Length L Ch R = 1 ,25900   ,400,400,400
BEGIN DESCRIPTION:
CEDAR CREEK 66.0
END DESCRIPTION:
XS GIS Cut Line= 3
      2055853.96       745147.03      2054857.32       745749.35
      2053606.63       746276.36
#Sta/Elev= 30
  3835.5  179.74  3868.7  176.06  3942.7  159.82    3976  154.27  4019.2  150.33
  4076.2  147.96  4240.1  147.36  4251.6   150.3  4263.1  151.55  4278.9  149.16
  4287.3  146.57  4373.1  147.41    4441  146.56  4453.5  148.37  4489.1  146.72
  4502.3  147.36  4513.7  146.05    4698  145.83  4811.4  147.06  4819.7  145.96
  4978.8   145.4  4979.8   143.4  5020.2   143.4  5021.2   145.4    5064  146.72
  5254.5   145.4  6001.1  147.06  6149.4  150.22  6286.4  161.78  6357.2  165.19
#Mann= 3 ,-1 , 0
  3835.5     .15       0  4978.8    .045       0  5021.2     .15       0
#XS Ineff= 2 , 0
       0    4265   151.6               0
Permanent Ineff=
       F       F
Bank Sta=4978.8,5021.2
XS Rating Curve= 0 ,0
Exp/Cntr=0.3,0.1

Type RM Length L Ch R = 1 ,25500   ,600,600,600
BEGIN DESCRIPTION:
CEDAR CREEK 65.0
END DESCRIPTION:
XS GIS Cut Line= 3
      2055774.74       745022.49      2054609.13       745491.43
      2053476.35       745970.71
#Sta/Elev= 30
  3743.6   179.1    3805  177.41  3839.7  174.24  3906.5  162.58  3944.4   154.4
  3997.9  147.12  4337.3   145.8  4377.7  146.12  4390.8  148.02  4461.1  145.43
  4480.4  146.72  4490.3  145.48  4691.6  145.22  4831.1  146.32  4960.2  145.14
  4970.3  146.34  4978.8  144.89  4979.8  142.89  5020.2  142.89  5021.2  144.89
  5062.5  146.22  5188.8  144.98  5857.3  146.45  5892.9  147.34  5919.4  149.55
  5935.5  152.63  5967.6  154.81  6059.8   158.5  6110.1  162.14    6230  165.09
#Mann= 3 ,-1 , 0
  3743.6     .15       0  4978.8    .045       0  5021.2     .15       0
Bank Sta=4978.8,5021.2
XS Rating Curve= 0 ,0
Exp/Cntr=0.3,0.1

Type RM Length L Ch R = 1 ,24900   ,500,500,500
BEGIN DESCRIPTION:
CEDAR CREEK 64.0
END DESCRIPTION:
XS GIS Cut Line= 3
      2055367.15       744500.26      2054736.13       744984.98
      2053394.31       745762.66
#Sta/Elev= 30
  4204.3  176.33  4240.4  173.09    4299  165.03  4442.5  157.48  4501.4  155.74
  4585.8  148.11  4669.8   147.9  4715.8  144.84  4978.8  144.27  4979.8  142.27
  5020.2  142.27  5021.2  144.27    5108  145.58  5227.4  144.27  5248.6  145.31
  5731.7  144.81  5738.1  146.13  5744.7  144.72  5813.6  145.87  5885.2  144.91
  6163.5  145.82  6282.1  153.43  6286.5   152.5  6357.2  153.48  6368.5   153.9
  6387.6  157.04    6398  155.48  6431.8  156.02    6477  159.57  6550.9   162.4
#Mann= 3 ,-1 , 0
  4204.3     .15       0  4978.8    .045       0  5021.2     .15       0
Bank Sta=4978.8,5021.2
XS Rating Curve= 0 ,0
Exp/Cntr=0.3,0.1

Type RM Length L Ch R = 1 ,24400   ,500,500,500
BEGIN DESCRIPTION:
CEDAR CREEK 63.0
END DESCRIPTION:
XS GIS Cut Line= 3
      2055372.77        744418.2      2054520.82       744622.05
      2053114.09       745318.28
#Sta/Elev= 30
    4124  169.82  4143.8  166.69  4277.6   155.5  4320.8  150.02  4333.5  149.63
  4381.4  144.12    4767  144.69  4780.4  143.73  4959.2  144.73  4978.1  144.41
  4978.8   143.4  4979.8   141.4  5020.2   141.4  5021.2   143.4  5089.2  144.42
  5306.9   143.4  5313.8  144.26  5885.2  144.13  6088.9  145.78  6133.1  145.24
  6203.2  146.86    6241  149.49  6246.7  148.51  6318.1  152.42  6392.3  154.33
  6480.5  153.95  6494.3  155.26  6506.6  154.16  6551.4  154.97  6569.6  156.34
#Mann= 3 ,-1 , 0
    4124     .15       0  4978.8    .045       0  5021.2     .15       0
Bank Sta=4978.8,5021.2
XS Rating Curve= 0 ,0
Exp/Cntr=0.3,0.1

Type RM Length L Ch R = 1 ,23900   ,500,500,500
BEGIN DESCRIPTION:
CEDAR CREEK 62.0
END DESCRIPTION:
XS GIS Cut Line= 3
      2054902.95         743680.       2054172.9       744454.86
      2052992.38       744999.01
#Sta/Elev= 30
  3935.4  174.23    4070  175.45  4177.6  174.11  4333.2  149.88  4382.7  143.96
    4576   142.8  4743.8  144.07  4748.3  143.15  4763.1  143.91  4774.2  143.06
  4803.8  144.13    4889  143.02  4963.2  144.21  4978.8  142.78  4979.8  140.78
  5020.2  140.78  5021.2  142.78    5073  144.29  5117.5  142.82  5123.3  143.61
    5266  143.06  5303.9  144.14  5708.4  143.58  5794.7  146.83  5945.6  149.46
  6013.1  149.24  6082.4  153.56  6117.3  154.32    6248  160.15  6299.9   160.1
#Mann= 4 ,-1 , 0
  3935.4     .15       0  4978.8    .045       0  5021.2     .15       0
  6117.3     .11       0
Bank Sta=4978.8,5021.2
XS Rating Curve= 0 ,0
Exp/Cntr=0.3,0.1

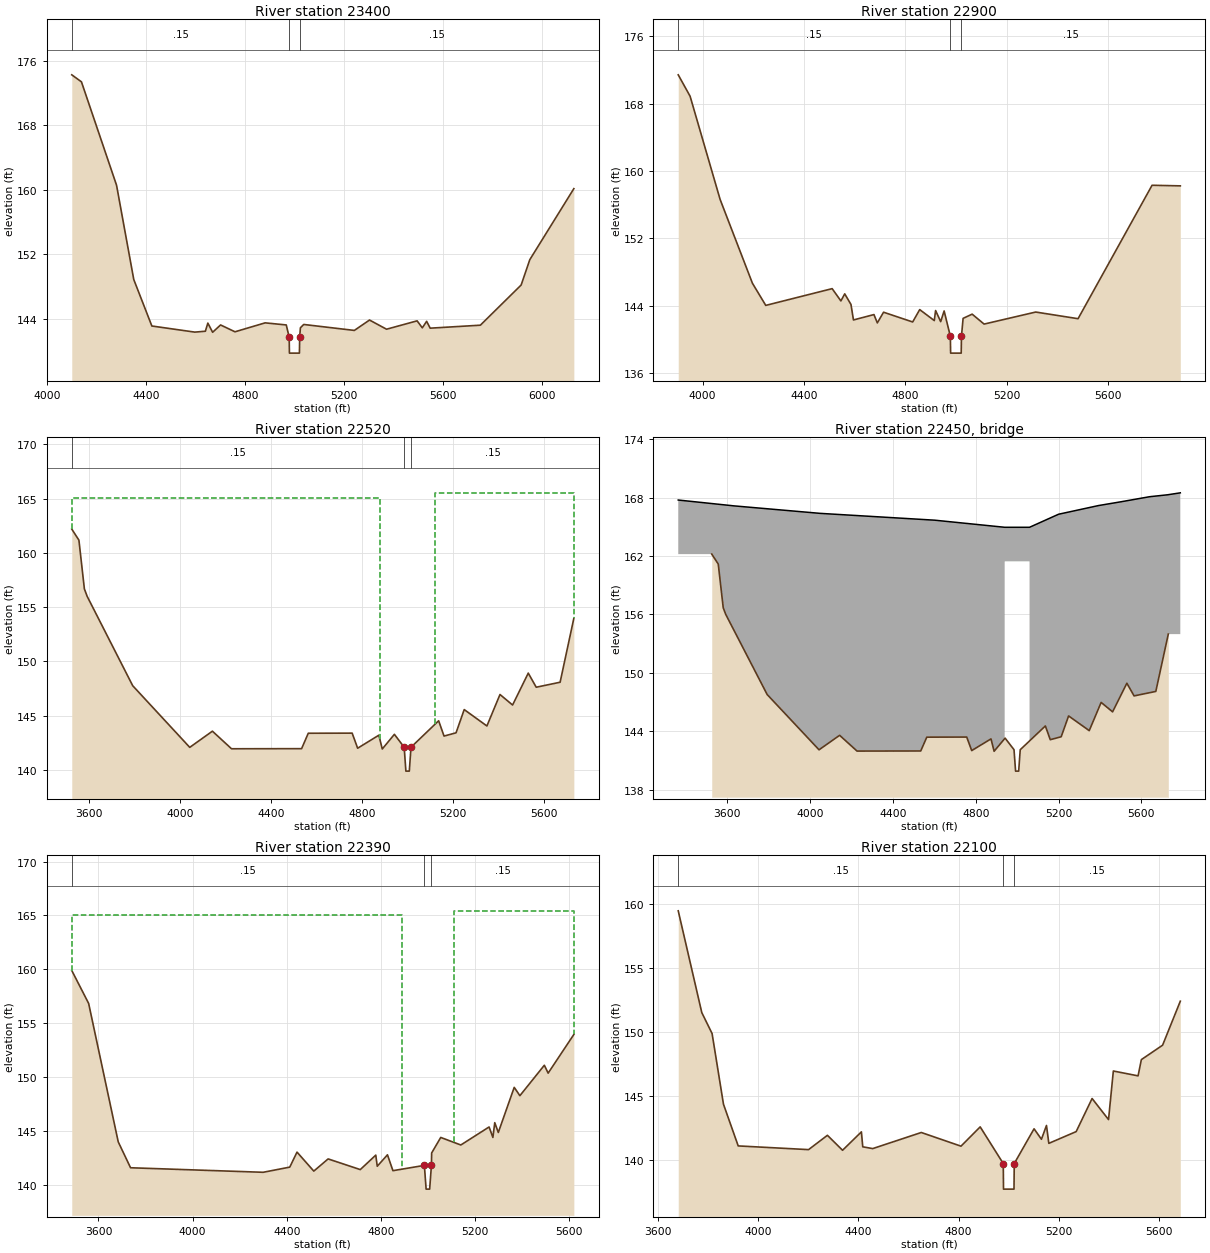
Type RM Length L Ch R = 1 ,23400   ,500,500,500
BEGIN DESCRIPTION:
CEDAR CREEK 61.0
END DESCRIPTION:
XS GIS Cut Line= 3
      2054700.15       743650.83      2053922.34       744101.83
      2052985.64       744730.83
#Sta/Elev= 30
  4100.9  174.27    4140   173.4  4281.7  160.56  4351.3  148.84  4424.3  143.07
  4597.7  142.31  4640.4  142.42  4650.4  143.43  4669.7  142.29  4701.8   143.2
  4759.9  142.35  4881.8  143.46    4967   143.2  4978.8   141.7  4979.8   139.7
  5020.2   139.7  5021.2   141.7  5024.2  142.85  5037.6  143.26    5242  142.52
  5303.2  143.81    5372  142.67  5495.4  143.71  5516.4  142.84  5533.9  143.65
  5548.2   142.8  5750.8  143.17  5915.5  148.16  5950.5  151.31  6128.3  160.13
#Mann= 3 ,-1 , 0
  4100.9     .15       0  4978.8    .045       0  5021.2     .15       0
Bank Sta=4978.8,5021.2
XS Rating Curve= 0 ,0
Exp/Cntr=0.3,0.1

Type RM Length L Ch R = 1 ,22900   ,380,380,380
BEGIN DESCRIPTION:
CEDAR CREEK 60.0
END DESCRIPTION:
XS GIS Cut Line= 3
      2054554.81       743357.35      2053554.02        743804.4
       2052814.1       744291.38
#Sta/Elev= 30
  3903.9  171.42  3950.7  168.88  4069.2  156.62  4196.8  146.66  4249.4  144.03
  4511.5  146.02    4546  144.56  4561.1   145.4  4585.8  144.14  4595.6   142.3
  4676.5  142.94  4689.8  141.95  4714.4  143.22  4829.3  142.06  4857.1  143.53
  4914.6  142.23  4919.8  143.42  4939.9   142.1  4953.5  143.37  4978.1  140.36
  4979.1  138.36  5020.9  138.36  5021.9  140.36  5028.4  142.49  5064.1  142.99
  5111.3  141.81  5315.1  143.24  5482.2  142.45  5774.3   158.3  5885.8  158.23
#Mann= 3 ,-1 , 0
  3903.9     .15       0  4978.1    .045       0  5021.9     .15       0
Bank Sta=4978.1,5021.9
XS Rating Curve= 0 ,0
Exp/Cntr=0.5,0.3

Type RM Length L Ch R = 1 ,22520   ,130,130,130
BEGIN DESCRIPTION:
CDC_Railroad (1)-US
END DESCRIPTION:
XS GIS Cut Line= 3
      2054422.78       742960.04      2053194.24       743776.68
       2052579.8       744171.39
#Sta/Elev= 30
  3524.8  162.19  3556.2  161.17  3580.2  156.68  3592.5  155.99  3792.5  147.76
  4043.1  142.08  4142.6  143.57  4226.6  141.95  4534.4  141.96  4563.7  143.38
  4756.5  143.39  4780.6     142  4873.7   143.2  4888.8  141.93    4942  143.28
    4985  142.09  4992.5  139.89  5007.5  139.89    5015  142.09  5136.4  144.53
  5160.1  143.12  5212.9  143.42  5248.7  145.56  5348.4  144.05  5405.9  146.95
  5461.2  145.98  5530.1  148.92    5565  147.62    5670  148.08  5730.3  153.97
#Mann= 3 ,-1 , 0
  3524.8     .15       0    4985    .045       0    5015     .15       0
#XS Ineff= 2 , 0
       0    4880  165.08    5120       0  165.53
Permanent Ineff=
       F       F
Bank Sta=4985,5015
XS Rating Curve= 0 ,0
Exp/Cntr=0.5,0.3

Type RM Length L Ch R = 3 ,22450   ,,,
BEGIN DESCRIPTION:
CDC_Railroad (1)-TOR
Structure ID: ID 277 - ESTIMATED
Approximate Survey Structure
END DESCRIPTION:
Bridge Culvert--1,0,-1,-1, 0
Deck Dist Width WeirC Skew NumUp NumDn MinLoCord MaxHiCord MaxSubmerge Is_Ogee
60,20,3,0, 14, 14, , , 0.95, 0, 1,1,,
  3362.9  3632.1  4048.5  4601.3    4940    4940    5060    5060  5200.1  5392.5
  5504.2  5639.6  5727.1  5788.3
  167.75  167.15  166.38  165.68  164.95  164.95  164.95  164.95  166.29  167.18
  167.58  168.09  168.29  168.49
  119.89  119.89  119.89  119.89  119.89  161.45  161.45  119.89  119.89  119.89
  119.89  119.89  119.89  119.89
  3362.9  3632.1  4048.5  4601.3    4940    4940    5060    5060  5200.1  5392.5
  5504.2  5639.6  5727.1  5788.3
  167.75  167.15  166.38  165.68  164.95  164.95  164.95  164.95  166.29  167.18
  167.58  168.09  168.29  168.49
  119.89  119.89  119.89  119.89  119.89  161.45  161.45  119.89  119.89  119.89
  119.89  119.89  119.89  119.89
Abutment Skew #Up #Dn= , 2 , 2
    4940    4955
  161.45  142.85
    4940    4955
  161.45  141.73
Abutment Skew #Up #Dn= , 2 , 2
    5045    5060
  142.38  161.45
    5045    5060
  143.69  161.45
BR Coef= 1 , 1 , 0 ,1.25, 0 ,,,0.8,0,2,0,
WSPro=,,,, 1 ,,,, 0 ,,,, 0 ,,,,-1 ,-1 ,-1 , 0 , 0 , 0 , 0 , 0
BC Design=,, 0 ,, 0 ,,,,,,
BC HTab HWMax=162.35
BC Use User HTab Curves=0
BC User HTab FreeFlow(D)= 0

Type RM Length L Ch R = 1 ,22390   ,290,290,290
BEGIN DESCRIPTION:
CDC_Railroad (1)-DS
END DESCRIPTION:
XS GIS Cut Line= 3
      2054386.48       742852.73      2053118.24       743678.71
      2052581.52       743989.69
#Sta/Elev= 30
  3486.5   159.9  3558.2  156.85    3684  144.02  3736.4  141.62    4300   141.2
    4413  141.68  4443.8  143.07  4515.1  141.31    4576  142.44  4712.6  141.45
  4778.5  142.79  4784.8  141.76  4828.2  142.82  4851.4  141.35    4985  141.84
  4992.5  139.64  5007.5  139.64    5015  141.84    5016  142.99  5054.6  144.43
    5140  143.73  5260.1   145.4  5276.3  144.43  5284.2   145.8  5299.3  144.89
  5366.9  149.07    5391   148.3  5494.9  151.12  5511.1  150.39  5620.3  153.97
#Mann= 3 ,-1 , 0
  3486.5     .15       0    4985    .045       0    5015     .15       0
#XS Ineff= 2 , 0
       0    4890  165.05    5110       0  165.43
Permanent Ineff=
       F       F
Bank Sta=4985,5015
XS Rating Curve= 0 ,0
Exp/Cntr=0.5,0.3

Type RM Length L Ch R = 1 ,22100   ,500,500,500
BEGIN DESCRIPTION:
CEDAR CREEK 56.0
END DESCRIPTION:
XS GIS Cut Line= 3
      2054400.36       742808.91      2053242.75       743438.62
      2052606.79       743690.44
#Sta/Elev= 30
  3682.2  159.49  3776.1  151.53  3817.2  149.89  3862.6  144.36  3921.3   141.1
  4201.8  140.81    4277  141.93  4337.4  140.76  4412.5   142.2  4417.9  141.03
  4457.6  140.89  4651.2  142.15  4809.6  141.08  4886.1  142.59  4978.1  139.72
  4979.1  137.72  5020.9  137.72  5021.9  139.72  5100.9  142.44  5130.3  141.62
  5150.4   142.7  5159.8   141.3  5268.8  142.22  5332.3  144.81  5397.8  143.16
    5417  146.96  5515.6  146.58  5528.7  147.85  5613.4  148.98    5684  152.42
#Mann= 3 ,-1 , 0
  3682.2     .15       0  4978.1    .045       0  5021.9     .15       0
Bank Sta=4978.1,5021.9
XS Rating Curve= 0 ,0
Exp/Cntr=0.3,0.1

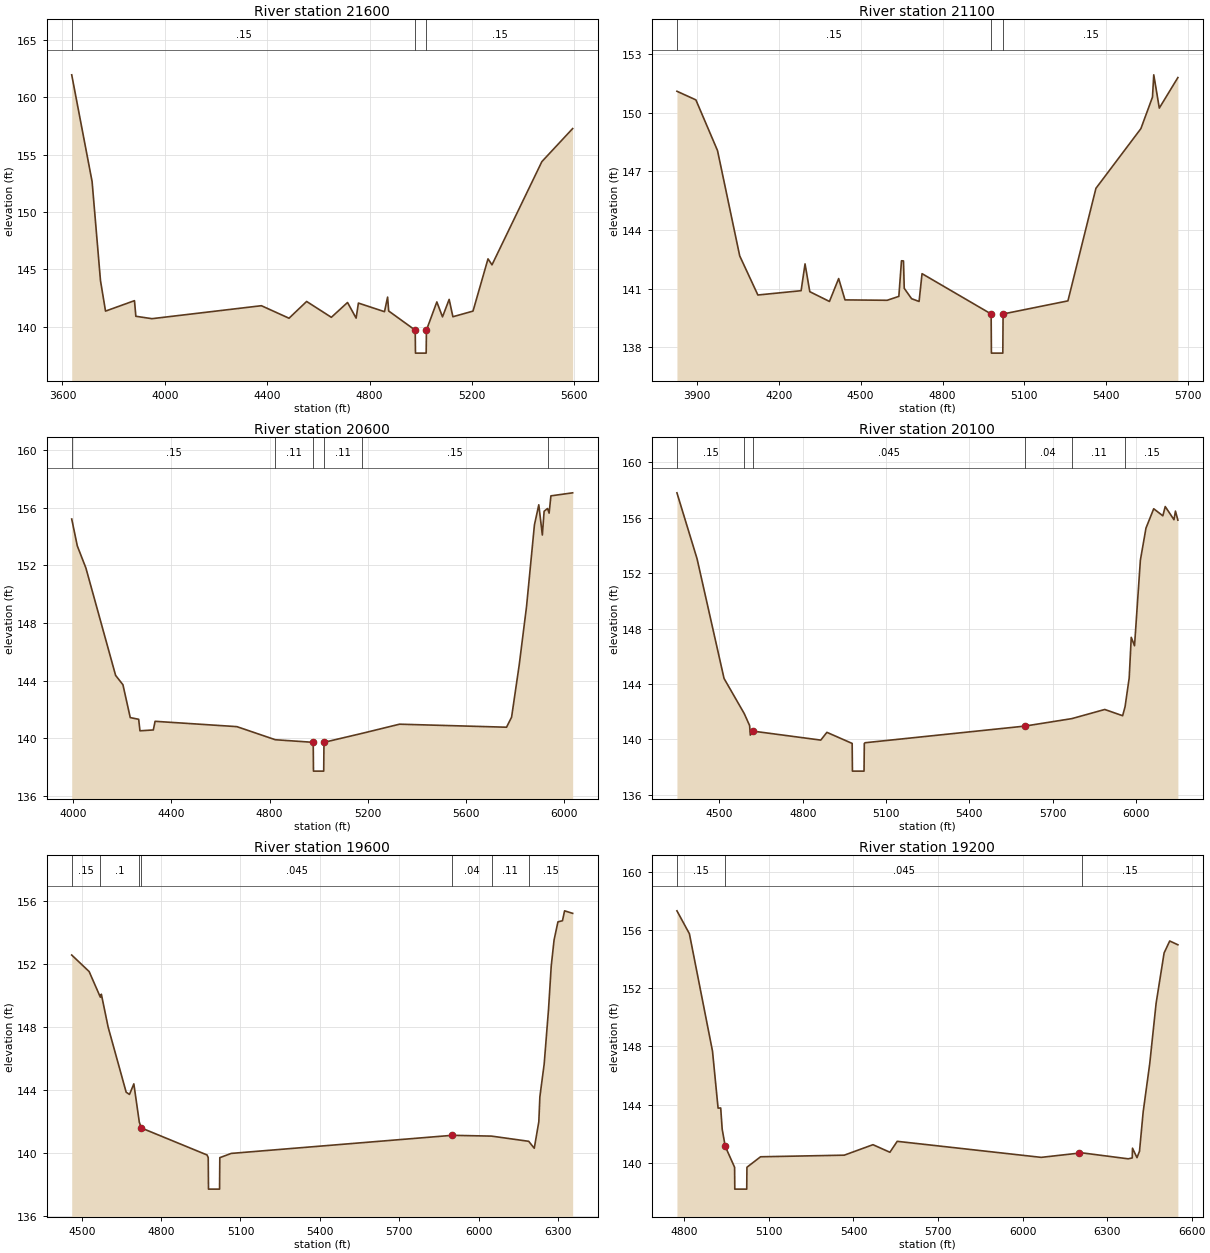
Type RM Length L Ch R = 1 ,21600   ,500,500,500
BEGIN DESCRIPTION:
CEDAR CREEK 55.0
END DESCRIPTION:
XS GIS Cut Line= 3
      2054418.89       742436.07      2053156.53       742952.47
      2052598.97       743154.98
#Sta/Elev= 30
  3636.1  161.95  3715.7  152.66  3748.5  144.03  3768.2  141.37  3881.3  142.28
  3886.7  140.92  3949.5  140.71  4377.2  141.84  4485.1  140.75  4553.9  142.21
  4650.4  140.83  4713.7  142.12  4747.2  140.76  4756.2  142.07  4858.1  141.32
  4870.2  142.59  4874.4  141.38  4978.1  139.71  4979.1  137.71  5020.9  137.71
  5021.9  139.71  5062.6  142.17  5084.7  140.87  5110.7  142.39  5125.3  140.88
  5203.9  141.37  5262.5  145.92  5278.1   145.4  5472.9  154.39  5593.2  157.27
#Mann= 3 ,-1 , 0
  3636.1     .15       0  4978.1    .045       0  5021.9     .15       0
Bank Sta=4978.1,5021.9
XS Rating Curve= 0 ,0
Exp/Cntr=0.3,0.1

Type RM Length L Ch R = 1 ,21100   ,500,500,500
BEGIN DESCRIPTION:
CEDAR CREEK 54.0
END DESCRIPTION:
XS GIS Cut Line= 3
      2054138.75       742158.66       2053010.2       742479.25
      2052400.81       742738.92
#Sta/Elev= 30
  3826.8  151.09  3896.2  150.65  3975.5  148.06  4056.8  142.68  4123.4  140.68
  4281.8   140.9  4296.2  142.27  4313.6  140.85  4385.6  140.35  4419.4  141.52
  4442.6  140.43  4597.2  140.41  4639.9  140.61  4649.6  142.43  4656.9  142.42
  4659.7  141.02  4686.7  140.49  4714.1  140.35  4724.9  141.77  4978.1  139.71
  4979.1  137.71  5020.9  137.71  5021.9  139.71  5259.5  140.38  5362.1  146.13
  5526.8  149.18  5569.3  150.79    5574  151.93  5594.3  150.23  5662.4  151.79
#Mann= 3 ,-1 , 0
  3826.8     .15       0  4978.1    .045       0  5021.9     .15       0
Bank Sta=4978.1,5021.9
XS Rating Curve= 0 ,0
Exp/Cntr=0.3,0.1

Type RM Length L Ch R = 1 ,20600   ,500,500,500
BEGIN DESCRIPTION:
CEDAR CREEK 53.0
END DESCRIPTION:
XS GIS Cut Line= 3
      2054090.64       741942.14      2053085.08       741990.13
      2052050.61       742046.37
#Sta/Elev= 30
  3993.3  155.22  4016.2  153.35  4051.3  151.81  4172.3  144.36  4202.2  143.71
    4232  141.43  4266.4  141.31  4271.6  140.51  4326.1  140.57  4333.2  141.17
  4666.8   140.8  4823.7  139.89  4978.1  139.71  4979.1  137.71  5020.9  137.71
  5021.9  139.71    5179  140.34    5330  140.97  5766.4  140.76    5787  141.46
  5818.1  145.09    5848  149.15  5880.1  154.81  5897.9  156.21  5912.4  154.11
  5919.6  155.76  5933.6  155.95    5940  155.63  5947.3  156.83    6036  157.04
#Mann= 6 ,-1 , 0
  3993.3     .15       0  4823.7     .11       0  4978.1    .045       0
  5021.9     .11       0    5179     .15       0  5933.6     .11       0
Bank Sta=4978.1,5021.9
XS Rating Curve= 0 ,0
Exp/Cntr=0.3,0.1

Type RM Length L Ch R = 1 ,20100   ,500,500,500
BEGIN DESCRIPTION:
CEDAR CREEK 52.0
END DESCRIPTION:
XS GIS Cut Line= 3
      2054005.71       741738.36      2053371.94       741580.62
      2052223.94       741490.91
#Sta/Elev= 30
  4346.9   157.8  4419.4  153.04  4516.6   144.4  4589.2  141.87  4608.7     141
  4611.2  140.31    4620   140.6    4865  139.95  4887.1  140.51  4978.1  139.71
  4979.1  137.71  5020.9  137.71  5021.9  139.71  5025.1  139.76    5600  140.96
  5769.4   141.5  5888.1  142.16  5952.5  141.71  5961.3  142.37  5976.1  144.44
  5983.5  147.37  5995.3  146.76  6016.4  152.94  6036.5  155.25  6064.4  156.65
  6097.4  156.14  6105.9  156.81  6137.4  155.86  6142.7  156.48  6151.5  155.83
#Mann= 6 ,-1 , 0
  4346.9     .15       0  4589.2     .04       0    4620    .045       0
    5600     .04       0  5769.4     .11       0  5961.3     .15       0
Bank Sta=4620,5600
XS Rating Curve= 0 ,0
Exp/Cntr=0.3,0.1

Type RM Length L Ch R = 1 ,19600   ,400,400,400
BEGIN DESCRIPTION:
CEDAR CREEK 51.0
END DESCRIPTION:
XS GIS Cut Line= 3
      2054164.19       741150.19      2053626.39       741151.71
      2052284.06       741338.77
#Sta/Elev= 30
  4462.2  152.59  4528.1  151.54  4570.5  149.91  4574.2   150.1    4600     148
    4668  143.87  4680.6  143.73    4697   144.4  4717.6  141.97    4725   141.6
  4973.8  139.88  4978.1  139.71  4979.1  137.71  5020.9  137.71  5021.9  139.71
    5065  139.98    5900  141.13  6048.6  141.08  6189.2  140.75  6210.2  140.31
  6227.4  141.99  6231.4  143.58  6247.7  145.67  6264.1  149.14  6274.3  151.89
  6285.1  153.55  6299.7   154.7  6316.8  154.77  6324.8   155.4  6355.3  155.24
#Mann= 7 ,-1 , 0
  4462.2     .15       0  4570.5      .1       0  4717.6     .04       0
    4725    .045       0    5900     .04       0  6048.6     .11       0
  6189.2     .15       0
Bank Sta=4725,5900
XS Rating Curve= 0 ,0
Exp/Cntr=0.3,0.1

Type RM Length L Ch R = 1 ,19200   ,600,600,600
BEGIN DESCRIPTION:
Cedar Creek (Dam 19000 - US)
END DESCRIPTION:
XS GIS Cut Line= 3
      2053963.19       740705.82      2053746.14       740770.57
      2052280.51       741278.63
#Sta/Elev= 30
  4773.5  157.31  4817.7  155.74  4899.7  147.68  4919.5  143.77  4928.8  143.78
  4934.1  142.32    4945  141.14  4978.1  139.71  4978.8  138.21  5021.2  138.21
  5021.9  139.71  5070.2  140.43  5367.2  140.54  5469.2  141.26  5529.2  140.74
  5555.2  141.49  6066.1  140.39    6200  140.68  6210.7   140.7  6374.9  140.29
  6389.2  140.35  6390.1  141.02  6406.1  140.37    6415  140.81    6428  143.51
  6451.3  146.82  6473.9  150.96  6502.3  154.42  6522.2  155.24  6551.2  154.98
#Mann= 3 ,-1 , 0
  4773.5     .15       0    4945    .045       0  6210.7     .15       0
Bank Sta=4945,6200
XS Rating Curve= 0 ,0
Exp/Cntr=0.3,0.1

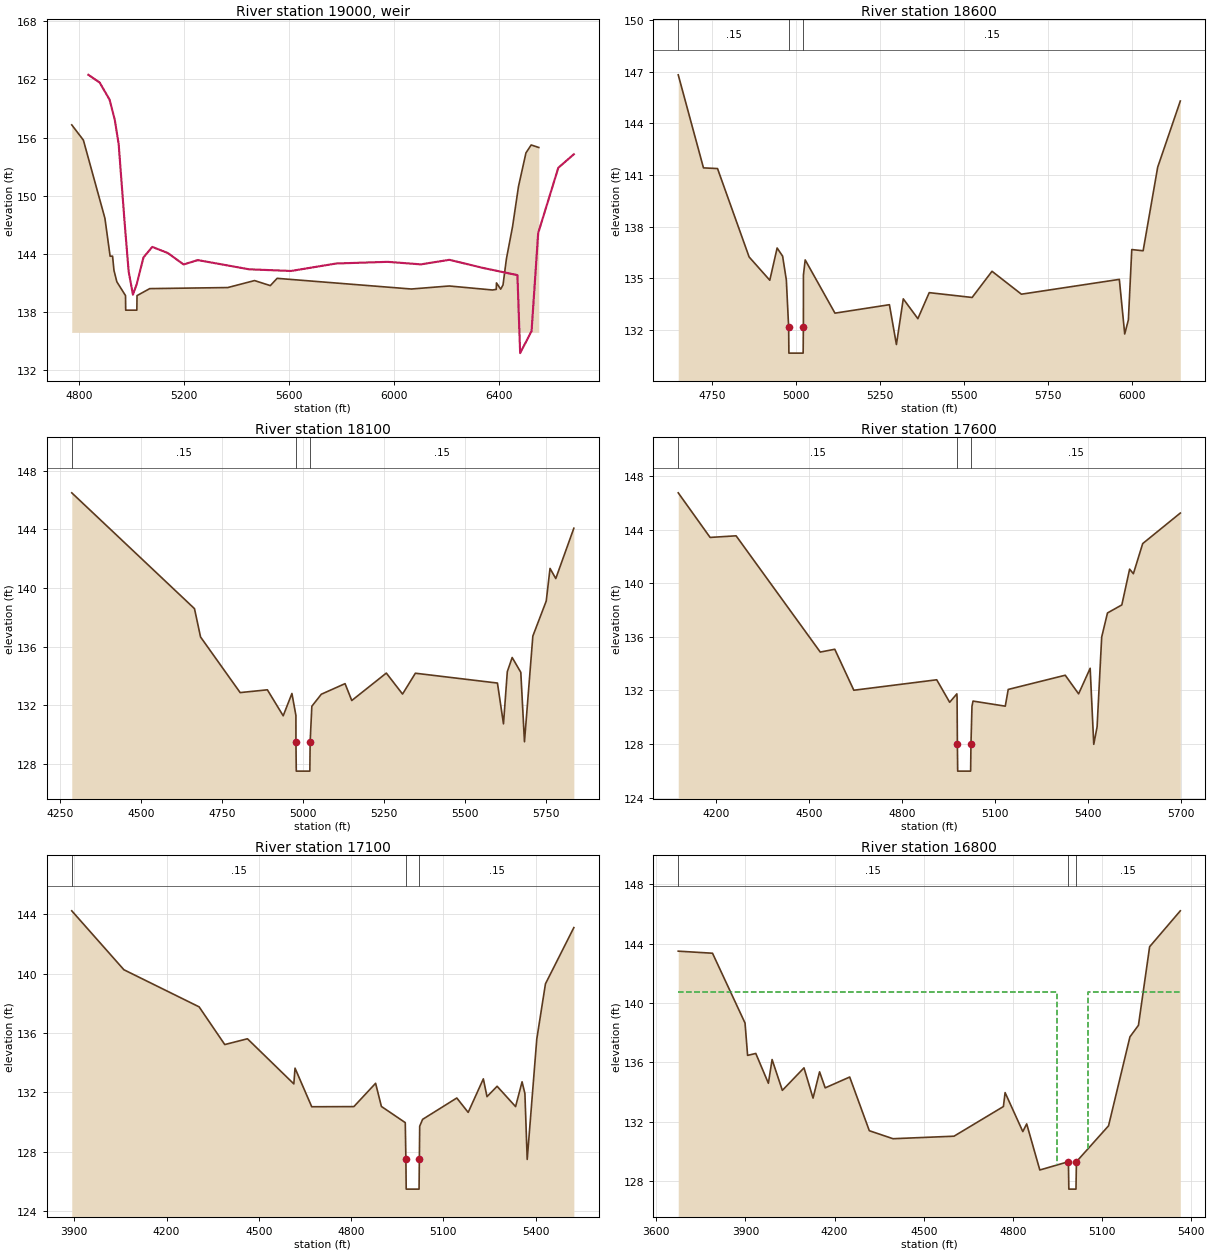
Type RM Length L Ch R = 5 ,19000   ,,,
BEGIN DESCRIPTION:
Cedar Creek (Dam 19000 - TOR)
Structure ID: Cedar Creek Dam 19000 - Estimated
Approximate Survey Structure
END DESCRIPTION:
IW Pilot Flow=0
#Inline Weir SE= 27
  4836.6  162.47  4879.5  161.68  4917.2  159.92  4937.1  157.85  4952.1   155.3
  4974.8  147.19    4990   142.2  5006.3   139.8  5020.7  140.89  5046.4  143.64
    5080  144.73  5139.1   144.1  5199.1  142.92  5253.3  143.37  5448.9  142.42
  5608.2  142.25  5780.3  143.02  5975.9  143.19  6102.3  142.93  6210.9   143.4
  6340.8  142.55  6469.8  141.82  6480.2  133.78  6523.7  136.06  6548.8  146.15
  6625.5  152.89  6684.6  154.28
IW Dist,WD,Coef,Skew,MaxSub,Min_El,Is_Ogee,SpillHt,DesHd
190,20,3,0,0.95,, 0 ,,,1,1,

Type RM Length L Ch R = 1 ,18600   ,500,500,500
BEGIN DESCRIPTION:
Cedar Creek (Dam 19000 - DS)
END DESCRIPTION:
XS GIS Cut Line= 3
      2053820.99       740398.64      2053493.35       740522.88
        2052398.       740850.51
#Sta/Elev= 30
  4649.6  146.81  4724.7  141.41  4766.5  141.37  4860.5  136.24    4922  134.89
  4943.8  136.76  4960.1  136.29  4971.2  134.91  4978.1  132.16  4978.8  130.66
  5021.2  130.66  5021.9  132.16  5022.1   135.2  5027.3  136.07  5115.9  132.98
  5277.9  133.47  5298.7  131.16  5319.1  133.81  5362.5  132.66  5396.3  134.17
  5523.9  133.89  5583.1  135.41  5670.6  134.08  5961.9  134.94  5977.9  131.77
  5988.8  132.59  5998.9  136.67  6032.7   136.6    6076  141.45  6143.3  145.29
#Mann= 3 ,-1 , 0
  4649.6     .15       0  4978.1    .045       0  5021.9     .15       0
Bank Sta=4978.1,5021.9
XS Rating Curve= 0 ,0
Exp/Cntr=0.3,0.1

Type RM Length L Ch R = 1 ,18100   ,500,500,500
BEGIN DESCRIPTION:
CEDAR CREEK 47.0
END DESCRIPTION:
XS GIS Cut Line= 3
      2053730.67       740019.02      2053087.21       740326.16
      2052282.93       740549.81
#Sta/Elev= 30
    4287  146.48  4665.3  138.59    4684  136.66  4806.1  132.87    4890  133.06
  4938.8  131.29  4965.7  132.81    4978  131.31  4978.1  129.52  4979.1  127.52
  5020.9  127.52  5021.9  129.52  5027.1  131.94  5056.4  132.76  5129.5  133.48
  5150.2  132.33  5256.7   134.2  5306.7  132.77  5346.3  134.19  5599.3  133.52
  5617.9  130.74  5629.7   134.3  5644.7  135.26  5671.3  134.25  5682.6  129.52
  5708.4  136.72  5749.7  139.11  5761.4  141.33  5779.1  140.64  5834.8  144.07
#Mann= 3 ,-1 , 0
    4287     .15       0  4978.1    .045       0  5021.9     .15       0
Bank Sta=4978.1,5021.9
XS Rating Curve= 0 ,0
Exp/Cntr=0.3,0.1

Type RM Length L Ch R = 1 ,17600   ,500,500,500
BEGIN DESCRIPTION:
CEDAR CREEK 46.0
END DESCRIPTION:
XS GIS Cut Line= 3
      2053679.37        739791.4      2052782.35       740008.86
      2052135.78       740271.02
#Sta/Elev= 30
    4077  146.75  4179.9  143.42  4263.8  143.54  4535.5  134.86  4582.3  135.07
  4643.8  132.01  4911.4  132.79  4953.2  131.11  4976.4  131.74  4977.1  131.45
  4978.1  127.97  4979.1  125.97  5020.9  125.97  5021.9  127.97  5025.2  130.81
  5028.6   131.2  5132.7  130.82  5142.2  132.07  5326.3  133.13  5369.4  131.74
  5406.7  133.65  5418.3  127.97  5429.1  129.28  5443.9  135.98  5462.6  137.78
  5508.9  138.38  5534.1  141.05  5546.2  140.71  5576.3  142.96  5697.7  145.24
#Mann= 3 ,-1 , 0
    4077     .15       0  4978.1    .045       0  5021.9     .15       0
Bank Sta=4978.1,5021.9
XS Rating Curve= 0 ,0
Exp/Cntr=0.3,0.1

Type RM Length L Ch R = 1 ,17100   ,300,300,300
BEGIN DESCRIPTION:
CEDAR CREEK 45.0
END DESCRIPTION:
XS GIS Cut Line= 3
      2053654.26       739251.02       2052592.4       739567.78
      2052106.48       739764.15
#Sta/Elev= 30
  3891.9  144.23  4061.4  140.26  4305.9  137.76  4389.3  135.22    4463  135.61
  4613.8  132.57  4617.7  133.63    4672  131.03    4809  131.04  4879.6  132.61
  4898.5  131.05  4976.1  129.96  4978.1  127.48  4979.1  125.48  5020.9  125.48
  5021.9  127.48    5023  129.72  5032.4  130.18  5143.6  131.62  5180.6  130.65
  5229.9  132.91  5241.8  131.71  5274.6  132.41  5334.7  131.04  5355.8  132.71
    5365  131.92  5372.5  127.48  5403.6  135.59  5431.8  139.31  5524.1   143.1
#Mann= 3 ,-1 , 0
  3891.9     .15       0  4978.1    .045       0  5021.9     .15       0
Bank Sta=4978.1,5021.9
XS Rating Curve= 0 ,0
Exp/Cntr=0.5,0.3

Type RM Length L Ch R = 1 ,16800   ,115,115,115
BEGIN DESCRIPTION:
CDC_Clarkson Rd-US
END DESCRIPTION:
XS GIS Cut Line= 3
       2053562.1        739108.6      2052303.54       739525.47
      2051993.38       739713.87
#Sta/Elev= 30
  3674.2   143.5  3789.5  143.36  3898.9  138.65  3907.5  136.47  3935.1   136.6
  3977.4  134.59  3989.9  136.19  4024.4  134.11  4097.2  135.63  4127.6  133.59
  4149.6  135.36  4168.5  134.28  4250.9  135.01  4316.9  131.39  4396.6  130.85
  4601.8  131.02  4767.9  133.02  4773.6  133.96  4833.2  131.33  4846.2  131.85
  4890.4  128.74  4986.5   129.3    4988  127.45    5012  127.45  5013.5   129.3
  5121.5  131.72  5193.5  137.72  5222.1   138.5  5259.7   143.8  5362.9  146.22
#Mann= 3 ,-1 , 0
  3674.2     .15       0  4986.5    .045       0  5013.5     .15       0
#XS Ineff= 2 , 0
       0    4947  140.75    5053       0  140.75
Permanent Ineff=
       F       F
Bank Sta=4986.5,5013.5
XS Rating Curve= 0 ,0
Exp/Cntr=0.5,0.3

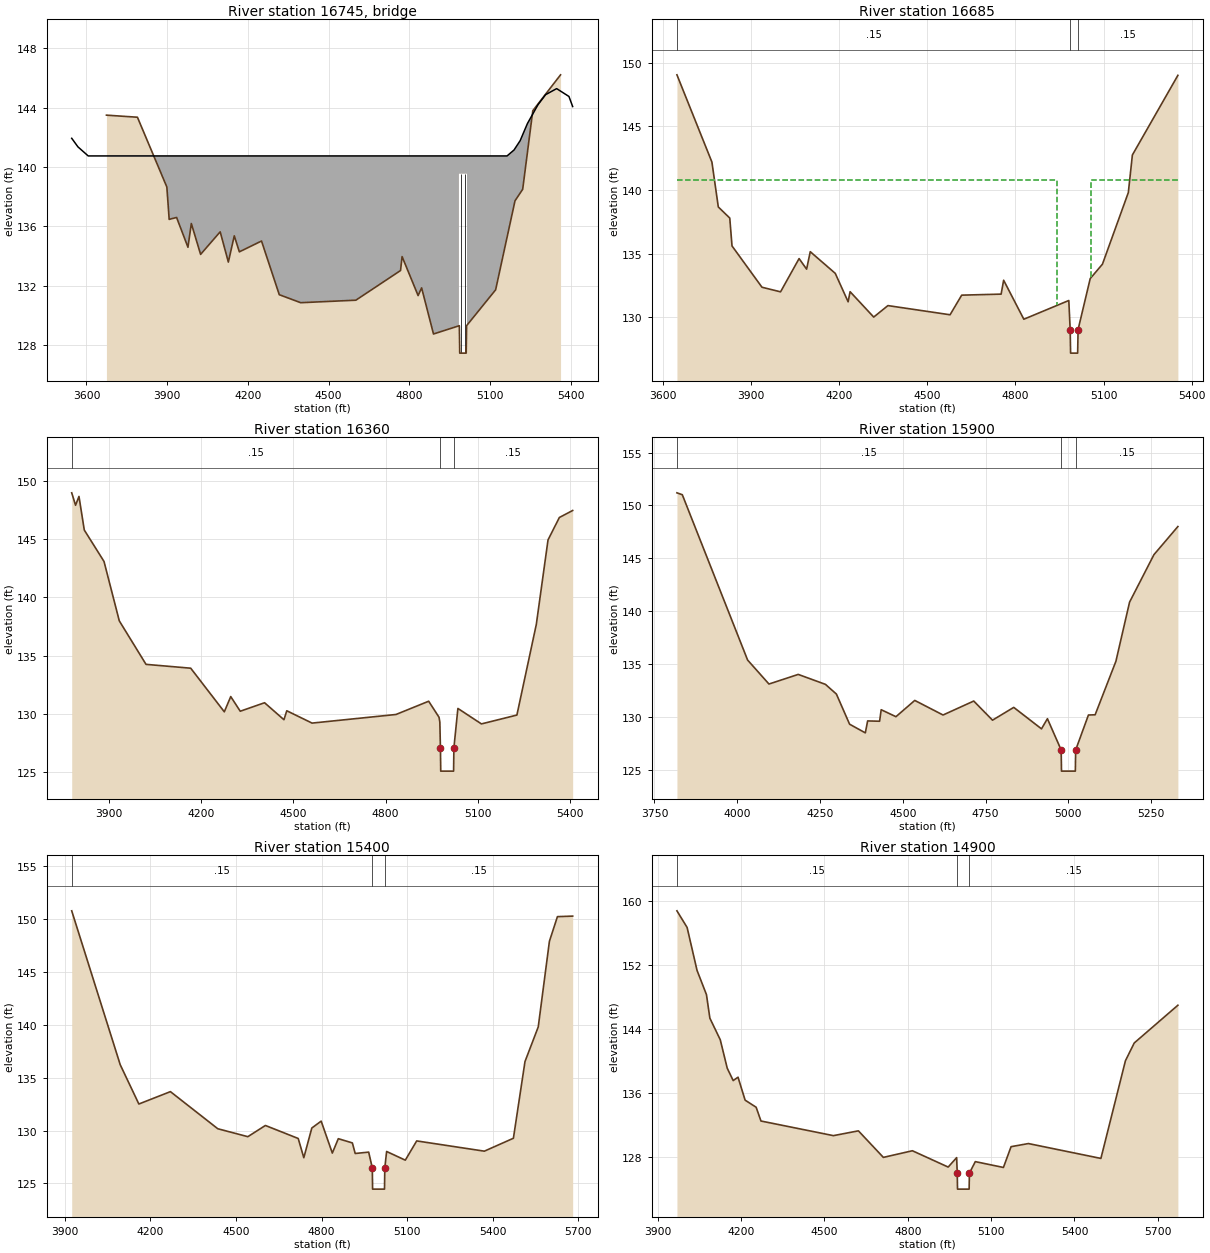
Type RM Length L Ch R = 3 ,16745   ,,,
BEGIN DESCRIPTION:
CDC_Clarkson Rd-TOR
Structure ID: lds 278
Approximate Survey Structure
END DESCRIPTION:
Bridge Culvert--1,0,-1,-1, 0
Deck Dist Width WeirC Skew NumUp NumDn MinLoCord MaxHiCord MaxSubmerge Is_Ogee
38,34,3,0, 16, 16, , , 0.95, 0, 1,1,,
  3545.1  3568.3  3606.4    4985    4985    5015    5015  5163.9  5189.8  5212.6
  5239.8  5278.8  5307.1  5348.3  5394.1  5407.9
  141.94  141.36  140.75  140.75  140.75  140.75  140.75  140.75  141.15  141.78
  142.94   144.2  144.88  145.29  144.76  144.08
  107.45  107.45  107.45  107.45  139.55  139.55  107.45  107.45  107.45  107.45
  107.45  107.45  107.45  107.45  107.45  107.45
  3545.1  3568.3  3606.4    4985    4985    5015    5015  5163.9  5189.8  5212.6
  5239.8  5278.8  5307.1  5348.3  5394.1  5407.9
  141.94  141.36  140.75  140.75  140.75  140.75  140.75  140.75  141.15  141.78
  142.94   144.2  144.88  145.29  144.76  144.08
  107.45  107.45  107.45  107.45  139.55  139.55  107.45  107.45  107.45  107.45
  107.45  107.45  107.45  107.45  107.45  107.45
Pier Skew, UpSta & Num, DnSta & Num=  ,4992.5, 2 ,4992.5, 2 , 0 , 0 , 0 ,0,0
     1.5     1.5
  127.45  139.55
     1.5     1.5
   127.2  139.55
Pier Skew, UpSta & Num, DnSta & Num=  ,5007.5, 2 ,5007.5, 2 , 0 , 0 , 0 ,0,0
     1.5     1.5
  127.45  139.55
     1.5     1.5
   127.2  139.55
Abutment Skew #Up #Dn= , 2 , 2
    4985    4988
  139.55  127.45
    4985    4988
  139.55   127.2
Abutment Skew #Up #Dn= , 2 , 2
    5012    5015
  127.45  139.55
    5012    5015
   127.2  139.55
BR Coef= 1 , 1 , 0 ,1.25, 0 ,,,0.8,0,2,0,
WSPro=,,,, 1 ,,,, 0 ,,,, 0 ,,,,-1 ,-1 ,-1 , 0 , 0 , 0 , 0 , 0
BC Design=,, 0 ,, 0 ,,,,,,
BC HTab HWMax=146.22
BC Use User HTab Curves=0
BC User HTab FreeFlow(D)= 0

Type RM Length L Ch R = 1 ,16685   ,325,325,325
BEGIN DESCRIPTION:
CDC_Clarkson Rd-DS
END DESCRIPTION:
XS GIS Cut Line= 3
      2053499.26       738970.93      2052231.94       739441.89
      2051899.89       739562.27
#Sta/Elev= 30
    3648  149.04  3767.1  142.19  3788.8  138.67  3827.8   137.8  3835.5  135.61
  3937.5  132.37  4000.7  132.01  4063.8  134.62  4089.4  133.79  4101.8  135.16
  4186.9  133.46  4230.7  131.23  4237.4  132.02  4317.8  130.03  4366.2  130.93
  4577.7  130.21  4617.3  131.75  4751.5  131.83  4760.1  132.92  4828.8  129.86
  4981.9  131.33  4986.5  129.05    4988   127.2    5012   127.2  5013.5  129.05
  5054.8  133.05  5096.4  134.18  5184.5   139.8  5198.3  142.75  5353.2     149
#Mann= 3 ,-1 , 0
    3648     .15       0  4986.5    .045       0  5013.5     .15       0
#XS Ineff= 2 , 0
       0    4942  140.75    5058       0  140.75
Permanent Ineff=
       F       F
Bank Sta=4986.5,5013.5
XS Rating Curve= 0 ,0
Exp/Cntr=0.5,0.3

Type RM Length L Ch R = 1 ,16360   ,460,460,460
BEGIN DESCRIPTION:
CEDAR CREEK 41.0
END DESCRIPTION:
XS GIS Cut Line= 3
      2053291.94       738603.81      2052208.83        739166.6
      2051829.98       739318.04
#Sta/Elev= 30
  3779.4     149  3791.9  147.93    3803  148.69  3820.3   145.8  3884.4   143.1
  3934.1  137.99    4021  134.25  4166.3  133.92  4275.5  130.17  4296.4  131.48
  4327.3  130.22  4406.4  130.95  4469.4  129.49  4478.6  130.26  4560.8   129.2
  4833.6  129.94  4939.9  131.08  4973.6   129.7  4976.2  129.28  4978.1  127.07
  4979.1  125.07  5020.9  125.07  5021.9  127.07  5034.9  130.46  5111.4  129.13
  5226.7  129.89  5289.8  137.68  5327.9  144.95  5364.8  146.88    5408  147.48
#Mann= 3 ,-1 , 0
  3779.4     .15       0  4978.1    .045       0  5021.9     .15       0
Bank Sta=4978.1,5021.9
XS Rating Curve= 0 ,0
Exp/Cntr=0.3,0.1

Type RM Length L Ch R = 1 ,15900   ,500,500,500
BEGIN DESCRIPTION:
CEDAR CREEK 40.0
END DESCRIPTION:
XS GIS Cut Line= 3
      2052858.39       738132.54      2051934.73       738870.41
      2051668.71       739066.69
#Sta/Elev= 30
  3817.8  151.19    3834  151.01  4031.2  135.37  4095.7   133.1  4184.1  134.01
  4266.2  133.07  4299.4  132.15  4339.2   129.3  4386.7  128.48  4393.7  129.61
  4429.8  129.58  4434.6  130.67  4479.2  130.01    4536  131.55  4621.4  130.17
  4714.1  131.49  4770.8  129.68  4834.9  130.89  4918.7  128.86  4936.6  129.82
  4978.1  126.86  4979.1  124.86  5020.9  124.86  5021.9  126.86  5060.5  130.17
  5080.7  130.19  5143.4  135.25  5184.7  140.85  5258.3  145.34  5330.6     148
#Mann= 3 ,-1 , 0
  3817.8     .15       0  4978.1    .045       0  5021.9     .15       0
Bank Sta=4978.1,5021.9
XS Rating Curve= 0 ,0
Exp/Cntr=0.3,0.1

Type RM Length L Ch R = 1 ,15400   ,500,500,500
BEGIN DESCRIPTION:
CEDAR CREEK 39.0
END DESCRIPTION:
XS GIS Cut Line= 3
      2052832.69       738126.81      2051813.31       738471.25
      2051183.29       738728.97
#Sta/Elev= 30
    3924  150.78  4094.2  136.22  4159.5  132.51  4270.1  133.68  4436.3  130.17
  4541.7  129.42  4603.2  130.48  4718.3  129.25  4737.9  127.43    4766  130.24
  4798.8  130.89  4837.9  127.87  4858.9  129.23  4908.2  128.83  4918.1  127.83
  4965.4  127.96  4978.1  126.46  4979.1  124.46  5020.9  124.46  5021.9  126.46
  5028.3  128.02  5093.8   127.2  5133.8  129.02    5371  128.05  5472.9  129.27
  5513.5  136.52    5560   139.8  5599.2   147.9  5627.3  150.23  5680.7  150.28
#Mann= 3 ,-1 , 0
    3924     .15       0  4978.1    .045       0  5021.9     .15       0
Bank Sta=4978.1,5021.9
XS Rating Curve= 0 ,0
Exp/Cntr=0.3,0.1

Type RM Length L Ch R = 1 ,14900   ,500,500,500
BEGIN DESCRIPTION:
CEDAR CREEK 38.0
END DESCRIPTION:
XS GIS Cut Line= 3
      2052845.79       737700.06      2051884.95       738072.24
      2051144.05       738289.12
#Sta/Elev= 30
  3969.6  158.79  4006.2  156.71  4041.9  151.34  4075.9   148.3    4088  145.37
  4125.5  142.66  4150.5  139.11    4172  137.56  4189.4  137.98  4214.9  135.11
  4254.6  134.22  4271.9   132.5  4532.6  130.67  4622.5  131.27  4712.3  127.95
  4816.8  128.78  4945.5  126.74    4976  127.92  4978.1  125.98  4979.1  123.98
  5020.9  123.98  5021.9  125.98  5043.1  127.42  5144.3  126.69  5171.8  129.29
  5234.2  129.68    5495  127.82  5583.3  140.04  5614.9  142.26    5772  146.98
#Mann= 3 ,-1 , 0
  3969.6     .15       0  4978.1    .045       0  5021.9     .15       0
Bank Sta=4978.1,5021.9
XS Rating Curve= 0 ,0
Exp/Cntr=0.3,0.1