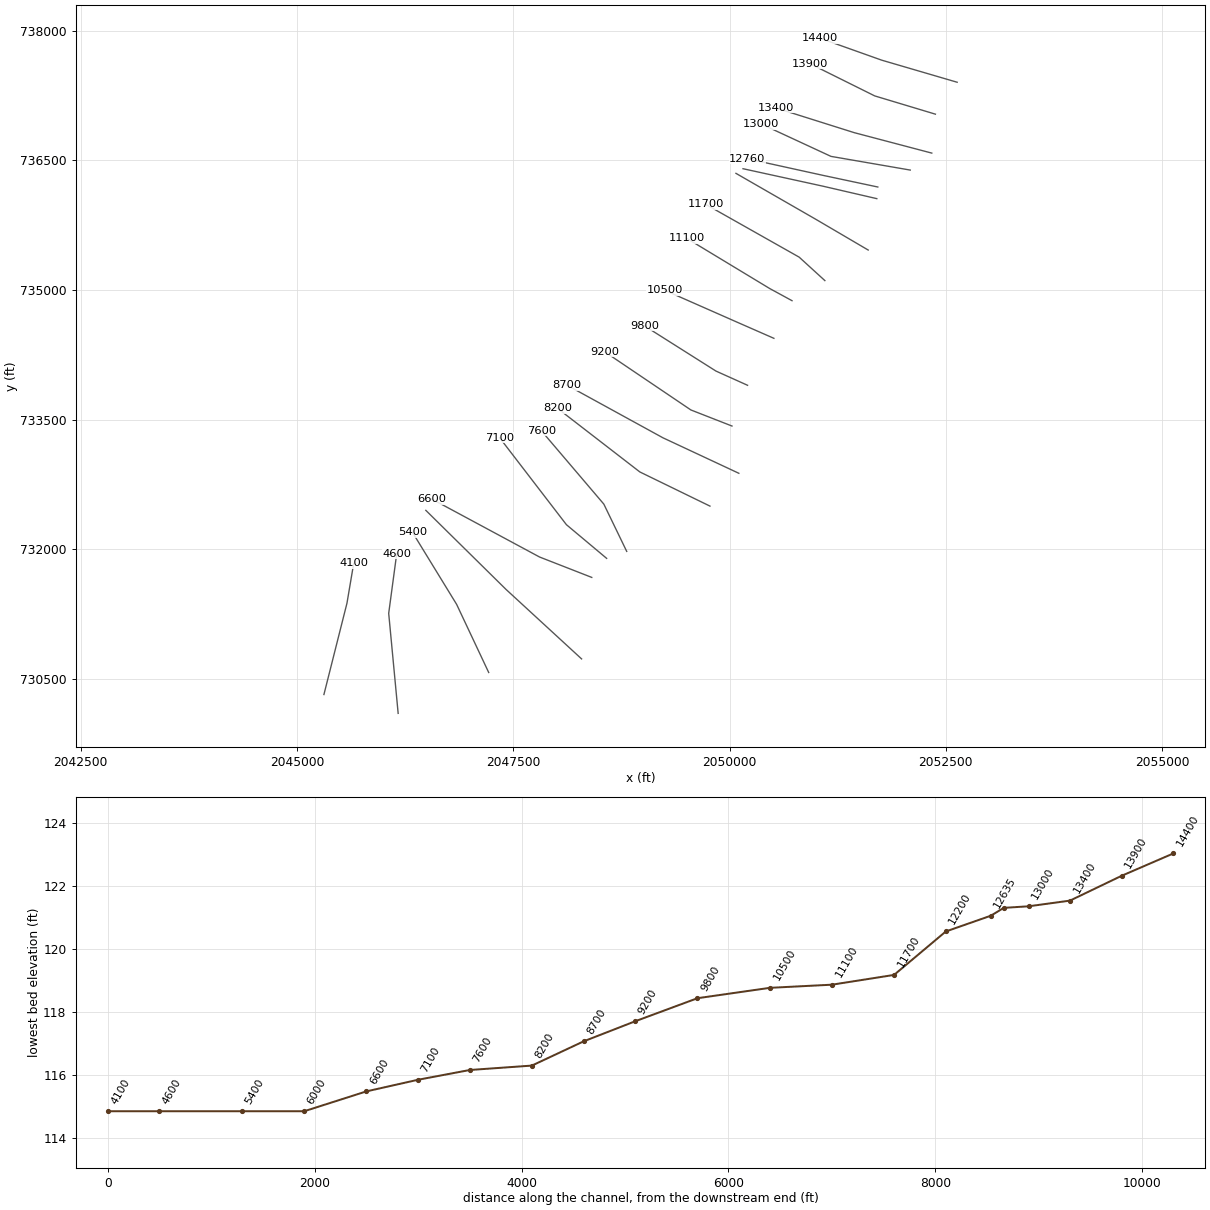
HEC-RAS study Cedar Creek.prj: Cedar Creek Limited Detail Study

--- Cedar Creek.g04 (geometry) --- (continued)

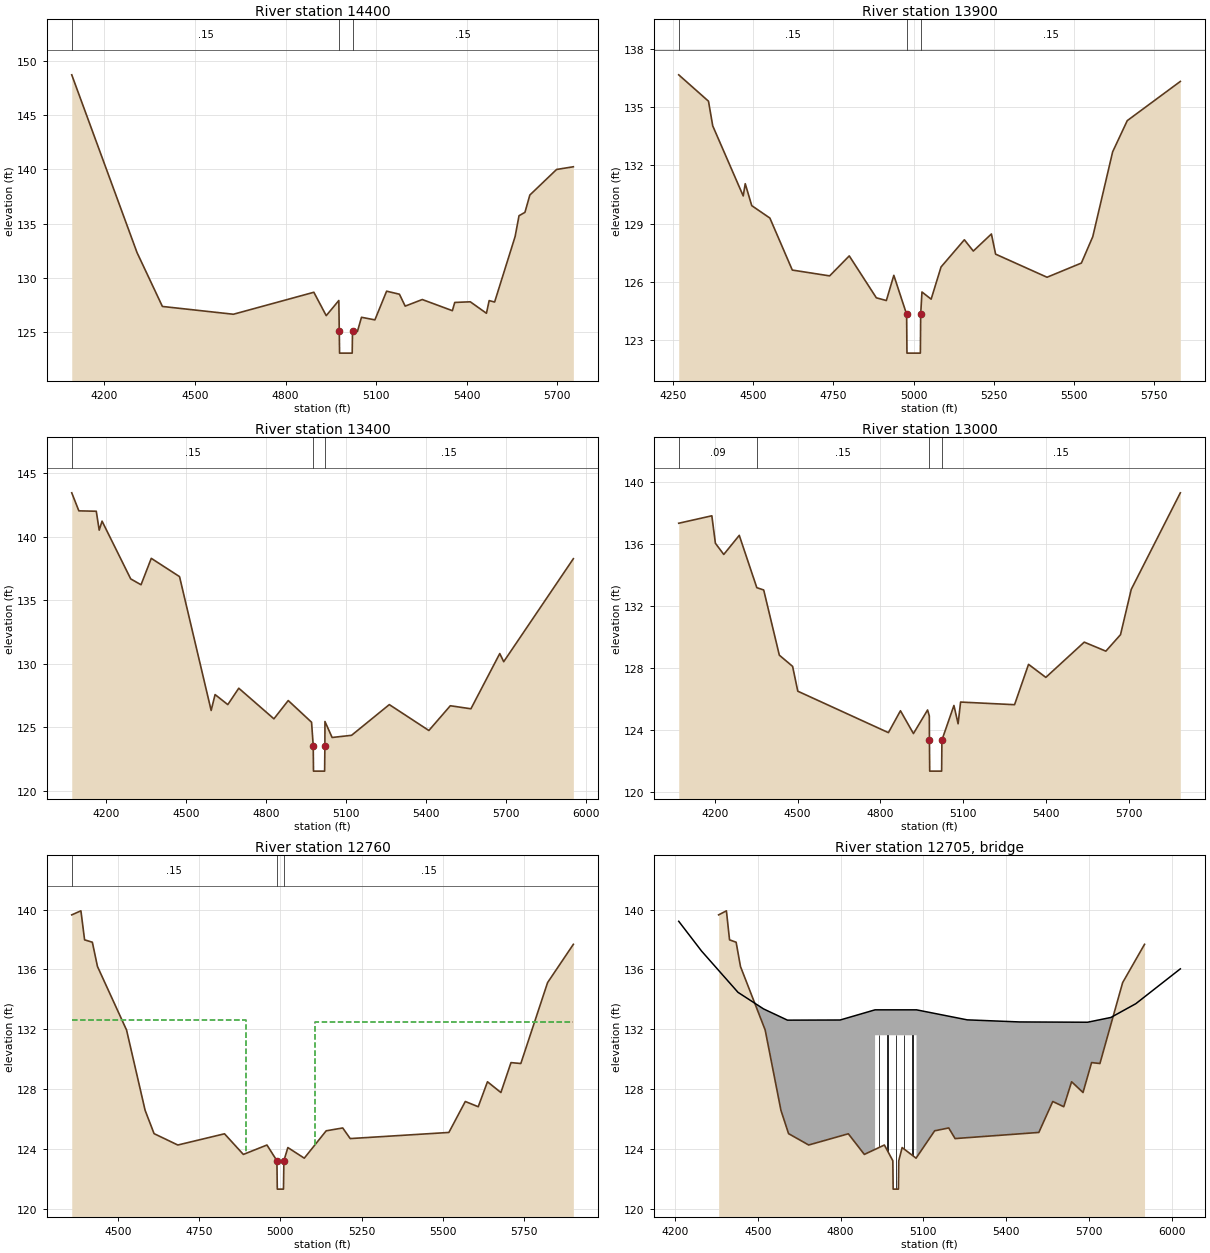
Type RM Length L Ch R = 1 ,14400   ,500,500,500
BEGIN DESCRIPTION:
CEDAR CREEK 37.0
END DESCRIPTION:
XS GIS Cut Line= 3
      2052631.15        737404.2      2051759.67       737659.47
      2051049.79       737912.12
#Sta/Elev= 30
  4091.9  148.74  4308.1  132.33  4392.2  127.35  4627.4  126.63  4893.9  128.66
  4934.9   126.5  4976.6   127.9  4978.1  125.04  4979.1  123.04  5020.9  123.04
  5021.9  125.04  5038.2  125.04  5051.7  126.35  5096.1  126.11  5134.9  128.76
  5177.4  128.48  5196.4  127.38  5253.1  127.99  5352.8  126.96  5360.6  127.72
  5412.1  127.78  5465.6  126.72  5474.6  127.89  5492.7  127.76  5560.6  133.81
  5573.5  135.73  5593.1  136.04  5609.4  137.64  5697.9     140  5753.5  140.25
#Mann= 3 ,-1 , 0
  4091.9     .15       0  4978.1    .045       0  5021.9     .15       0
Bank Sta=4978.1,5021.9
XS Rating Curve= 0 ,0
Exp/Cntr=0.3,0.1

Type RM Length L Ch R = 1 ,13900   ,500,500,500
BEGIN DESCRIPTION:
CEDAR CREEK 36.0
END DESCRIPTION:
XS GIS Cut Line= 3
      2052379.79       737035.05      2051678.66       737246.09
      2050934.56       737616.28
#Sta/Elev= 30
  4267.8  136.67  4360.6  135.31  4373.8  134.04  4468.8  130.43  4475.1  131.06
  4495.4  129.93  4551.9  129.29  4621.8  126.61  4738.2  126.31  4799.3  127.34
  4883.7  125.18  4914.9  125.04  4938.2  126.34  4978.1  124.33  4979.1  122.33
  5020.9  122.33  5021.9  124.33  5025.9  125.48  5054.5  125.11  5085.4  126.77
    5158  128.17  5185.9  127.59  5242.3  128.47  5255.4  127.43  5415.7  126.24
  5522.7  126.97  5558.2  128.33  5620.1   132.7  5665.7  134.31  5831.1  136.33
#Mann= 3 ,-1 , 0
  4267.8     .15       0  4978.1    .045       0  5021.9     .15       0
Bank Sta=4978.1,5021.9
XS Rating Curve= 0 ,0
Exp/Cntr=0.3,0.1

Type RM Length L Ch R = 1 ,13400   ,400,400,400
BEGIN DESCRIPTION:
CEDAR CREEK 35.0
END DESCRIPTION:
XS GIS Cut Line= 3
      2052337.91       736584.74        2051441.       736821.36
       2050531.4       737108.36
#Sta/Elev= 30
  4072.4  143.46  4099.1  142.04  4164.4  142.01  4175.4  140.52  4186.1  141.23
  4293.6  136.68  4332.3  136.22  4370.7   138.3  4476.7  136.86  4595.3  126.32
    4610  127.57  4657.7  126.78  4698.9  128.07  4830.7  125.66  4884.4   127.1
  4971.9  125.39  4978.1  123.54  4979.1  121.54  5020.9  121.54  5021.9  123.54
  5022.1  125.45    5049  124.19  5121.9  124.36  5263.5  126.78  5411.9  124.74
  5492.3  126.69  5569.6  126.45  5677.8   130.8  5692.6  130.16  5953.8  138.27
#Mann= 3 ,-1 , 0
  4072.4     .15       0  4978.1    .045       0  5021.9     .15       0
Bank Sta=4978.1,5021.9
XS Rating Curve= 0 ,0
Exp/Cntr=0.3,0.1

Type RM Length L Ch R = 1 ,13000   ,240,240,240
BEGIN DESCRIPTION:
CEDAR CREEK 34.0
END DESCRIPTION:
XS GIS Cut Line= 3
      2052089.17       736388.38      2051172.48        736546.9
      2050369.03       736919.88
#Sta/Elev= 30
  4069.7  137.33  4189.6  137.81  4202.5  136.04  4232.8  135.32  4288.9  136.55
  4352.4  133.18  4377.4  133.03    4434  128.83    4482  128.11  4500.8  126.51
  4828.9  123.84  4872.5  125.25  4919.5  123.78  4970.7   125.3    4977  124.91
  4977.4  123.36  4978.4  121.36  5021.6  121.36  5022.6  123.36  5066.1  125.59
  5081.2  124.41  5090.2  125.81  5285.6  125.64  5336.2  128.24  5398.8   127.4
  5537.9  129.67  5616.2  129.09  5669.2  130.15  5708.1  133.07  5885.8  139.29
#Mann= 4 ,-1 , 0
  4069.7     .09       0  4352.4     .15       0  4977.4    .045       0
  5022.6     .15       0
Bank Sta=4977.4,5022.6
XS Rating Curve= 0 ,0
Exp/Cntr=0.5,0.3

Type RM Length L Ch R = 1 ,12760   ,125,125,125
BEGIN DESCRIPTION:
CDC_Bluff Rd-US
END DESCRIPTION:
XS GIS Cut Line= 3
      2051713.98       736192.58      2051086.21       736326.05
      2050206.03       736519.56
#Sta/Elev= 30
  4358.2  139.65  4386.4  139.92  4397.7  137.98  4421.6  137.82  4437.3   136.2
  4526.8  131.95  4583.9  126.58  4611.5  125.02  4684.5  124.26  4828.1  125.01
  4886.1  123.63  4958.7  124.26  4989.3  123.21  4990.5  121.31  5009.5  121.31
  5010.8  123.21    5023  124.09  5073.5  123.38  5140.9  125.21  5191.8   125.4
  5214.8  124.69  5518.3   125.1  5568.8  127.17  5608.6  126.82    5637  128.49
  5678.3  127.77  5709.4  129.77  5739.6  129.71  5821.9  135.12  5901.2  137.68
#Mann= 3 ,-1 , 0
  4358.2     .15       0  4989.3    .045       0  5010.8     .15       0
#XS Ineff= 2 , 0
       0    4895   132.6    5105       0  132.47
Permanent Ineff=
       F       F
Bank Sta=4989.3,5010.8
XS Rating Curve= 0 ,0
Exp/Cntr=0.5,0.3

Type RM Length L Ch R = 3 ,12705   ,,,
BEGIN DESCRIPTION:
CDC_Bluff Rd-TOR
Structure ID: lds 280
Approximate Survey Structure
END DESCRIPTION:
Bridge Culvert--1,0,-1,-1, 0
Deck Dist Width WeirC Skew NumUp NumDn MinLoCord MaxHiCord MaxSubmerge Is_Ogee
30,50,3,0, 16, 16, , , 0.95, 0, 1,1,,
  4213.6  4296.3  4428.3  4521.1  4607.5  4798.3    4925    4925    5075    5075
  5258.7  5448.6  5694.7  5779.3  5869.6  6030.9
  139.22  137.23  134.47  133.36  132.61  132.62   133.3   133.3   133.3   133.3
  132.63  132.49  132.47  132.79  133.71  136.04
  101.31  101.31  101.31  101.31  101.31  101.31  101.31   131.6   131.6  101.31
  101.31  101.31  101.31  101.31  101.31  101.31
  4213.6  4296.3  4428.3  4521.1  4607.5  4798.3    4925    4925    5075    5075
  5258.7  5448.6  5694.7  5779.3  5869.6  6030.9
  139.22  137.23  134.47  133.36  132.61  132.62   133.3   133.3   133.3   133.3
  132.63  132.49  132.47  132.79  133.71  136.04
  101.31  101.31  101.31  101.31  101.31  101.31  101.31   131.6   131.6  101.31
  101.31  101.31  101.31  101.31  101.31  101.31
Pier Skew, UpSta & Num, DnSta & Num=  ,4940, 2 ,4940, 2 , 0 , 0 , 0 ,0,0
     1.5     1.5
  123.75   131.6
     1.5     1.5
  123.49   131.6
Pier Skew, UpSta & Num, DnSta & Num=  ,4970, 2 ,4970, 2 , 0 , 0 , 0 ,0,0
     1.5     1.5
  123.48   131.6
     1.5     1.5
   124.9   131.6
Pier Skew, UpSta & Num, DnSta & Num=  ,5000, 2 ,5000, 2 , 0 , 0 , 0 ,0,0
     1.5     1.5
   123.4   131.6
     1.5     1.5
  123.15   131.6
Pier Skew, UpSta & Num, DnSta & Num=  ,5030, 2 ,5030, 2 , 0 , 0 , 0 ,0,0
     1.5     1.5
  123.36   131.6
     1.5     1.5
  124.57   131.6
Pier Skew, UpSta & Num, DnSta & Num=  ,5060, 2 ,5060, 2 , 0 , 0 , 0 ,0,0
     1.5     1.5
  123.56   131.6
     1.5     1.5
  123.95   131.6
Abutment Skew #Up #Dn= , 2 , 2
    4925  4939.5
   131.6  123.84
    4925  4939.5
   131.6  123.48
Abutment Skew #Up #Dn= , 2 , 2
  5060.5    5075
   123.6   131.6
  5060.5    5075
     124   131.6
BR Coef= 1 , 1 , 0 ,1.25, 0 ,,,0.8,0,2,0,
WSPro=,,,, 1 ,,,, 0 ,,,, 0 ,,,,-1 ,-1 ,-1 , 0 , 0 , 0 , 0 , 0
BC Design=,, 0 ,, 0 ,,,,,,
BC HTab HWMax=139.97
BC Use User HTab Curves=0
BC User HTab FreeFlow(D)= 0

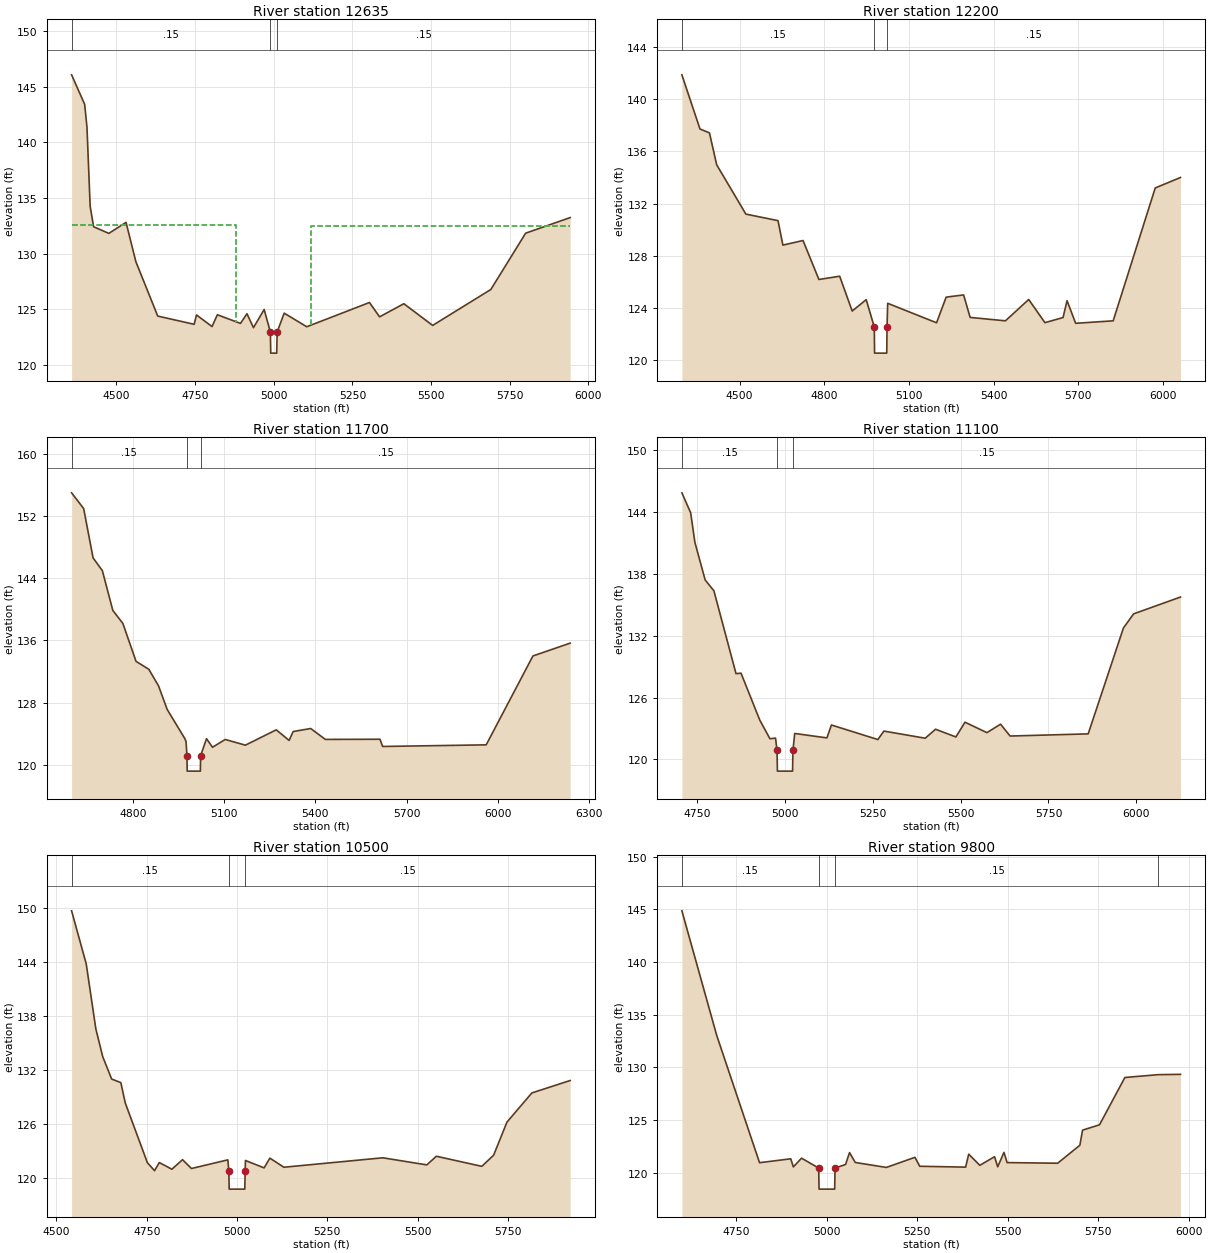
Type RM Length L Ch R = 1 ,12635   ,435,435,435
BEGIN DESCRIPTION:
CDC_Bluff Rd-DS
END DESCRIPTION:
XS GIS Cut Line= 3
      2051702.44       736057.94       2051076.5       736202.85
      2050156.05       736404.15
#Sta/Elev= 30
  4357.5  146.07    4399  143.42  4406.4  141.35  4416.5  134.26  4427.4  132.42
  4475.8  131.82  4530.5  132.81  4561.9  129.27  4631.3  124.39  4747.1  123.65
  4754.5  124.49  4803.9  123.45  4820.9  124.51  4894.2  123.73  4914.9   124.6
  4935.6  123.35  4969.5  124.98  4989.3  122.96  4990.5  121.06  5009.5  121.06
  5010.8  122.96  5033.3  124.65    5105  123.43  5304.3  125.61  5336.4  124.32
  5413.6   125.5  5505.1  123.55  5690.1  126.78  5800.7  131.84  5942.2  133.24
#Mann= 3 ,-1 , 0
  4357.5     .15       0  4989.3    .045       0  5010.8     .15       0
#XS Ineff= 2 , 0
       0    4880   132.6    5120       0  132.47
Permanent Ineff=
       F       F
Bank Sta=4989.3,5010.8
XS Rating Curve= 0 ,0
Exp/Cntr=0.5,0.3

Type RM Length L Ch R = 1 ,12200   ,500,500,500
BEGIN DESCRIPTION:
CEDAR CREEK 30.0
END DESCRIPTION:
XS GIS Cut Line= 3
      2051602.83       735463.56      2050995.44       735820.29
      2050074.53       736350.43
#Sta/Elev= 30
  4295.6  141.84  4359.6   137.7  4393.3   137.4  4418.9  134.96  4522.3  131.19
  4636.2  130.69  4653.5  128.82  4724.9  129.17  4781.2  126.19  4854.8  126.44
  4899.1  123.78  4948.8  124.65  4977.4  122.56  4978.4  120.56  5021.6  120.56
  5022.6  122.56  5024.9  124.37  5198.1  122.88  5232.1  124.84    5294  125.01
  5317.2  123.29  5442.2  123.03  5524.7  124.66  5582.3  122.89  5646.4  123.28
  5660.6  124.57  5691.1  122.84  5824.1  123.03  5973.1  133.19  6062.6  133.99
#Mann= 3 ,-1 , 0
  4295.6     .15       0  4977.4    .045       0  5022.6     .15       0
Bank Sta=4977.4,5022.6
XS Rating Curve= 0 ,0
Exp/Cntr=0.3,0.1

Type RM Length L Ch R = 1 ,11700   ,600,600,600
BEGIN DESCRIPTION:
CEDAR CREEK 29.0
END DESCRIPTION:
XS GIS Cut Line= 3
      2051102.12       735110.12      2050805.35       735381.14
      2049727.66       735990.42
#Sta/Elev= 30
  4598.1  154.97  4637.8  152.95  4668.7  146.61  4699.3  144.96  4733.7  139.85
  4766.8  138.17    4810   133.3  4852.1  132.28  4884.2  130.13  4912.4  127.12
  4970.9  123.34  4974.6  122.98  4977.4  121.18  4978.4  119.18  5021.6  119.18
  5022.6  121.18  5041.9  123.35  5061.6  122.25  5103.4  123.25  5169.8  122.52
  5271.2  124.49  5313.6  123.13  5326.9  124.27  5384.5  124.66  5432.8  123.26
  5612.3  123.28  5621.3  122.35  5961.8  122.56  6115.5  133.99    6238  135.64
#Mann= 3 ,-1 , 0
  4598.1     .15       0  4977.4    .045       0  5022.6     .15       0
Bank Sta=4977.4,5022.6
XS Rating Curve= 0 ,0
Exp/Cntr=0.3,0.1

Type RM Length L Ch R = 1 ,11100   ,600,600,600
BEGIN DESCRIPTION:
CEDAR CREEK 28.0
END DESCRIPTION:
XS GIS Cut Line= 3
      2050722.52       734877.74      2050464.89       735018.13
      2049501.84       735600.99
#Sta/Elev= 30
  4706.6  145.84  4731.5  143.91  4743.6  141.04  4772.8   137.4  4797.7  136.34
  4860.6  128.32  4874.9  128.36  4928.2  123.82  4957.1  122.01  4973.1  122.07
  4977.4  120.87  4978.4  118.87  5021.6  118.87  5022.6  120.87  5027.7  122.52
  5119.3  122.09  5132.2  123.34  5264.4  121.93  5281.5  122.75  5399.1  122.06
  5428.5  122.93  5486.5  122.18  5512.3  123.61  5574.8   122.6  5613.6  123.42
  5640.8  122.27    5863  122.48  5963.3  132.74  5992.3  134.11  6125.7  135.74
#Mann= 3 ,-1 , 0
  4706.6     .15       0  4977.4    .045       0  5022.6     .15       0
Bank Sta=4977.4,5022.6
XS Rating Curve= 0 ,0
Exp/Cntr=0.3,0.1

Type RM Length L Ch R = 1 ,10500   ,700,700,700
BEGIN DESCRIPTION:
CEDAR CREEK 27.0
END DESCRIPTION:
XS GIS Cut Line= 3
      2050513.07       734442.48      2050093.79       734626.54
      2049249.85       734998.82
#Sta/Elev= 30
  4542.1  149.67  4582.6  143.78  4609.2  136.57  4628.1   133.5    4653  130.99
  4678.4   130.6  4690.8  128.32    4752   121.7  4771.7  120.82  4784.9  121.72
  4819.8  120.98  4849.2  122.04  4873.9  121.06  4974.7  122.02  4977.4  120.77
  4978.4  118.77  5021.6  118.77  5022.6  120.77  5023.4  121.95  5075.1  121.13
    5091  122.21  5129.9   121.2  5403.8  122.25  5525.5  121.46  5551.9  122.42
  5677.8   121.3  5710.5  122.54  5747.4  126.21  5816.3  129.45  5922.4  130.83
#Mann= 3 ,-1 , 0
  4542.1     .15       0  4977.4    .045       0  5022.6     .15       0
Bank Sta=4977.4,5022.6
XS Rating Curve= 0 ,0
Exp/Cntr=0.3,0.1

Type RM Length L Ch R = 1 ,9800    ,600,600,600
BEGIN DESCRIPTION:
CEDAR CREEK 26.0
END DESCRIPTION:
XS GIS Cut Line= 3
      2050208.71       733899.23      2049843.34       734063.74
      2049017.48       734586.48
#Sta/Elev= 30
  4599.3  144.87  4695.6  133.03  4813.9  120.95  4900.2  121.32  4907.4  120.55
    4930  121.38  4977.4  120.44  4978.4  118.44  5021.6  118.44  5022.6  120.44
  5051.6  120.78  5062.7  121.91  5078.5  120.97  5164.5   120.5  5243.4  121.46
  5256.8  120.61  5383.5  120.53  5392.1  121.76  5422.8   120.7  5463.5  121.52
  5472.2  120.56  5489.5  121.93  5498.2  120.96    5638   120.9  5699.3  122.61
  5706.7  124.04  5753.6  124.55  5823.7  129.04  5915.2  129.31  5977.4  129.34
#Mann= 4 ,-1 , 0
  4599.3     .15       0  4977.4    .045       0  5022.6     .15       0
  5915.2     .11       0
Bank Sta=4977.4,5022.6
XS Rating Curve= 0 ,0
Exp/Cntr=0.3,0.1

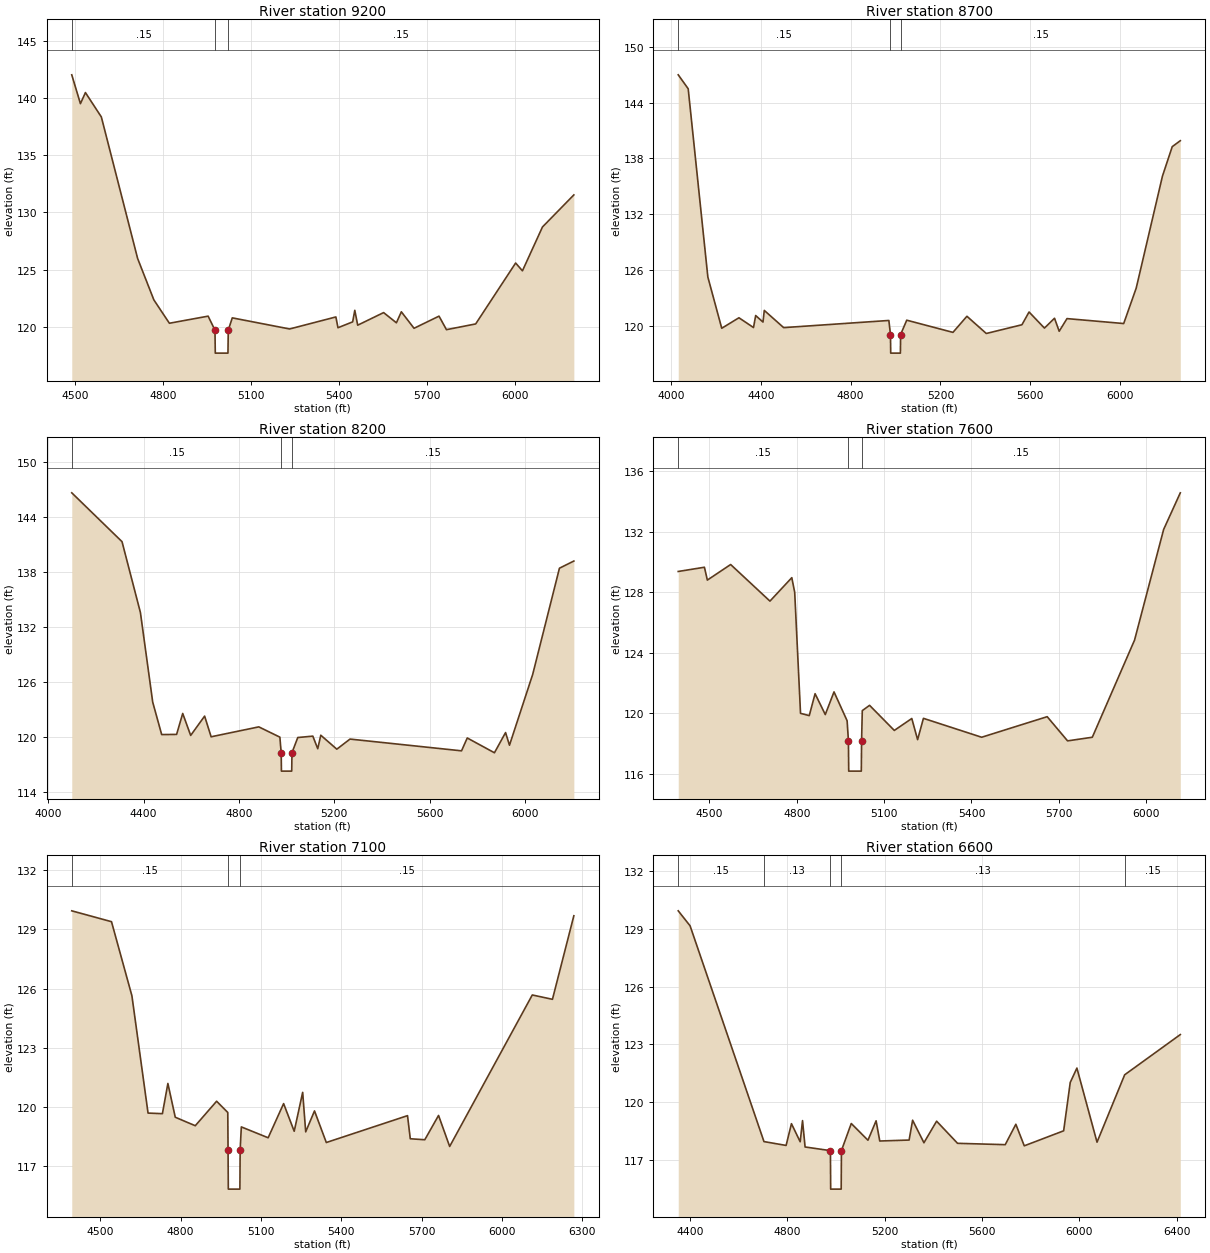
Type RM Length L Ch R = 1 ,9200    ,500,500,500
BEGIN DESCRIPTION:
CEDAR CREEK 25.0
END DESCRIPTION:
XS GIS Cut Line= 3
      2050028.67       733427.99      2049553.56       733613.92
      2048559.98       734285.39
#Sta/Elev= 30
  4489.8  142.02  4519.3   139.5  4536.3  140.47  4590.5  138.34    4714  125.98
  4769.3  122.36  4822.2  120.32  4954.1  120.94  4977.4  119.71  4978.4  117.71
  5021.6  117.71  5022.6  119.71  5036.3  120.79  5231.6  119.82    5389  120.87
  5396.2  119.93  5446.2  120.44  5453.4  121.45  5463.3  120.15  5551.5  121.25
  5595.1  120.36  5611.9  121.32  5655.1  119.88  5740.2  120.94  5765.5  119.76
    5865  120.26    6001  125.58  6024.2   124.9  6092.4  128.73  6199.2  131.53
#Mann= 3 ,-1 , 0
  4489.8     .15       0  4977.4    .045       0  5022.6     .15       0
Bank Sta=4977.4,5022.6
XS Rating Curve= 0 ,0
Exp/Cntr=0.3,0.1

Type RM Length L Ch R = 1 ,8700    ,500,500,500
BEGIN DESCRIPTION:
CEDAR CREEK 24.0
END DESCRIPTION:
XS GIS Cut Line= 3
      2050107.89       732881.45      2049230.67       733291.91
      2048118.12       733902.52
#Sta/Elev= 30
  4031.5  146.98  4075.9  145.48  4163.5  125.25  4225.4  119.74    4302  120.87
    4367  119.82  4376.6  121.11  4409.2  120.41    4415  121.66  4501.4  119.81
  4970.2  120.58  4977.4  119.07  4978.4  117.07  5021.6  117.07  5022.6  119.07
  5049.9  120.61  5255.8   119.3  5318.1  121.03  5404.5  119.18  5563.3  120.12
    5595  121.49  5663.6  119.76  5708.5  120.82  5729.3  119.42  5764.1  120.78
  6016.8  120.25  6072.6  124.06  6189.5  136.09  6233.1  139.26  6269.1   139.9
#Mann= 3 ,-1 , 0
  4031.5     .15       0  4977.4    .045       0  5022.6     .15       0
Bank Sta=4977.4,5022.6
XS Rating Curve= 0 ,0
Exp/Cntr=0.3,0.1

Type RM Length L Ch R = 1 ,8200    ,600,600,600
BEGIN DESCRIPTION:
CEDAR CREEK 23.0
END DESCRIPTION:
XS GIS Cut Line= 3
      2049774.09       732501.83      2048963.85       732896.84
      2048010.13       733634.17
#Sta/Elev= 30
  4098.6  146.61  4309.5  141.29  4386.7  133.57  4438.3  123.81  4475.9  120.28
  4538.5   120.3  4564.2  122.58  4597.6  120.19  4656.1  122.29  4683.4  120.04
  4883.5  121.12  4971.9     120  4977.4   118.3  4978.4   116.3  5021.6   116.3
  5022.6   118.3    5047  119.96  5110.2  120.11  5130.8  118.74  5143.6  120.21
  5210.9  118.69  5266.2  119.79  5734.2  118.51  5758.2  119.91  5872.3   118.3
    5919   120.5  5935.4  119.12  6032.9  126.84  6145.1   138.4  6205.5  139.18
#Mann= 3 ,-1 , 0
  4098.6     .15       0  4977.4    .045       0  5022.6     .15       0
Bank Sta=4977.4,5022.6
XS Rating Curve= 0 ,0
Exp/Cntr=0.3,0.1

Type RM Length L Ch R = 1 ,7600    ,500,500,500
BEGIN DESCRIPTION:
CEDAR CREEK 22.0
END DESCRIPTION:
XS GIS Cut Line= 3
      2048811.94       731978.22      2048547.62       732524.76
      2047823.62       733375.61
#Sta/Elev= 30
  4392.9  129.36  4482.9  129.64  4492.9  128.79  4572.9  129.82  4707.9   127.4
  4782.9  128.95  4792.9  127.98  4812.9  119.98  4842.9  119.83  4862.9  121.28
  4897.9   119.9  4927.9   121.4  4972.9  119.49  4977.4  118.16  4978.4  116.16
  5021.6  116.16  5022.6  118.16    5025  120.16    5050  120.51    5135  118.85
    5195  119.64    5215  118.24    5235  119.65    5435   118.4    5660  119.76
    5730  118.16    5815   118.4    5960  124.82    6060  132.14  6117.2  134.56
#Mann= 3 ,-1 , 0
  4392.9     .15       0  4977.4    .045       0  5022.6     .15       0
Bank Sta=4977.4,5022.6
XS Rating Curve= 0 ,0
Exp/Cntr=0.3,0.1

Type RM Length L Ch R = 1 ,7100    ,500,500,500
BEGIN DESCRIPTION:
CEDAR CREEK 21.0
END DESCRIPTION:
XS GIS Cut Line= 3
      2048579.89       731897.43      2048115.22        732286.9
      2047342.48       733293.37
#Sta/Elev= 30
  4393.7  129.94  4542.1  129.39  4618.3  125.64  4678.6   119.7  4732.2  119.67
  4752.7   121.2  4780.2  119.49    4855  119.06  4934.7   120.3  4976.4  119.73
  4977.4  117.85  4978.4  115.85  5021.6  115.85  5022.6  117.85    5027     119
  5127.2  118.45  5184.9  120.18  5224.5  118.78  5256.1  120.75  5267.4  118.75
  5300.3  119.81  5344.4  118.21  5647.7  119.57    5658   118.4  5712.2  118.35
  5763.6  119.58  5805.1  118.01  6113.7  125.68    6189  125.46  6268.9  129.69
#Mann= 3 ,-1 , 0
  4393.7     .15       0  4977.4    .045       0  5022.6     .15       0
Bank Sta=4977.4,5022.6
XS Rating Curve= 0 ,0
Exp/Cntr=0.3,0.1

Type RM Length L Ch R = 1 ,6600    ,600,600,600
BEGIN DESCRIPTION:
CEDAR CREEK 20.0
END DESCRIPTION:
XS GIS Cut Line= 3
      2048408.11       731677.11      2047804.79       731913.02
      2046559.12       732583.61
#Sta/Elev= 30
  4352.2  129.94  4400.9  129.16  4704.4  117.95  4795.3  117.75  4817.3  118.88
  4853.2  117.94  4862.8  119.04  4873.3  117.67  4977.4  117.48  4978.4  115.48
  5021.6  115.48  5022.6  117.48    5063  118.89  5131.6  118.02    5165  119.03
  5180.1  117.98  5300.7  118.03    5315  119.06  5361.5  117.89  5413.6  119.01
  5499.6  117.86  5695.5  117.79  5739.1  118.85  5773.7  117.73  5935.5  118.51
  5962.5  121.02  5989.9  121.77  6072.6  117.92  6186.1  121.42  6414.7  123.51
#Mann= 5 ,-1 , 0
  4352.2     .15       0  4704.4     .13       0  4977.4    .045       0
  5022.6     .13       0  6186.1     .15       0
Bank Sta=4977.4,5022.6
XS Rating Curve= 0 ,0
Exp/Cntr=0.3,0.1

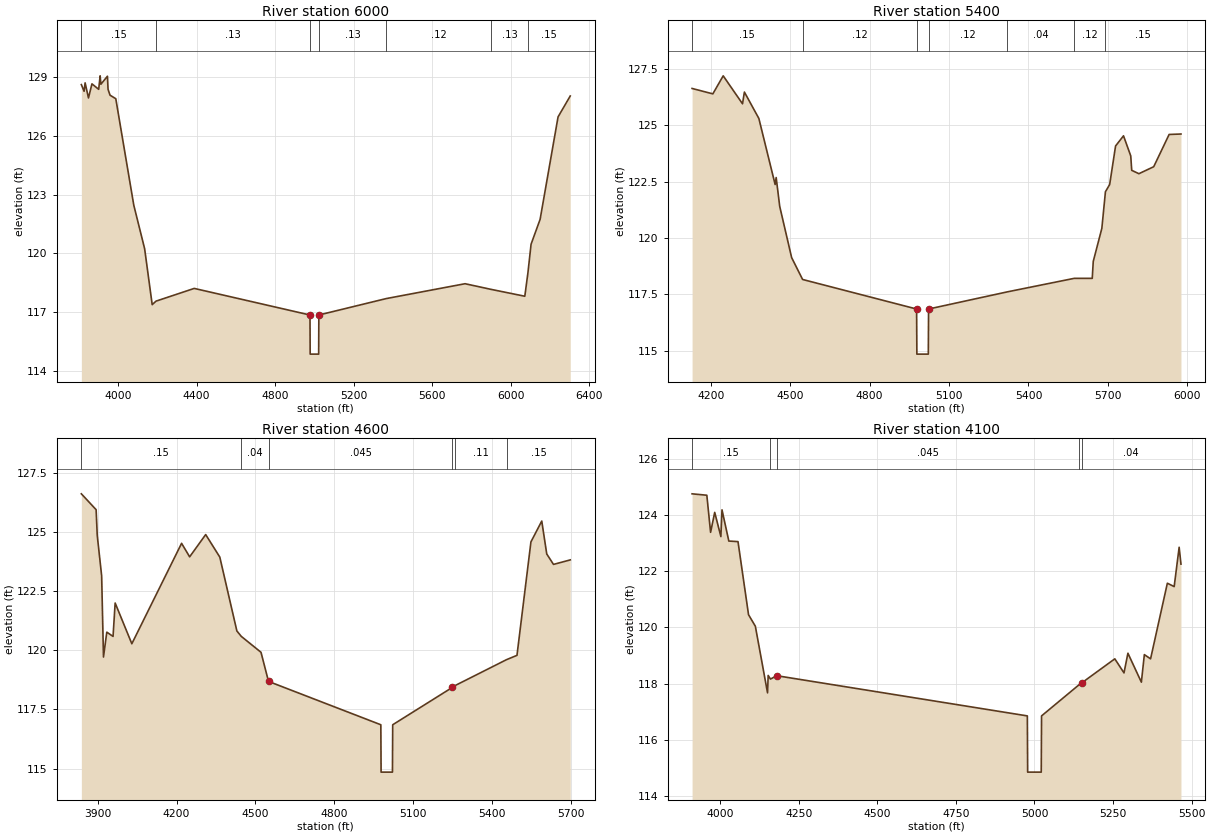
Type RM Length L Ch R = 1 ,6000    ,600,600,600
BEGIN DESCRIPTION:
CEDAR CREEK 19.0
END DESCRIPTION:
XS GIS Cut Line= 3
      2048290.32       730734.58      2047417.41       731538.05
      2046490.37       732452.71
#Sta/Elev= 30
  3813.6  128.63  3827.5  128.29  3832.7  128.72  3849.9  127.95  3867.5  128.67
  3901.8  128.39  3909.2  129.08  3913.1  128.65  3946.4  129.06  3949.5  128.39
  3959.6  128.09  3988.9  127.91  4080.6  122.46  4135.7  120.24  4174.2  117.38
  4193.8  117.56  4388.2  118.21  4977.4  116.85  4978.4  114.85  5021.6  114.85
  5022.6  116.85  5365.5  117.69    5767  118.45  5899.8  118.16    6071  117.81
  6086.9  119.01  6102.9  120.47  6148.9  121.74  6240.3  126.98  6302.3  128.05
#Mann= 7 ,-1 , 0
  3813.6     .15       0  4193.8     .13       0  4977.4    .045       0
  5022.6     .13       0  5365.5     .12       0  5899.8     .13       0
  6086.9     .15       0
Bank Sta=4977.4,5022.6
XS Rating Curve= 0 ,0
Exp/Cntr=0.3,0.1

Type RM Length L Ch R = 1 ,5400    ,800,800,800
BEGIN DESCRIPTION:
CEDAR CREEK 18.0
END DESCRIPTION:
XS GIS Cut Line= 3
       2047216.9       730577.47      2046846.25       731365.23
      2046336.55       732197.44
#Sta/Elev= 30
  4129.4  126.63  4207.8  126.39  4246.9  127.19  4319.9  125.95    4327  126.47
  4381.6   125.3  4443.1  122.37    4447  122.68  4460.4   121.4  4505.4  119.13
  4546.8  118.16  4977.4  116.85  4978.4  114.85  5021.6  114.85  5022.6  116.85
  5319.8  117.61  5572.7  118.21  5640.8  118.21  5644.6  118.96  5677.1  120.43
  5690.6  122.05  5706.6  122.37  5728.9  124.08  5758.9  124.53  5786.2  123.64
  5789.9     123    5817  122.85    5873  123.16  5931.2  124.59  5975.9  124.61
#Mann= 7 ,-1 , 0
  4129.4     .15       0  4546.8     .12       0  4977.4    .045       0
  5022.6     .12       0  5319.8     .04       0  5572.7     .12       0
  5690.6     .15       0
Bank Sta=4977.4,5022.6
XS Rating Curve= 0 ,0
Exp/Cntr=0.3,0.1

Type RM Length L Ch R = 1 ,4600    ,500,500,500
BEGIN DESCRIPTION:
CEDAR CREEK 17.0
END DESCRIPTION:
XS GIS Cut Line= 3
      2046170.46       730104.58      2046061.12       731261.62
      2046154.09       731953.61
#Sta/Elev= 30
  3837.8   126.6    3894  125.93  3898.2  124.85    3915  123.14    3922  119.71
  3934.6  120.76  3958.4  120.58  3966.4  121.99  4029.9  120.27  4219.2  124.51
  4249.9  123.94  4310.9  124.88  4364.6  123.93  4429.6  120.81  4446.5  120.58
  4521.4  119.91    4550  118.68  4977.4  116.85  4978.4  114.85  5021.6  114.85
  5022.6  116.85    5250  118.43  5259.2   118.5    5456   119.6  5495.5  119.78
  5548.6  124.57  5589.8  125.45  5608.8  124.06  5634.5  123.62  5698.2  123.81
#Mann= 6 ,-1 , 0
  3837.8     .15       0  4446.5     .04       0    4550    .045       0
    5250     .04       0  5259.2     .11       0    5456     .15       0
Bank Sta=4550,5250
XS Rating Curve= 0 ,0
Exp/Cntr=0.3,0.1

Type RM Length L Ch R = 1 ,4100    ,400,400,400
BEGIN DESCRIPTION:
CEDAR CREEK 16.0
END DESCRIPTION:
XS GIS Cut Line= 3
      2045312.42       730322.46      2045578.75        731378.7
      2045656.46       731838.38
#Sta/Elev= 30
  3910.7  124.75  3957.6   124.7  3969.6  123.38  3982.7  124.09  4002.3  123.23
  4005.9  124.18  4027.6  123.07  4056.8  123.05  4090.3  120.45    4112  120.04
  4150.8  117.67  4152.8  118.29  4160.1  118.16    4180  118.28  4977.4  116.85
  4978.4  114.85  5021.6  114.85  5022.6  116.85  5141.1  117.95    5150  118.02
  5255.7  118.88  5284.9  118.38  5297.4  119.08  5340.2  118.05  5349.7  119.03
  5369.5  118.88  5422.9  121.57  5444.6  121.45  5460.4  122.85  5466.2  122.25
#Mann= 5 ,-1 , 0
  3910.7     .15       0  4160.1     .04       0    4180    .045       0
  5141.1     .15       0    5150     .04       0
Bank Sta=4180,5150
XS Rating Curve= 0 ,0
Exp/Cntr=0.3,0.1