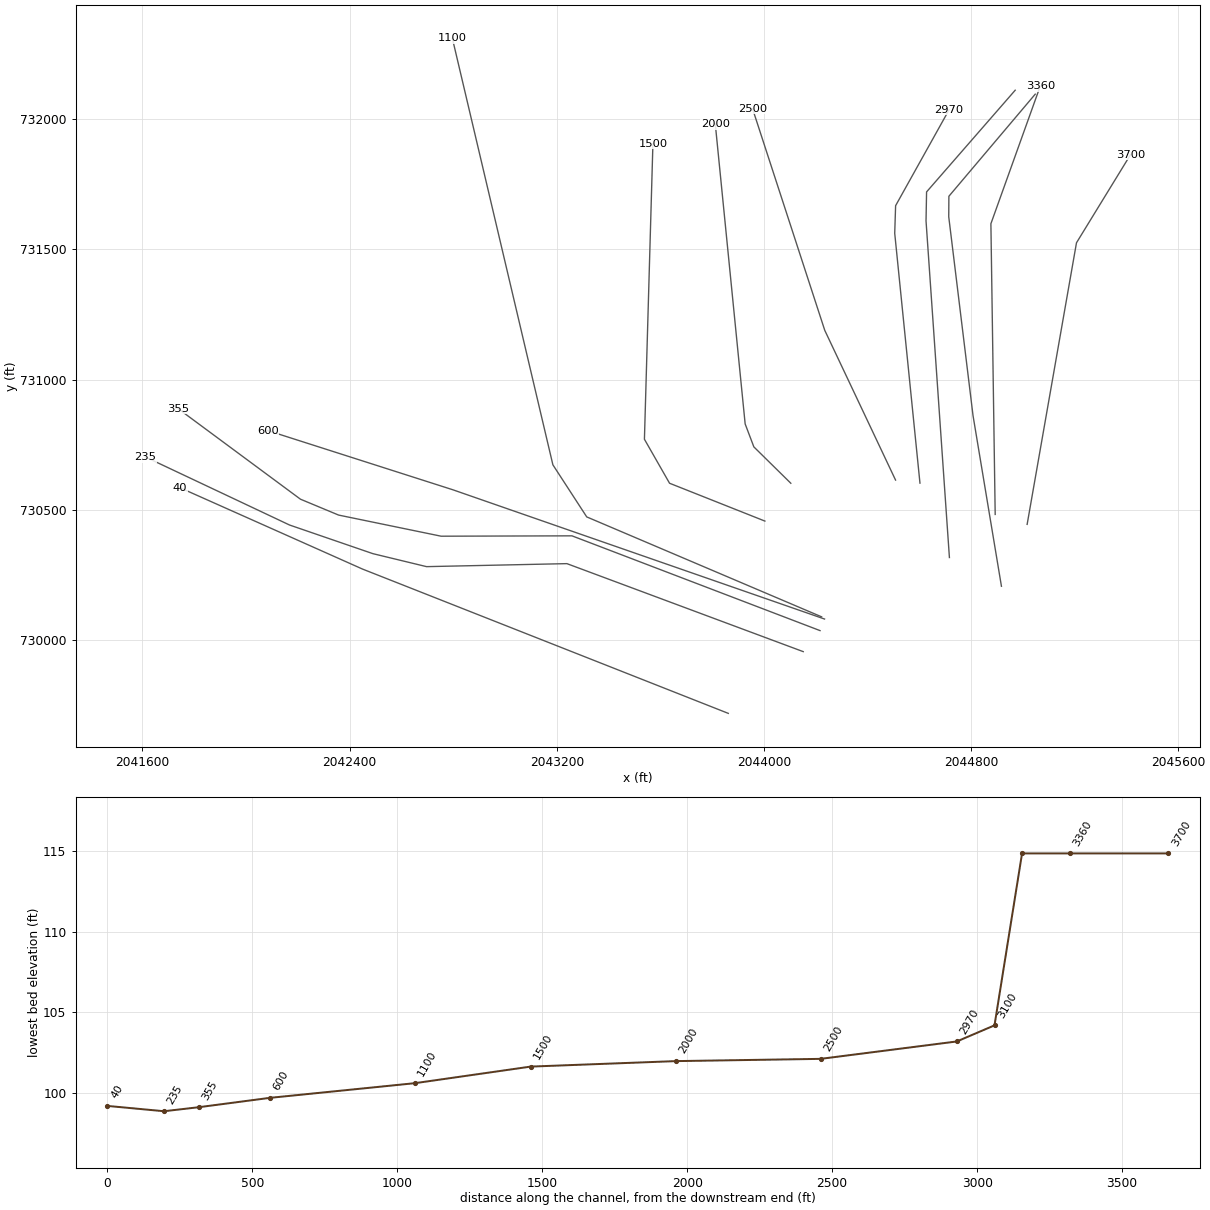
HEC-RAS study Cedar Creek.prj: Cedar Creek Limited Detail Study

--- Cedar Creek.g04 (geometry) --- (continued)

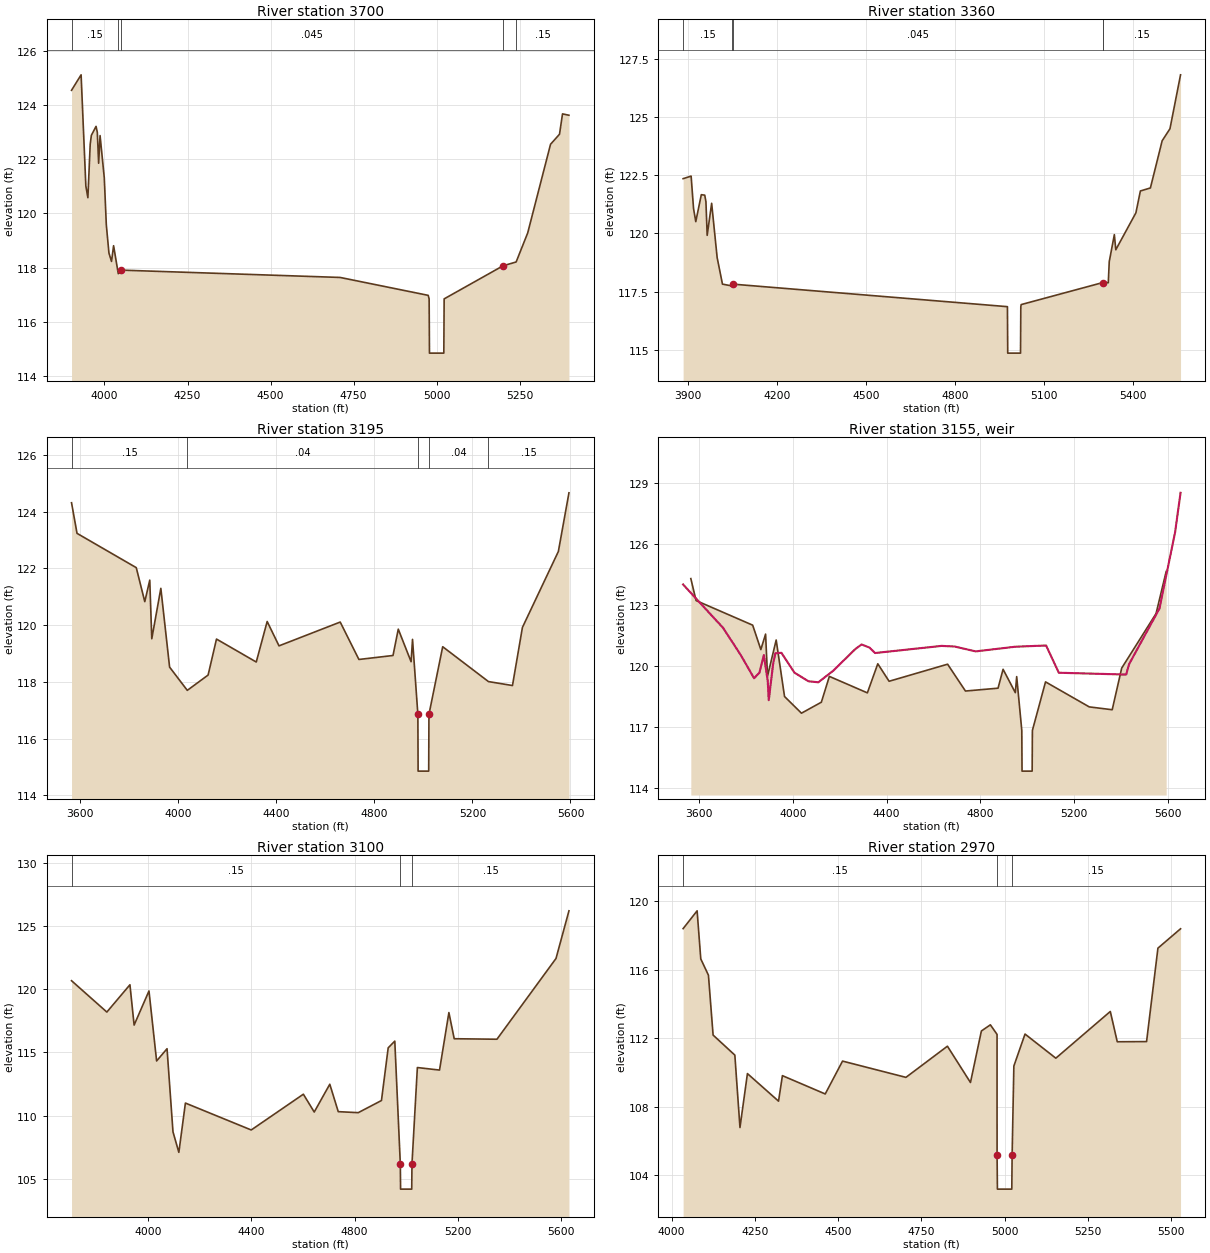
Type RM Length L Ch R = 1 ,3700    ,340,340,340
BEGIN DESCRIPTION:
CEDAR CREEK 15.0
END DESCRIPTION:
XS GIS Cut Line= 3
      2045016.15       730443.21      2045206.73       731525.66
       2045415.6        731864.8
#Sta/Elev= 30
  3900.9  124.54  3929.7  125.11    3944  121.01  3950.1  120.58  3957.1  122.55
  3960.6  122.88  3974.7  123.21  3978.5  122.99  3982.5  121.85  3986.8  122.87
  3999.5  121.31  4005.6  119.58  4013.5  118.54  4021.3  118.23  4027.5  118.81
  4041.6  117.78    4050  117.91  4709.4  117.64  4974.6  116.98  4977.4  116.85
  4978.4  114.85  5021.6  114.85  5022.6  116.85    5200  118.07  5239.3  118.21
  5274.1  119.28  5342.9  122.55  5369.9  122.92  5378.9  123.67  5398.3  123.62
#Mann= 5 ,-1 , 0
  3900.9     .15       0  4041.6     .04       0    4050    .045       0
    5200     .04       0  5239.3     .15       0
Bank Sta=4050,5200
XS Rating Curve= 0 ,0
Exp/Cntr=0.3,0.1

Type RM Length L Ch R = 1 ,3360    ,165,165,165
BEGIN DESCRIPTION:
CEDAR CREEK 14.0
END DESCRIPTION:
XS GIS Cut Line= 3
      2044892.79       730481.42      2044876.21        731598.9
      2045066.65       732127.54
#Sta/Elev= 30
  3882.4  122.36  3909.4  122.47  3917.6  121.07  3925.1  120.51  3943.8  121.67
  3955.4  121.65  3959.4  121.37  3963.6  119.92  3978.7   121.3  3997.3  118.96
  4015.2  117.82  4048.1  117.74    4050  117.82  4977.4  116.85  4978.4  114.85
  5021.6  114.85  5022.6  116.85  5023.9  116.94    5300  117.89  5300.9  117.89
  5317.9  117.88  5321.2  118.79  5338.4  119.95  5343.3   119.3  5411.2  120.89
  5426.3  121.83  5460.1  121.96  5499.8  123.99  5526.2  124.51  5561.9  126.83
#Mann= 5 ,-1 , 0
  3882.4     .15       0  4048.1     .04       0    4050    .045       0
    5300     .04       0  5300.9     .15       0
Bank Sta=4050,5300
XS Rating Curve= 0 ,0
Exp/Cntr=0.3,0.1

Type RM Length L Ch R = 1 ,3195    ,95,95,95
BEGIN DESCRIPTION:
CDC_Dam (1)-US
END DESCRIPTION:
XS GIS Cut Line= 5
      2044916.94       730205.31      2044807.23       730861.18
      2044713.41       731625.77      2044713.97       731704.47
      2045047.41       732096.94
#Sta/Elev= 30
  3564.7  124.32  3587.1  123.24  3828.7  122.03  3863.5  120.83  3883.8  121.59
    3892  119.52    3929   121.3  3964.7  118.52  4036.9   117.7  4121.8  118.24
    4156  119.51  4318.2   118.7  4362.7  120.13    4411  119.27  4660.7  120.11
  4736.9  118.79    4876  118.93  4897.5  119.86  4949.8  118.71  4955.6   119.5
  4977.4  116.85  4978.4  114.85  5021.6  114.85  5022.6  116.85  5078.7  119.24
  5265.3  118.01  5363.3  117.87  5403.9  119.92  5550.5   122.6  5593.7  124.67
#Mann= 5 ,-1 , 0
  3564.7     .15       0  4036.9     .04       0  4977.4    .045       0
  5022.6     .04       0  5265.3     .15       0
Bank Sta=4977.4,5022.6
XS Rating Curve= 0 ,0
Exp/Cntr=0.3,0.1

Type RM Length L Ch R = 5 ,3155    ,,,
BEGIN DESCRIPTION:
CDC_Dam (1)-TOR
Structure ID: lds 282
Approximate Survey Structure
END DESCRIPTION:
IW Pilot Flow=0
#Inline Weir SE= 30
  3531.8  124.03  3702.1   121.9  3777.8  120.56  3834.5  119.42  3857.4  119.69
  3876.4  120.56    3893  119.28  3897.3  118.34  3916.1  120.14  3925.4  120.65
  3951.3  120.67  4007.2  119.69  4066.9  119.27  4108.9  119.22  4172.7  119.79
  4267.3  120.86  4293.5  121.08  4326.7  120.93  4351.3  120.66    4635  121.01
  4690.5  120.98  4780.4  120.74    4950  120.97  5081.1  121.03  5135.4  119.69
  5422.8   119.6  5435.3  120.11    5565  122.85  5631.6  126.59    5655  128.54
IW Dist,WD,Coef,Skew,MaxSub,Min_El,Is_Ogee,SpillHt,DesHd
32.5,15,3,0,0.95,, 0 ,,,1,1,

Type RM Length L Ch R = 1 ,3100    ,130,130,130
BEGIN DESCRIPTION:
CDC_Dam (1)-DS
END DESCRIPTION:
XS GIS Cut Line= 4
      2044716.02       730315.77      2044625.73       731609.72
      2044627.81       731721.22      2044970.07       732112.15
#Sta/Elev= 30
  3702.9  120.67  3839.8  118.19  3929.3  120.35  3945.5  117.16  4003.1  119.86
  4032.7  114.32  4073.1  115.29  4096.2  108.71  4118.9  107.09  4144.3  110.99
  4399.5  108.86  4601.6  111.69  4643.7  110.28    4704  112.48  4736.8  110.31
  4814.3  110.23  4904.3  111.19  4930.4  115.36    4956  115.89  4977.4  106.18
  4978.4  104.18  5021.6  104.18  5022.6  106.18  5043.5   113.8  5129.4   113.6
  5165.7  118.15  5186.3  116.08    5352  116.04  5580.9  122.43  5631.1   126.2
#Mann= 3 ,-1 , 0
  3702.9     .15       0  4977.4    .045       0  5022.6     .15       0
Bank Sta=4977.4,5022.6
XS Rating Curve= 0 ,0
Exp/Cntr=0.3,0.1

Type RM Length L Ch R = 1 ,2970    ,470,470,470
BEGIN DESCRIPTION:
CEDAR CREEK 10.0
END DESCRIPTION:
XS GIS Cut Line= 4
      2044602.29       730601.79      2044504.82       731562.16
      2044508.25        731668.3      2044714.49       732036.58
#Sta/Elev= 30
  4034.7   118.4  4076.7  119.44  4087.7  116.63  4110.7  115.68  4124.7  112.18
    4190  111.01  4205.4  106.78  4227.8  109.93  4321.2  108.32  4332.8  109.81
  4461.4  108.74  4513.4  110.66  4703.7  109.71  4828.3  111.53  4897.5  109.41
  4930.3  112.42  4957.3  112.78  4977.3  112.22  4977.4  105.18  4978.4  103.18
  5021.6  103.18  5022.6  105.18  5027.8  110.37  5061.3  112.24  5153.8  110.83
  5317.4  113.56  5338.3  111.79  5426.3   111.8  5460.4  117.26  5528.3  118.39
#Mann= 3 ,-1 , 0
  4034.7     .15       0  4977.4    .045       0  5022.6     .15       0
Bank Sta=4977.4,5022.6
XS Rating Curve= 0 ,0
Exp/Cntr=0.3,0.1

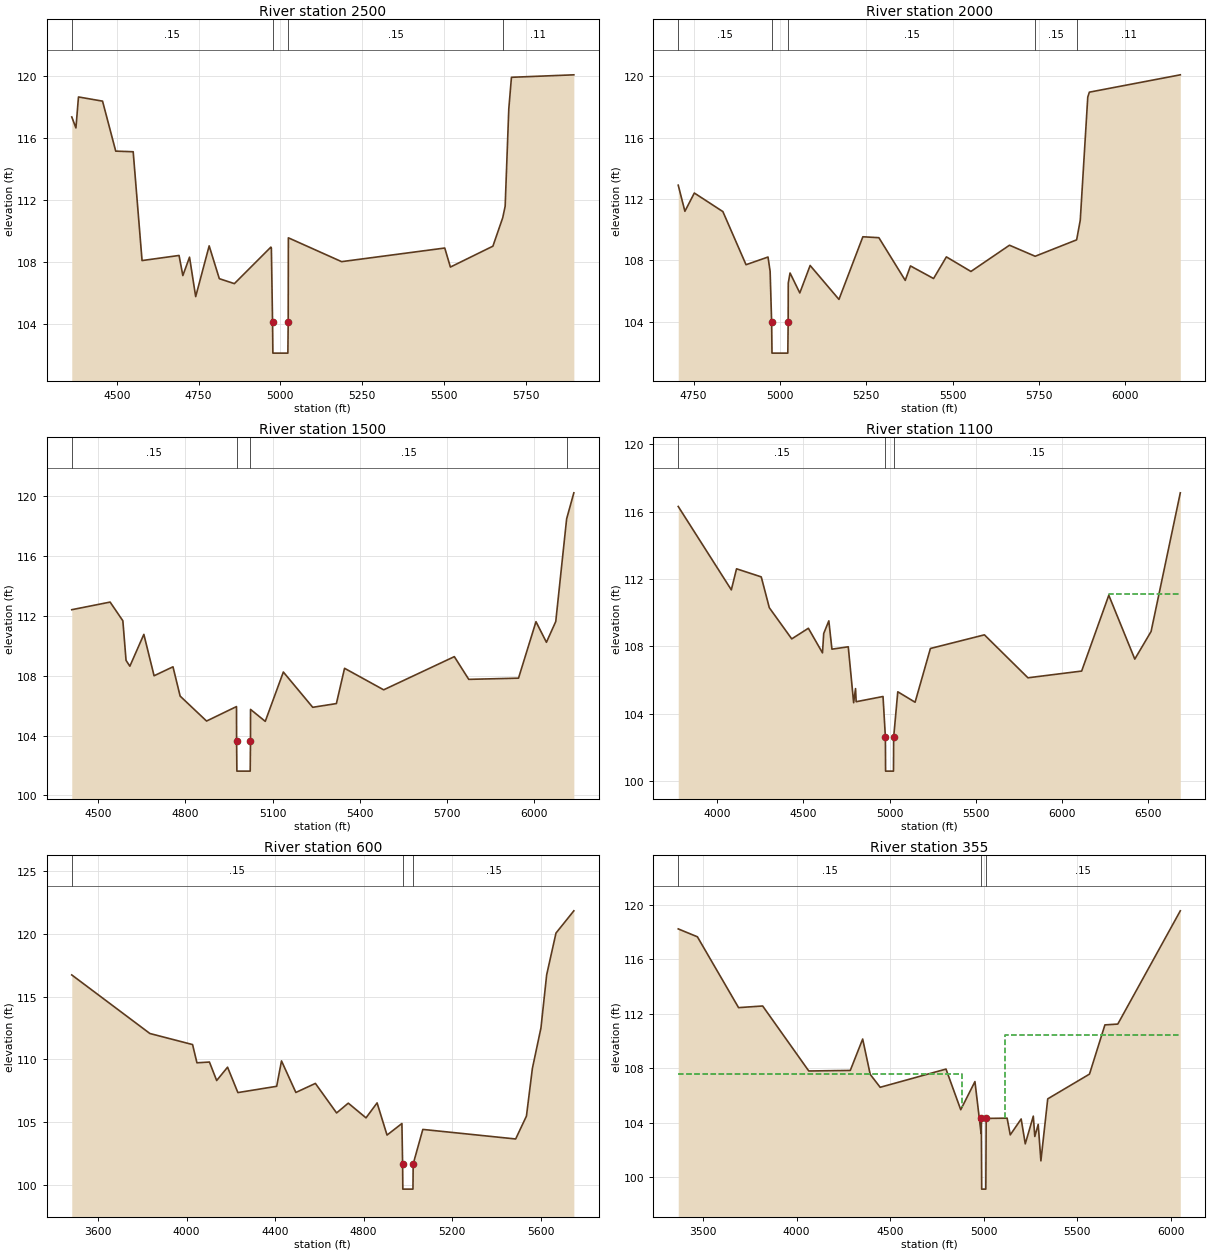
Type RM Length L Ch R = 1 ,2500    ,500,500,500
BEGIN DESCRIPTION:
CEDAR CREEK 9.0
END DESCRIPTION:
XS GIS Cut Line= 3
      2044508.02       730613.55      2044234.64       731189.13
      2043955.82       732041.06
#Sta/Elev= 30
  4362.8  117.36  4375.5  116.65  4383.3  118.65  4456.8  118.38  4497.1  115.15
  4550.4  115.11  4577.5  108.08  4690.5  108.41  4702.1  107.11  4722.5   108.3
  4741.3  105.75  4782.5  109.03  4813.5  106.91  4859.5  106.59    4971  108.95
  4972.5  108.88  4976.1   104.1  4977.1   102.1  5022.9   102.1  5023.9   104.1
  5024.4  109.55    5187  108.01  5502.1  108.89  5519.3  107.66  5649.2  109.01
  5679.2  110.85  5686.6  111.59  5697.7  117.87  5705.8  119.92  5896.4  120.08
#Mann= 4 ,-1 , 0
  4362.8     .15       0  4976.1    .045       0  5023.9     .15       0
  5679.2     .11       0
Bank Sta=4976.1,5023.9
XS Rating Curve= 0 ,0
Exp/Cntr=0.3,0.1

Type RM Length L Ch R = 1 ,2000    ,500,500,500
BEGIN DESCRIPTION:
CEDAR CREEK 8.0
END DESCRIPTION:
XS GIS Cut Line= 4
      2044103.56       730601.32      2043960.82       730741.12
      2043927.25       730829.35       2043811.9        731982.3
#Sta/Elev= 30
  4705.8   112.9  4725.1   111.2  4752.4  112.39    4835  111.18    4902  107.72
  4965.6  108.22  4971.7  107.29  4976.1  103.96  4977.1  101.96  5022.9  101.96
  5023.9  103.96  5024.2  106.52  5029.4  107.18  5057.6  105.88  5087.5  107.67
  5170.9  105.46  5240.1  109.54  5286.4  109.48  5362.7   106.7  5377.8  107.64
  5444.7  106.82  5481.8  108.23  5552.8  107.28  5664.4  108.99  5738.7  108.27
  5858.7  109.34  5869.2  110.62  5890.9  118.64  5895.5  118.96  6158.7  120.09
#Mann= 5 ,-1 , 0
  4705.8     .15       0  4976.1    .045       0  5023.9     .15       0
  5738.7     .15       0  5858.7     .11       0
Bank Sta=4976.1,5023.9
XS Rating Curve= 0 ,0
Exp/Cntr=0.3,0.1

Type RM Length L Ch R = 1 ,1500    ,400,400,400
BEGIN DESCRIPTION:
CEDAR CREEK 7.0
END DESCRIPTION:
XS GIS Cut Line= 4
      2044003.46       730455.91       2043635.3       730601.34
      2043538.26       730770.43      2043571.05       731905.95
#Sta/Elev= 30
  4409.2  112.42  4541.1  112.93  4584.9  111.68  4595.9  109.03    4609  108.64
  4657.1  110.77  4692.3     108  4757.3   108.6  4781.9  106.64  4872.8  104.97
  4975.8  105.94  4976.1  103.62  4977.1  101.62  5022.9  101.62  5023.9  103.62
    5024  105.75  5074.7  104.95  5136.9  108.25  5237.9  105.89  5319.3  106.14
  5347.4   108.5  5481.9  107.06    5725  109.28  5774.5  107.76  5945.7  107.84
  6005.8  111.62  6041.7  110.24  6073.8  111.63  6111.2   118.5    6136  120.24
#Mann= 4 ,-1 , 0
  4409.2     .15       0  4976.1    .045       0  5023.9     .15       0
  6111.2     .11       0
Bank Sta=4976.1,5023.9
XS Rating Curve= 0 ,0
Exp/Cntr=0.3,0.1

Type RM Length L Ch R = 1 ,1100    ,500,500,500
BEGIN DESCRIPTION:
CEDAR CREEK 6.0
END DESCRIPTION:
XS GIS Cut Line= 4
      2044222.54        730087.8      2043315.47       730471.95
      2043184.76        730672.2      2042796.59       732311.57
#Sta/Elev= 30
  3775.8   116.3  4083.4  111.35  4113.6   112.6  4256.8  112.12  4303.5  110.29
  4433.4  108.44  4529.8  109.07  4611.5  107.61  4618.7  108.76  4648.3  109.51
  4666.3  107.83  4760.9  107.97  4792.1  104.65    4803  105.49  4806.7  104.71
  4962.3  105.02  4976.1  102.59  4977.1  100.59  5022.9  100.59  5023.9  102.59
  5047.8   105.3  5148.1  104.68  5236.9  107.87  5549.7  108.68    5802  106.13
  6113.1  106.53  6270.4  111.03    6421  107.24  6515.4  108.88  6684.7  117.11
#Mann= 3 ,-1 , 0
  3775.8     .15       0  4976.1    .045       0  5023.9     .15       0
#XS Ineff= 2 , 0
       0                    6270       0   111.1
Permanent Ineff=
       F       F
Bank Sta=4976.1,5023.9
XS Rating Curve= 0 ,0
Exp/Cntr=0.3,0.1

Type RM Length L Ch R = 1 ,600     ,245,245,245
BEGIN DESCRIPTION:
CEDAR CREEK 5.0
END DESCRIPTION:
XS GIS Cut Line= 3
      2044233.81       730079.37      2042798.28       730576.29
      2042083.61       730803.77
#Sta/Elev= 30
  3480.9  116.72    3834  112.06  4026.9  111.18  4046.6  109.73  4103.1  109.79
  4135.8  108.32    4185  109.38  4231.7  107.36    4407  107.86  4428.8  109.88
  4493.7  107.37  4581.9  108.09  4677.8  105.74  4730.6  106.52  4810.7  105.35
  4860.8  106.54  4905.7  103.98    4973   104.9  4976.1  101.68  4977.1   99.68
  5022.9   99.68  5023.9  101.68  5067.5  104.43    5487  103.67  5535.8  105.49
  5562.6  109.28  5601.4  112.51  5627.2  116.73  5669.3  120.05    5750  121.82
#Mann= 3 ,-1 , 0
  3480.9     .15       0  4976.1    .045       0  5023.9     .15       0
Bank Sta=4976.1,5023.9
XS Rating Curve= 0 ,0
Exp/Cntr=0.5,0.3

Type RM Length L Ch R = 1 ,355     ,120,120,120
BEGIN DESCRIPTION:
CDC_Old Buff Rd-US
END DESCRIPTION:
XS GIS Cut Line= 6
      2044216.41       730034.86      2043258.47       730399.16
      2042753.26       730397.76      2042357.28       730478.97
      2042209.98       730540.02      2041736.93       730888.51
#Sta/Elev= 30
  3367.7  118.24  3470.1  117.66    3690  112.45  3818.8  112.57  4065.2  107.79
  4286.9  107.83  4353.1  110.14  4393.4  107.54  4446.6  106.59  4798.3  107.93
    4877  104.94  4952.9  107.01  4985.7   103.2    4987   104.3    4989    99.1
    5011    99.1    5013   104.3  5124.8  104.32  5141.6  103.09  5199.8  104.26
  5221.8  102.43  5264.7  104.47  5272.7  102.97  5290.9  103.86  5305.3  101.18
  5341.8  105.74  5564.9  107.56  5647.3  111.18  5716.1  111.24  6050.1  119.57
#Mann= 3 ,-1 , 0
  3367.7     .15       0    4987    .045       0    5013     .15       0
#XS Ineff= 2 , 0
       0    4884  107.59    5116       0   110.4
Permanent Ineff=
       F       F
Bank Sta=4987,5013
XS Rating Curve= 0 ,0
Exp/Cntr=0.5,0.3

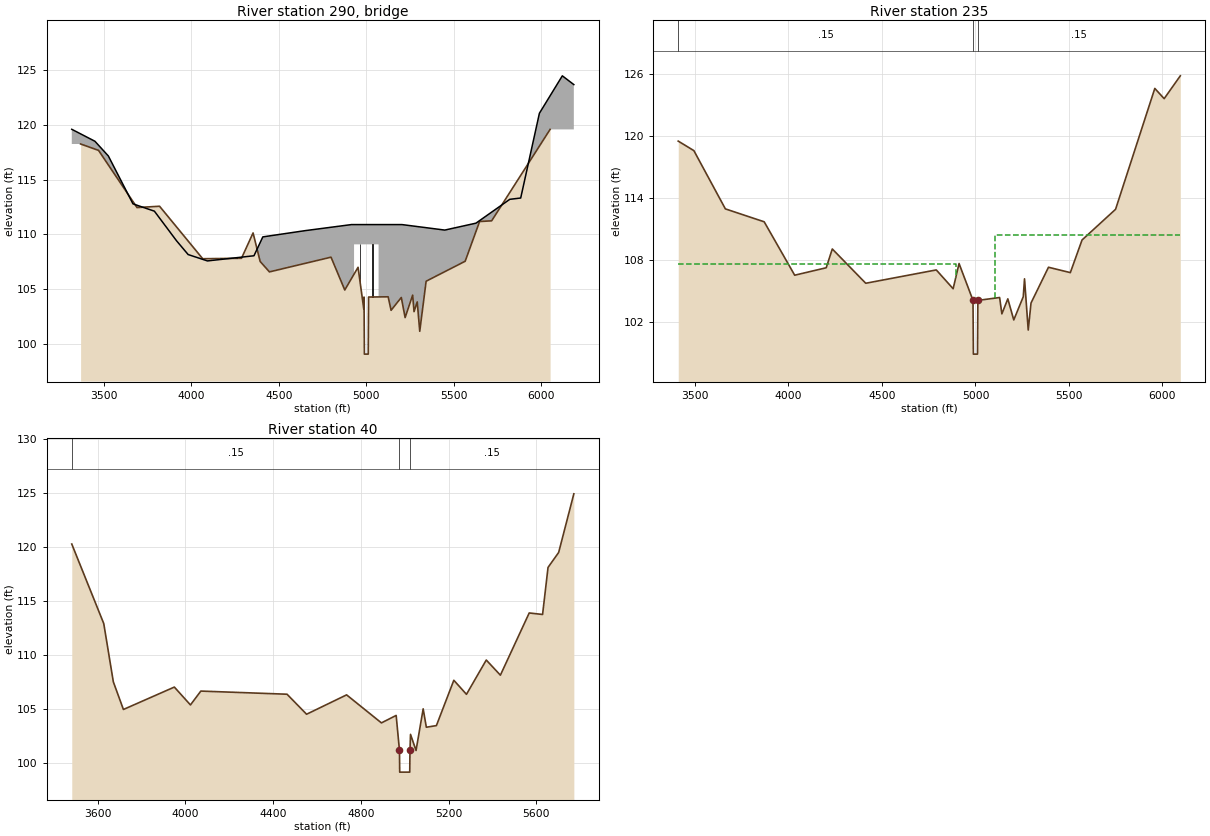
Type RM Length L Ch R = 3 ,290     ,,,
BEGIN DESCRIPTION:
CDC_Old Buff Rd-TOR
Structure ID: lds 285
Approximate Survey Structure
END DESCRIPTION:
Bridge Culvert--1,0,-1,-1, 0
Deck Dist Width WeirC Skew NumUp NumDn MinLoCord MaxHiCord MaxSubmerge Is_Ogee
46,38,3,0, 24, 24, , , 0.95, 0, 1,1,,
  3317.2  3449.5  3526.2  3666.8  3789.4  3915.5  3982.1  4092.3  4358.2  4408.7
  4651.3  4914.9    4930    4930    5070    5070  5203.9  5448.3  5626.5  5819.6
  5882.1  5988.9  6119.9  6185.7
  119.58  118.49  117.15  112.79  112.12  109.43  108.17  107.59  108.06  109.78
  110.35   110.9   110.9   110.9   110.9   110.9   110.9   110.4  111.03   113.2
  113.32  121.04  124.45  123.65
    79.1    79.1    79.1    79.1    79.1    79.1    79.1    79.1    79.1    79.1
    79.1    79.1    79.1   109.1   109.1    79.1    79.1    79.1    79.1    79.1
    79.1    79.1    79.1    79.1
  3317.2  3449.5  3526.2  3666.8  3789.4  3915.5  3982.1  4092.3  4358.2  4408.7
  4651.3  4914.9    4930    4930    5070    5070  5203.9  5448.3  5626.5  5819.6
  5882.1  5988.9  6119.9  6185.7
  119.58  118.49  117.15  112.79  112.12  109.43  108.17  107.59  108.06  109.78
  110.35   110.9   110.9   110.9   110.9   110.9   110.9   110.4  111.03   113.2
  113.32  121.04  124.45  123.65
    79.1    79.1    79.1    79.1    79.1    79.1    79.1    79.1    79.1    79.1
    79.1    79.1    79.1   109.1   109.1    79.1    79.1    79.1    79.1    79.1
    79.1    79.1    79.1    79.1
Pier Skew, UpSta & Num, DnSta & Num=  ,4965, 2 ,4965, 2 , 0 , 0 , 0 ,0,0
       1       1
  105.75   109.1
       1       1
  106.07   109.1
Pier Skew, UpSta & Num, DnSta & Num=  ,5035, 2 ,5035, 2 , 0 , 0 , 0 ,0,0
       1       1
  104.32   109.1
       1       1
   104.3   109.1
Abutment Skew #Up #Dn= , 2 , 2
    4930    4942
   109.1  106.31
    4930    4942
   109.1  106.05
Abutment Skew #Up #Dn= , 2 , 2
    5058    5070
  103.89   109.1
    5058    5070
  103.38   109.1
BR Coef= 1 , 1 , 0 ,1.25, 0 ,,,0.8,0,2,0,
WSPro=,,,, 1 ,,,, 0 ,,,, 0 ,,,,-1 ,-1 ,-1 , 0 , 0 , 0 , 0 , 0
BC Design=,, 0 ,, 0 ,,,,,,
BC HTab HWMax=119.57
BC Use User HTab Curves=0
BC User HTab FreeFlow(D)= 0

Type RM Length L Ch R = 1 ,235     ,195,195,195
BEGIN DESCRIPTION:
CDC_Old Buff Rd-DS
END DESCRIPTION:
XS GIS Cut Line= 6
      2044151.53       729954.02      2043238.83       730292.32
      2042696.94       730280.74      2042489.52       730330.71
      2042167.89       730440.75      2041611.06        730702.4
#Sta/Elev= 30
  3410.5  119.47  3494.1  118.55  3662.6  112.91  3870.2  111.66  4033.3  106.49
    4202  107.21  4234.4  109.03  4413.3  105.71  4790.6     107  4880.7  105.18
  4912.4  107.62    4987  104.05    4989   98.85    5011   98.85    5013  104.05
  5129.3  104.33  5141.4  102.75  5173.2   104.2    5205  102.16  5255.7   104.4
  5262.5  106.14  5282.3  101.18  5297.3   103.8  5390.7  107.26  5507.5  106.74
  5570.2   109.9  5749.5  112.87  5959.3  124.57  6009.4  123.58  6095.7  125.79
#Mann= 3 ,-1 , 0
  3410.5     .15       0    4987    .045       0    5013     .15       0
#XS Ineff= 2 , 0
       0    4894  107.59    5106       0   110.4
Permanent Ineff=
       F       F
Bank Sta=4987,5013
XS Rating Curve= 0 ,0
Exp/Cntr=0.5,0.3

Type RM Length L Ch R = 1 ,40      ,0,0,0
BEGIN DESCRIPTION:
CEDAR CREEK 1.0
END DESCRIPTION:
XS GIS Cut Line= 3
      2043862.16        729716.7      2042449.67        730271.4
      2041745.08       730583.94
#Sta/Elev= 30
  3482.5  120.26  3628.3  112.91    3672  107.52  3717.9  104.97    3950  107.04
  4023.4  105.39  4070.7  106.67  4463.6  106.38  4552.7  104.53  4735.1  106.32
  4893.8  103.73    4961  104.42  4976.1  101.18  4977.1   99.18  5022.9   99.18
  5023.9  101.18  5026.4  102.67  5051.6  101.18  5084.1  105.03  5098.5  103.33
  5144.4  103.48  5223.8  107.67  5281.4  106.37  5371.7  109.54    5436  108.14
  5567.4  113.89  5628.3  113.75  5653.2   118.1  5701.6  119.48  5770.8   124.9
#Mann= 3 ,-1 , 0
  3482.5     .15       0  4976.1    .045       0  5023.9     .15       0
Bank Sta=4976.1,5023.9
XS Rating Curve= 0 ,0
Exp/Cntr=0.3,0.1

Chan Stop Cuts=-1
Use User Specified Reach Order=0
Composite Channel Slope=5

--- Cedar Creek.g01 (geometry) ---

Geom Title=Existing Conditions
Program Version=4.10

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
River Reach=Cedar Creek     ,Reach-1

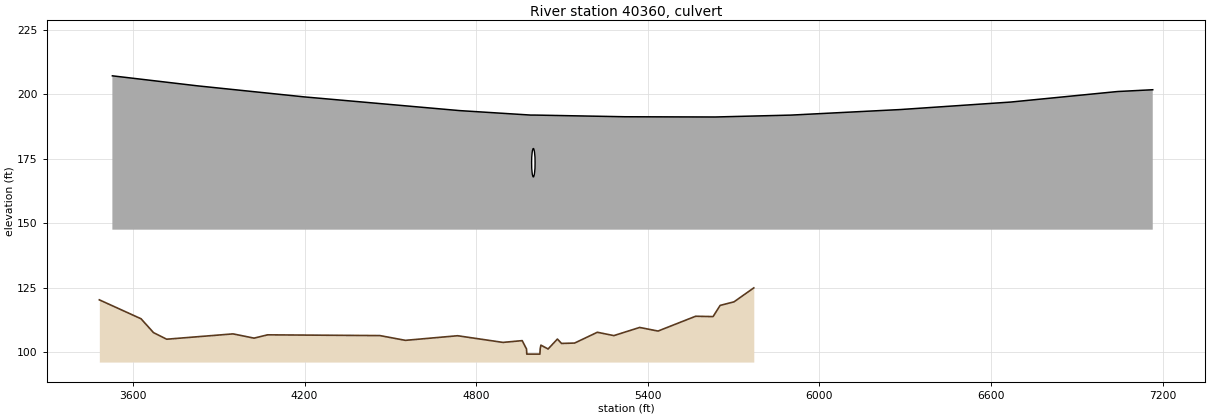
Type RM Length L Ch R = 2 ,40360   ,,,
BEGIN DESCRIPTION:
CDC_Railroad (2)-TOR
Structure ID: lds 274
Approximate Survey Structure
END DESCRIPTION:
Bridge Culvert--1,0,-1,-1, 0
Deck Dist Width WeirC Skew NumUp NumDn MinLoCord MaxHiCord MaxSubmerge Is_Ogee
26,58,3,0, 13, 13, , , 0.95, 0, 1,1,,
  3528.1  3825.8  4200.2  4741.9  4991.2  5006.2  5319.8  5635.5  5900.3  6283.4
  6669.2  7041.8  7165.7
  207.24  203.35  199.05  193.74     192     192  191.35  191.26  191.99  194.15
  197.06  201.14  201.84
   147.5   147.5   147.5   147.5   147.5   147.5   147.5   147.5   147.5   147.5
   147.5   147.5   147.5
  3528.1  3825.8  4200.2  4741.9  4991.2  5006.2  5319.8  5635.5  5900.3  6283.4
  6669.2  7041.8  7165.7
  207.24  203.35  199.05  193.74     192     192  191.35  191.26  191.99  194.15
  197.06  201.14  201.84
  147.21  147.21  147.21  147.21  147.21  147.21  147.21  147.21  147.21  147.21
  147.21  147.21  147.21
BR Coef= 1 , 1 , 0 ,1.25, 0 ,,,0.8,0,2,0,
WSPro=,,,, 1 ,,,, 0 ,,,, 0 ,,,,-1 ,-1 ,-1 , 0 , 0 , 0 , 0 , 0
Culvert=4,11,12,58,0.012,0.4,1,29,1,168,5000,167.71,5000,Culvert #1  , 0 ,26
Culvert Bottom n=0.012
BC Design=,, 0 ,, 0 ,,,,,,
BC HTab HWMax=203.4
BC Use User HTab Curves=0
BC User HTab FreeFlow(D)= 0